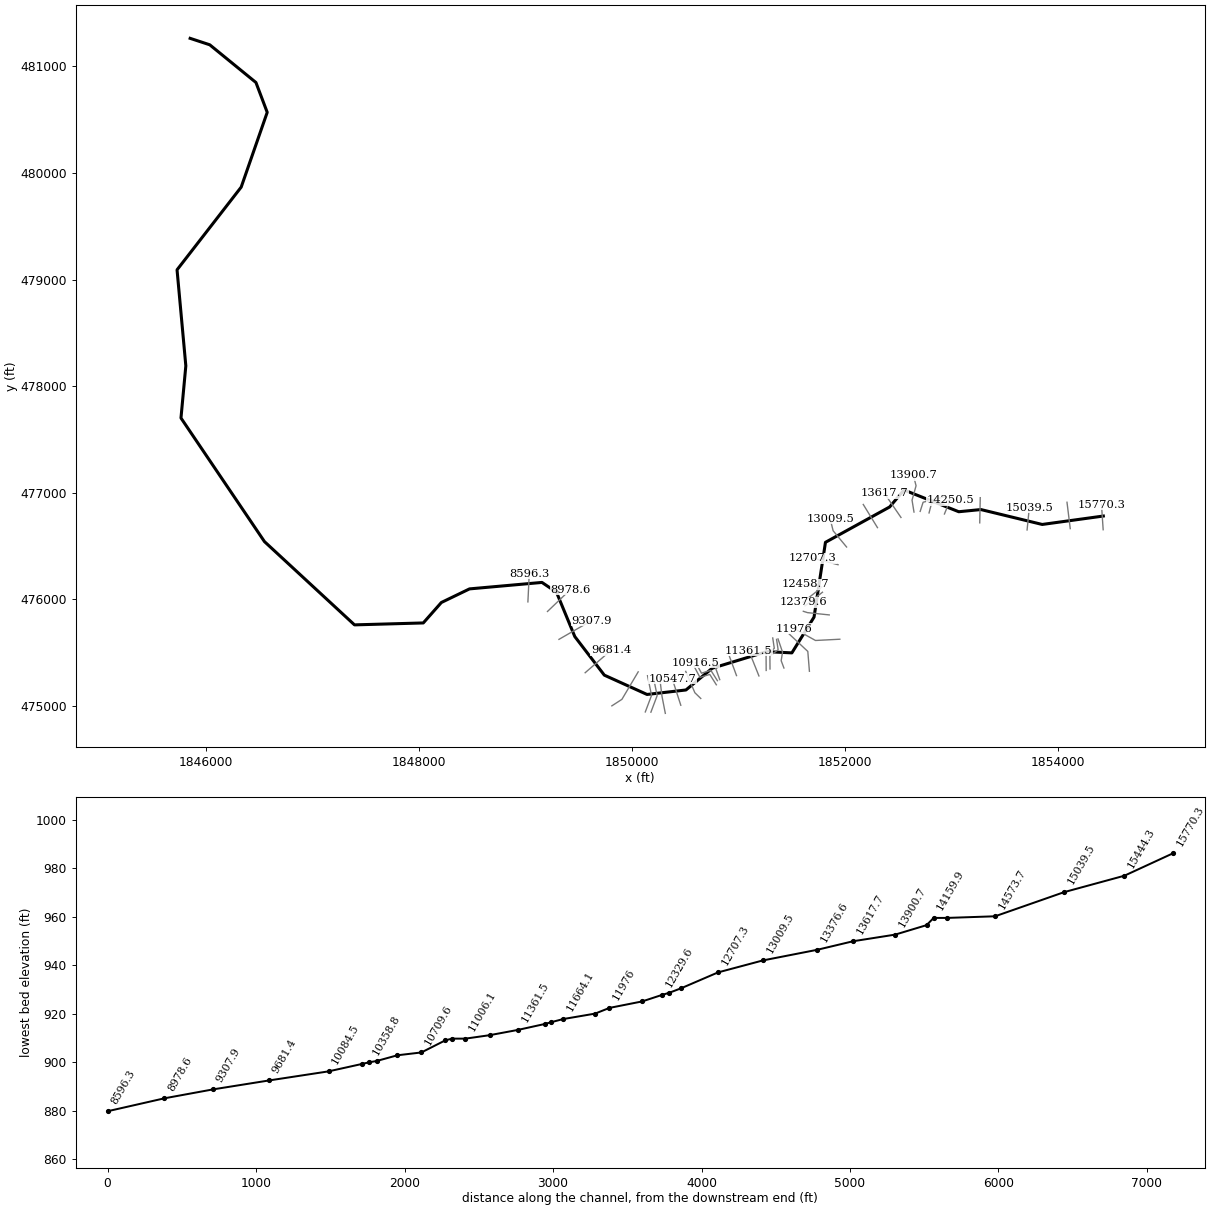
--- CAMPBLSCK.prj (project) ---

Proj Title=CAMPBLSCK
Current Plan=p01
Default Exp/Contr=0,0
English Units
Geom File=g01
Geom File=g02
Flow File=f01
Plan File=p01
BEGIN DESCRIPTION:
Known WS of 793.1' applied to match effective XS BQ.
END DESCRIPTION:
DSS Export Rating Curves= 0
DSS Export Rating Curve Sorted= 0
DSS Export Volume Flow Curves= 0
DXF OffsetX= 0
DXF OffsetY= 0
DXF ScaleX= 0
DXF ScaleY= 0

--- CAMPBLSCK.p01 (plan) ---

Plan Title=Floodplain
Program Version=4.00
Geom File=g01
Flow File=f01
K Sum by GR=0
Std Step Tol=0.01
Critical Tol=0.01
Num of Std Step Trials=20
Max Error Tol=0.3
Flow Tol Ratio=0.001
Split Flow NTrial=30
Split Flow Tol=0.02
Split Flow Ratio=0.02
Log Output Level=0
Friction Slope Method=1
Unsteady Friction Slope Method=2
Unsteady Bridges Friction Slope Method=1
Global Log Level=0
CheckData=False
Run HTab=0
Run UNet=0
Run PostProcess=0
UNET Theta=0
UNET Theta Warmup=0
UNET ZTol=0
UNET ZSATol=0
UNET MxIter=0
UNET MaxInSteps=0
UNET DtIC=0
UNET DtMin=0
UNET MaxCRTS=0
UNET WFStab=0
UNET SFStab=0
UNET WFX=0
UNET SFX=0
UNET DSS MLevel=0
UNET DZMax Abort=0
UNET Convert EG Bridges=0
UNET Use Existing IB Tables=0
UNET Froude Limit=0
UNET Froude Power=0
Write IC File=0
Echo Input=False
Echo Output=False
Write Detailed=0

--- CAMPBLSCK.f01 (steady flow) ---

Flow Title=NFF Regression Equation
Program Version=4.10
Number of Profiles= 1
Profile Names=P100yr
River Rch & RM=CAMPBLSCK,Main            ,15770.3
863.6914
River Rch & RM=CAMPBLSCK,Main            ,15039.5
932.0407
River Rch & RM=CAMPBLSCK,Main            ,11976
1031.232
River Rch & RM=CAMPBLSCK,Main            ,11361.5
1455.256
River Rch & RM=CAMPBLSCK,Main            ,9681.4
1584.041
River Rch & RM=CAMPBLSCK,Main            ,5968.2
1661.583
River Rch & RM=CAMPBLSCK,Main            ,5739
2109.695
River Rch & RM=CAMPBLSCK,Main            ,3001.4
2312.027
River Rch & RM=CAMPBLSCK,Main            ,601.8
2434.275
Boundary for River Rch & Prof#=CAMPBLSCK,Main            , 1
Up Type= 0
Dn Type= 1
Dn Known WS=793.1
DSS Import GetInterval= 0
DSS Import GetPeak= 0
DSS Import FillOption= 0

--- CAMPBLSCK.g01 (geometry) ---

Geom Title=USGS 10m DEM
Program Version=4.10

River Reach=CAMPBLSCK       ,Main
Reach XY= 30
     1854425.086      476782.412     1853851.318      476703.422
     1853275.797      476843.179     1853067.898       476822.78
     1852554.002      477026.779     1852419.026      476867.484
     1851816.595      476535.887     1851709.407      475834.411
     1851501.452      475499.012     1851264.314      475510.481
      1850753.59      475354.893     1850506.986       475151.07
     1850141.647      475108.994     1849740.705      475290.247
     1849463.657      475651.987     1849291.559      476068.143
     1849155.436      476159.761     1848475.303      476099.126
     1848211.091      475971.528     1848041.453      475779.742
     1847395.789      475761.625      1846550.65      476542.528
     1845766.825      477701.683     1845812.398      478191.049
     1845729.933      479091.657     1846332.146      479867.482
     1846576.415      480568.723     1846470.575      480848.476
     1846037.008      481202.117     1845852.834      481262.718

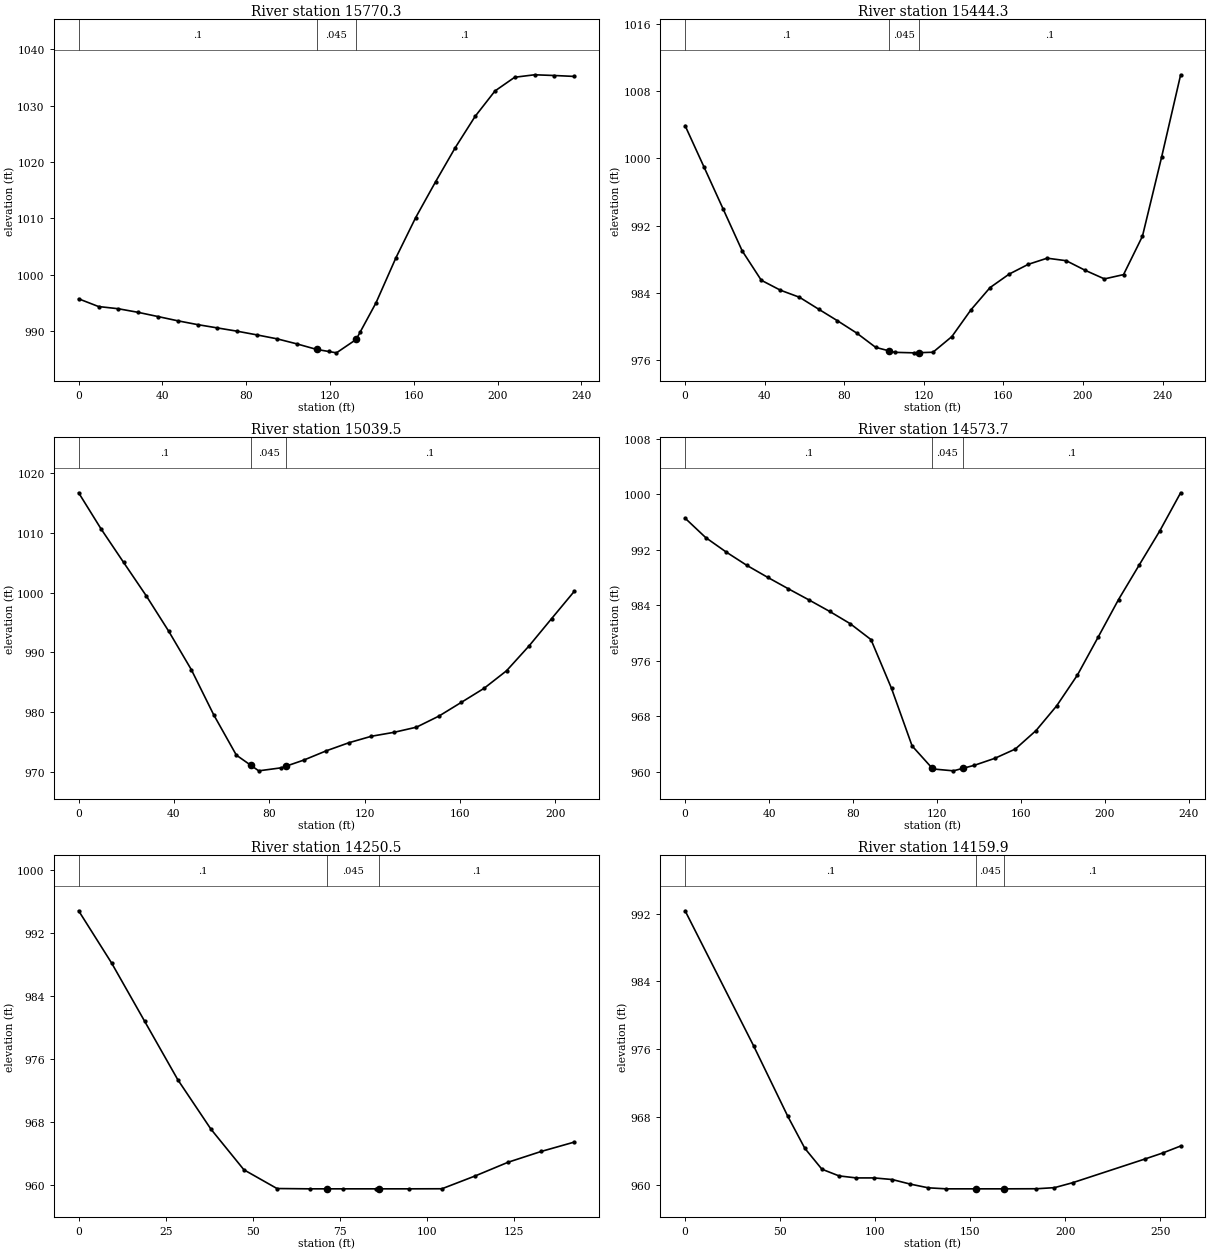
Type RM Length L Ch R = 1 ,15770.3 ,324.5,326.1,326.9
XS GIS Cut Line= 2
     1854423.479      476653.958     1854407.507      476890.069
#Sta/Elev= 28
       0   995.7     9.5  994.33    18.9  993.94    28.4   993.3    37.9  992.55
    47.3   991.8    56.8  991.12    66.3  990.53    75.7  989.95    85.2  989.29
    94.7   988.6   104.1  987.71   113.6  986.72   119.4  986.35   123.1  986.11
   132.5  988.48   134.4  989.78     142     995   151.5 1002.99   160.9  1010.1
   170.4 1016.46   179.8 1022.52   189.3 1028.08   198.8  1032.6   208.2 1035.03
   217.7 1035.47   227.2 1035.34   236.6 1035.18
#Mann= 3 , 0 , 0
       0      .1       0   113.6    .045       0   132.5      .1       0
Bank Sta=113.6,132.5
XS Rating Curve= 0 ,0
Exp/Cntr=0.3,0.1

Type RM Length L Ch R = 1 ,15444.3 ,409.8,404.8,399.4
XS GIS Cut Line= 2
     1854114.451      476664.374     1854083.895      476911.596
#Sta/Elev= 29
       0 1003.88     9.6  998.92    19.2  993.94    28.7  989.01    38.3  985.52
    47.9  984.34    57.5   983.5    67.1  982.09    76.6  980.71    86.2  979.26
    95.8  977.55   102.6  977.13   105.4  976.96     115   976.9   117.6  976.92
   124.6  976.97   134.1  978.83   143.7  982.01   153.3  984.65   162.9  986.25
   172.5  987.41     182  988.14   191.6  987.84   201.2  986.69   210.8  985.68
   220.4  986.19   229.9  990.75   239.5 1000.11   249.1 1009.92
#Mann= 3 , 0 , 0
       0      .1       0   102.6    .045       0   117.6      .1       0
Bank Sta=102.6,117.6
XS Rating Curve= 0 ,0
Exp/Cntr=0.3,0.1

Type RM Length L Ch R = 1 ,15039.5 ,463.9,465.8,467.6
XS GIS Cut Line= 2
     1853709.243      476651.874     1853730.076      476858.819
#Sta/Elev= 25
       0  1016.7     9.4 1010.66    18.9 1005.03    28.4  999.44    37.8  993.53
    47.3  987.09    56.7  979.53    66.2  972.78    72.2   971.1    75.6  970.15
    85.1  970.66    87.2  970.95    94.5  971.95     104  973.51   113.4  974.85
   122.9  975.94   132.4   976.6   141.8  977.46   151.3  979.33   160.7  981.63
   170.2  983.97   179.6   986.9   189.1  991.08   198.5  995.62     208 1000.18
#Mann= 3 , 0 , 0
       0      .1       0    72.2    .045       0    87.2      .1       0
Bank Sta=72.2,87.2
XS Rating Curve= 0 ,0
Exp/Cntr=0.3,0.1

Type RM Length L Ch R = 1 ,14573.7 ,331.4,323.2,314.6
XS GIS Cut Line= 2
     1853264.798      476718.541     1853269.659      476954.652
#Sta/Elev= 27
       0  996.57     9.8  993.78    19.7  991.67    29.5  989.76    39.4  988.04
    49.2   986.4      59   984.8    68.9  983.14    78.7  981.37    88.6  979.08
    98.4  972.04   108.2  963.76   117.5  960.64   118.1  960.44   127.9  960.17
   132.5  960.54   137.8  960.96   147.6  961.97   157.4  963.31   167.3  965.98
   177.1  969.53     187  973.97   196.8  979.39   206.6  984.85   216.5  989.85
   226.3  994.76   236.2 1000.23
#Mann= 3 , 0 , 0
       0      .1       0   117.5    .045       0   132.5      .1       0
Bank Sta=117.5,132.5
XS Rating Curve= 0 ,0
Exp/Cntr=0.3,0.1

Type RM Length L Ch R = 1 ,14250.5 ,118.3,90.6,60.5
XS GIS Cut Line= 2
     1852933.479       476801.55     1852986.951      476933.495
#Sta/Elev= 18
       0  994.85     9.5  988.19      19  980.78    28.5  973.37      38   967.1
    47.5  961.92      57  959.54    66.4   959.5    71.4   959.5    75.9   959.5
    85.4   959.5    86.4   959.5    94.9   959.5   104.4  959.51   113.9  961.13
   123.4  962.88   132.9  964.25   142.4  965.44
#Mann= 3 , 0 , 0
       0      .1       0    71.4    .045       0    86.4      .1       0
Bank Sta=71.4,86.4
XS Rating Curve= 0 ,0
Exp/Cntr=0.3,0.1

Type RM Length L Ch R = 1 ,14159.9 ,64.4,47.5,53.8
XS GIS Cut Line= 3
     1852788.998      476811.529     1852811.483      476898.733
     1852979.285      476930.164
#Sta/Elev= 20
       0  992.35      36  976.42      54  968.09      63  964.29      72  961.82
      81  961.03    90.1  960.79    99.5  960.79     109   960.6   118.5  960.06
     128  959.62   137.5   959.5     153   959.5     168   959.5   184.9  959.51
   194.4  959.64   203.9  960.22   241.8  963.01   251.3  963.73   260.8  964.56
#Mann= 3 , 0 , 0
       0      .1       0     153    .045       0     168      .1       0
Bank Sta=153,168
XS Rating Curve= 0 ,0
Exp/Cntr=0.3,0.1

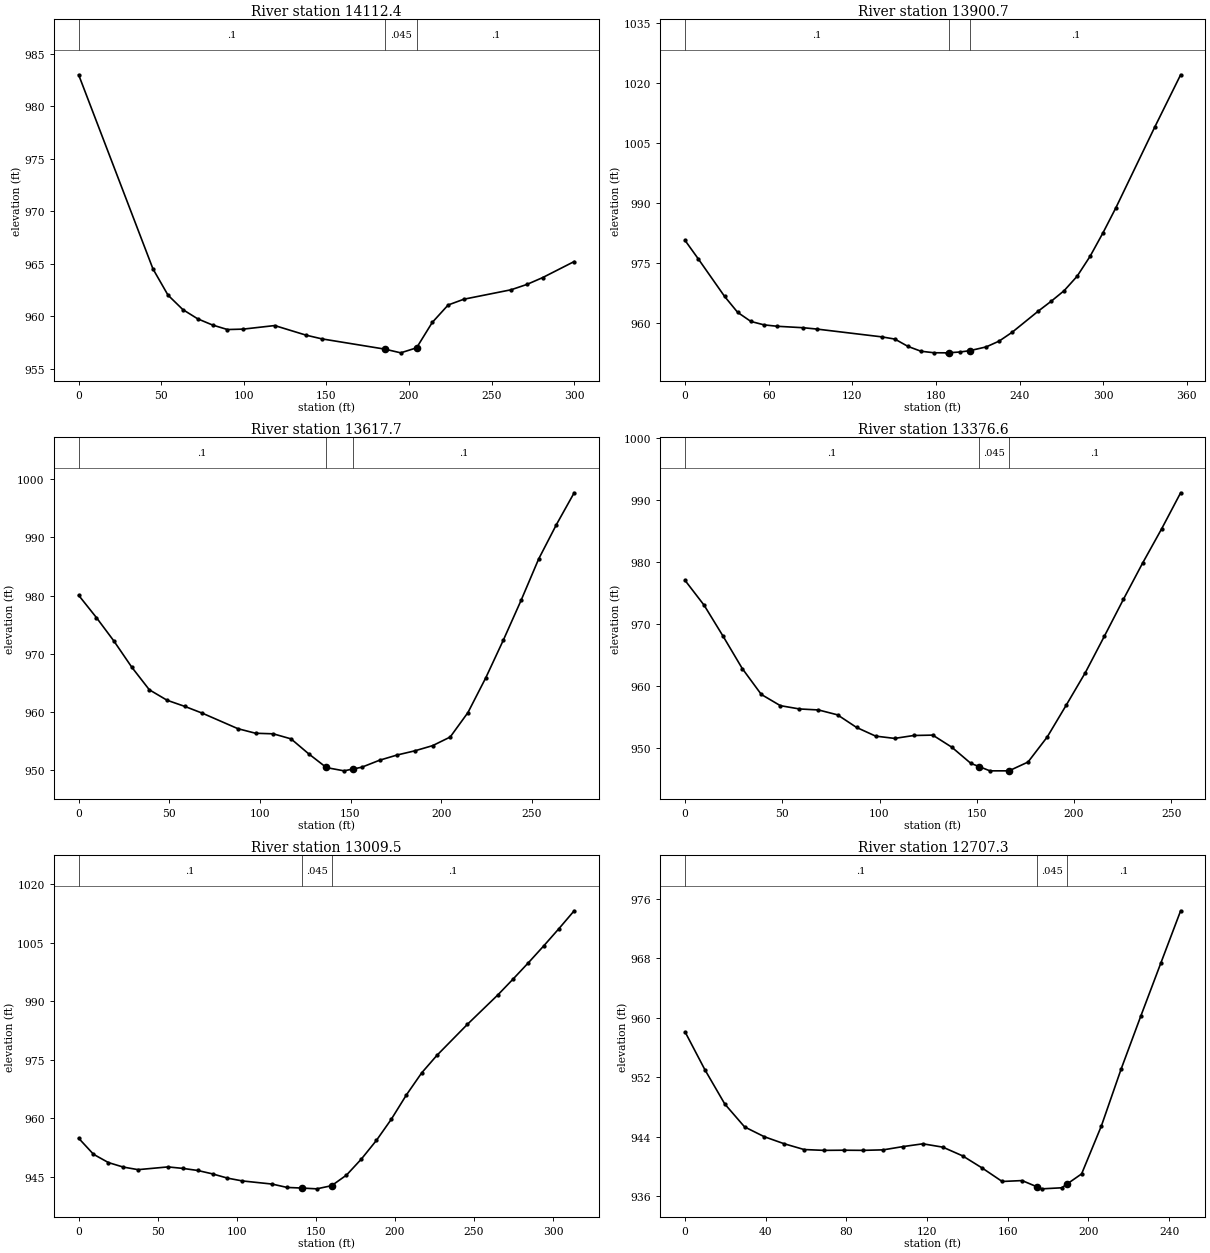
Type RM Length L Ch R = 1 ,14112.4 ,163.8,211.7,238.1
XS GIS Cut Line= 3
     1852705.689      476826.103     1852733.271      476911.878
     1852936.786      476963.155
#Sta/Elev= 21
       0  983.02      45  964.52    54.1  962.02    63.1  960.64    72.1  959.76
    81.1  959.17    90.1  958.74    99.6  958.78   118.7  959.12   137.8   958.2
   147.3  957.85   185.5  956.87     195  956.52   204.6     957   214.1  959.42
   223.7  961.08   233.2  961.63   261.8  962.53   271.4  963.04   280.9  963.69
     300  965.22
#Mann= 3 , 0 , 0
       0      .1       0   185.5    .045       0   204.6      .1       0
Bank Sta=185.5,204.6
XS Rating Curve= 0 ,0
Exp/Cntr=0.3,0.1

Type RM Length L Ch R = 1 ,13900.7 ,262.9,282.9,302.2
XS GIS Cut Line= 4
     1852647.645      476819.745     1852629.312      476931.411
      1852667.09      477066.411     1852641.534        477165.3
#Sta/Elev= 30
       0  980.64     9.4  976.08    28.3   966.7    37.7  962.71    47.2  960.44
    56.6  959.59      66  959.24    84.9  958.87    94.3  958.55   141.2  956.59
   150.5  956.04   159.9  954.21   169.2  953.01   178.6  952.63   187.9  952.61
   189.4  952.64   197.3  952.82   204.4  953.16     216  954.09   225.3  955.54
   234.7  957.76   253.4  963.03   262.6  965.47   271.9  968.11   281.2   971.7
   290.5  976.67   299.8  982.55   309.1  988.84   336.9 1008.91   355.5 1021.98
#Mann= 3 , 0 , 0
       0      .1       0   189.4    .045       0   204.4      .1       0
Bank Sta=189.4,204.4
XS Rating Curve= 0 ,0
Exp/Cntr=0.3,0.1

Type RM Length L Ch R = 1 ,13617.7 ,242,241.1,240.4
XS GIS Cut Line= 2
     1852525.587      476769.015     1852370.815      476994.363
#Sta/Elev= 30
       0  980.05     9.8  976.22    19.5  972.17    29.3   967.7      39  963.81
    48.8  962.01    58.6  960.95    68.3  959.78    87.9  957.12    97.6  956.34
   107.4  956.24   117.2  955.37   126.9  952.81   136.3  950.54   136.7  950.44
   146.4  949.88   151.3  950.19   156.2   950.5     166   951.7   175.7   952.6
   185.5  953.32   195.3  954.21     205  955.69   214.8   959.9   224.6  965.85
   234.3  972.33   244.1  979.17   253.8  986.28   263.6  992.19   273.4  997.66
#Mann= 3 , 0 , 0
       0      .1       0   136.3    .045       0   151.3      .1       0
Bank Sta=136.3,151.3
XS Rating Curve= 0 ,0
Exp/Cntr=0.3,0.1

Type RM Length L Ch R = 1 ,13376.6 ,363.5,367,369.9
XS GIS Cut Line= 2
     1852304.868      476673.633     1852171.534      476890.856
#Sta/Elev= 29
       0  977.06     9.8  973.06    19.6  968.04    29.4  962.86    39.2  958.68
      49  956.87    58.8  956.34    68.6  956.18    78.4  955.39    88.2  953.36
      98  951.96   107.8  951.59   117.6  952.06   127.4  952.12   137.2  950.17
     147  947.56   151.2  947.05   156.8  946.36   166.2  946.36   166.6  946.36
   176.4  947.78   186.3  951.83   196.1  956.98   205.9  962.21   215.7  968.09
   225.5  974.04   235.3  979.84   245.1  985.37   254.9   991.2
#Mann= 3 , 0 , 0
       0      .1       0   151.2    .045       0   166.6      .1       0
Bank Sta=151.2,166.6
XS Rating Curve= 0 ,0
Exp/Cntr=0.3,0.1

Type RM Length L Ch R = 1 ,13009.5 ,288.1,302.2,316.4
XS GIS Cut Line= 3
     1852014.868      476491.967     1851888.757      476644.189
     1851860.423      476756.411
#Sta/Elev= 30
       0  954.94     9.4  950.82    18.8   948.7    28.2  947.54    37.6  946.88
    56.5  947.58    65.9   947.2    75.3  946.67    84.7  945.79    94.1  944.71
   103.5  943.99   122.4  943.18   131.8  942.32   141.2  942.16   150.6  941.96
     160  942.77   169.4  945.48   178.8  949.59   188.3  954.36   197.7  959.77
   207.3  966.04     217  971.71   226.6  976.18   245.9  984.14   265.2   991.7
   274.8  995.75   284.5  999.94   294.1 1004.22   303.8 1008.68   313.4 1013.24
#Mann= 3 , 0 , 0
       0      .1       0   141.2    .045       0     160      .1       0
Bank Sta=141.2,160
XS Rating Curve= 0 ,0
Exp/Cntr=0.3,0.1

Type RM Length L Ch R = 1 ,12707.3 ,246.6,248.6,250.4
XS GIS Cut Line= 2
     1851934.677       476325.89     1851696.829      476387.522
#Sta/Elev= 28
       0   958.1     9.8  953.03    19.7  948.41    29.5  945.34    39.3  944.02
    49.1  943.08      59   942.3    68.8  942.19    78.6  942.21    88.4  942.19
    98.3  942.26   108.1   942.7   117.9  943.07   127.8  942.62   137.6  941.45
   147.4   939.8   157.2  938.01   167.1  938.13   174.5  937.29   176.9  937.02
   186.7  937.16   189.5  937.69   196.6  939.03   206.4  945.47   216.2  953.12
     226  960.27   235.9  967.37   245.7  974.38
#Mann= 3 , 0 , 0
       0      .1       0   174.5    .045       0   189.5      .1       0
Bank Sta=174.5,189.5
XS Rating Curve= 0 ,0
Exp/Cntr=0.3,0.1

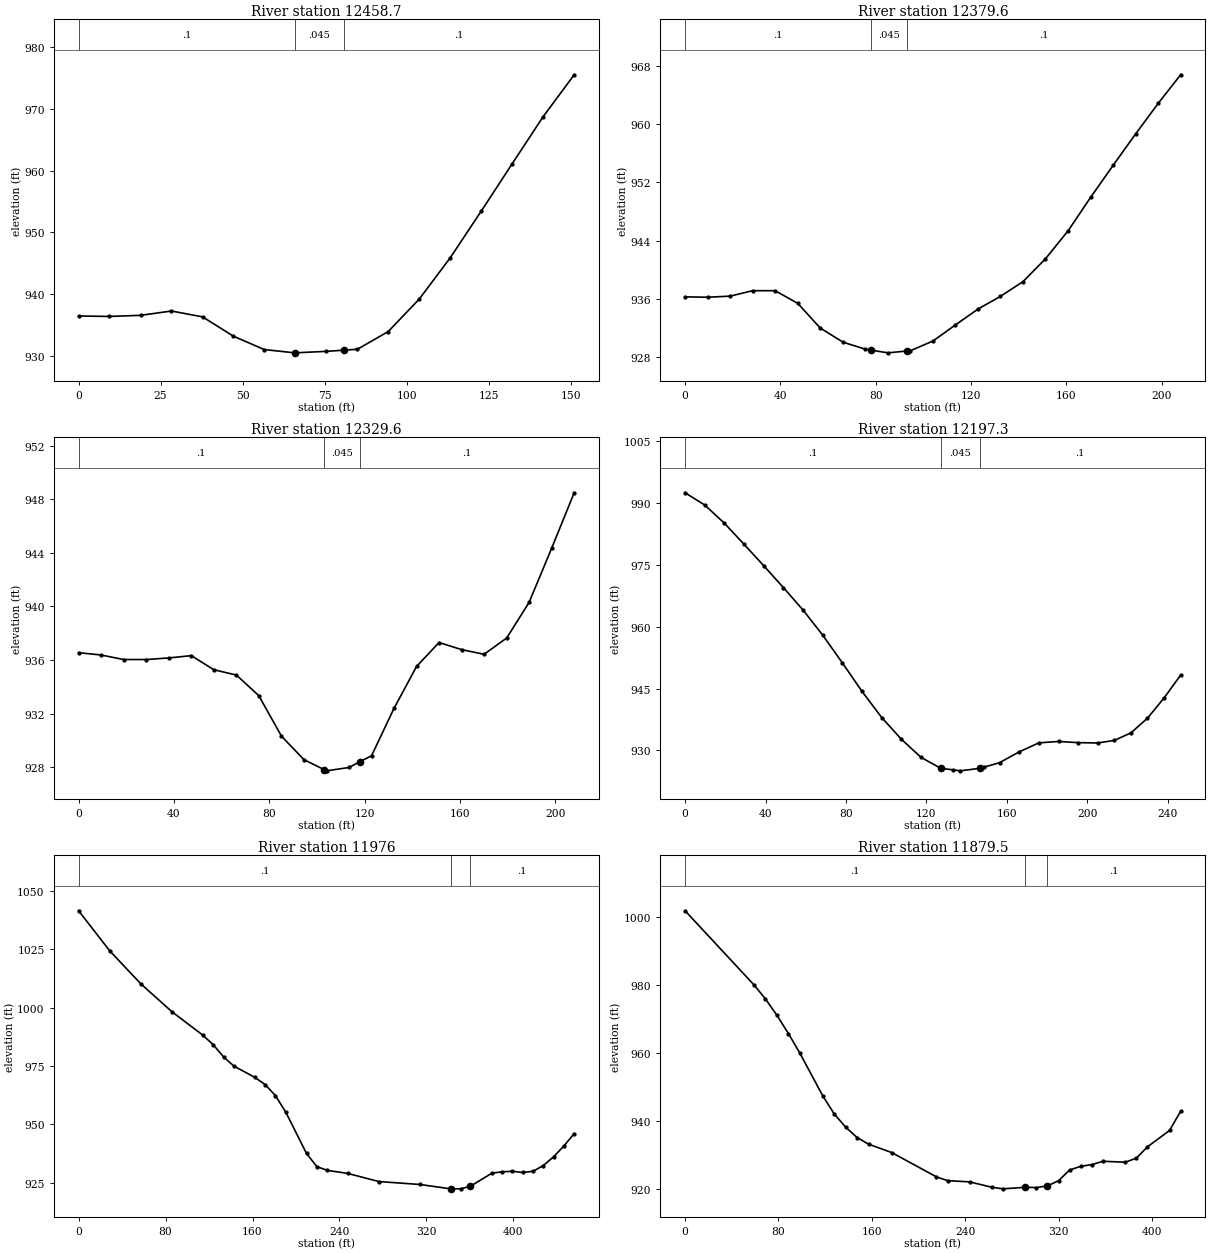
Type RM Length L Ch R = 1 ,12458.7 ,57.1,79.2,100.9
XS GIS Cut Line= 2
     1851779.659      476116.249      1851630.77      476141.805
#Sta/Elev= 18
       0  936.44     9.4  936.37    18.9  936.55    28.3  937.25    37.8   936.3
    47.2  933.17    56.6     931    65.9  930.47    75.5  930.71    80.9   930.9
      85  931.05    94.4  933.92   103.9  939.21   113.3  945.87   122.7  953.39
   132.2  961.12   141.6  968.72   151.1  975.54
#Mann= 3 , 0 , 0
       0      .1       0    65.9    .045       0    80.9      .1       0
Bank Sta=65.9,80.9
XS Rating Curve= 0 ,0
Exp/Cntr=0.3,0.1

Type RM Length L Ch R = 1 ,12379.6 ,51.1,50,50.6
XS GIS Cut Line= 2
     1851769.029      476102.485     1851605.183      475974.446
#Sta/Elev= 25
       0   936.3     9.4  936.25    18.9   936.4    28.4  937.15    37.8  937.14
    47.3   935.4    56.7  932.03    66.2   930.1    75.6  929.13    78.1     929
    85.1  928.63    93.1  928.88    94.5  928.92     104  930.25   113.4  932.45
   122.9  934.63   132.3  936.37   141.8   938.4   151.2  941.52   160.7  945.36
   170.1  949.92   179.6  954.33     189  958.62   198.5  962.82   207.9  966.73
#Mann= 3 , 0 , 0
       0      .1       0    78.1    .045       0    93.1      .1       0
Bank Sta=78.1,93.1
XS Rating Curve= 0 ,0
Exp/Cntr=0.3,0.1

Type RM Length L Ch R = 1 ,12329.6 ,151.5,132.3,111
XS GIS Cut Line= 2
      1851788.56      476067.762     1851624.715      475939.724
#Sta/Elev= 25
       0  936.54     9.4  936.37    18.9  936.03    28.4  936.03    37.8  936.15
    47.3  936.32    56.7  935.27    66.2  934.87    75.6  933.33    85.1  930.31
    94.5  928.56   102.9  927.82     104  927.72   113.4  927.97   117.9  928.39
   122.9  928.85   132.3  932.38   141.8  935.52   151.2   937.3   160.7  936.77
   170.1  936.42   179.6  937.64     189   940.3   198.5  944.36   207.9  948.48
#Mann= 3 , 0 , 0
       0      .1       0   102.9    .045       0   117.9      .1       0
Bank Sta=102.9,117.9
XS Rating Curve= 0 ,0
Exp/Cntr=0.3,0.1

Type RM Length L Ch R = 1 ,12197.3 ,230.4,221.3,212.2
XS GIS Cut Line= 3
     1851852.188      475854.936     1851648.022      475876.463
     1851608.785      475888.963
#Sta/Elev= 29
       0  992.52     9.8  989.54    19.6  985.11    29.3  980.04    39.1  974.83
    48.9  969.52    58.7  964.05    68.4  958.02    78.2  951.28      88  944.34
    97.8     938   107.5  932.77   117.3  928.35   127.1  925.69   133.5  925.28
   136.9  925.06   146.6  925.67   148.5  925.93   156.4  927.03   166.2  929.67
     176  931.85   185.8  932.19   195.5   931.9   205.3  931.82   213.5  932.44
   221.8  934.28     230  937.84   238.2   942.7   246.5  948.29
#Mann= 3 , 0 , 0
       0      .1       0   127.1    .045       0   146.6      .1       0
Bank Sta=127.1,146.6
XS Rating Curve= 0 ,0
Exp/Cntr=0.3,0.1

Type RM Length L Ch R = 1 ,11976   ,102,96.5,91
XS GIS Cut Line= 3
     1851951.494       475627.05     1851723.022      475615.245
     1851524.411      475725.662
#Sta/Elev= 30
       0  1041.6    28.6 1024.43    57.2 1010.28    85.8  998.34   114.4  988.21
   123.9  984.16   133.4  978.92     143  974.96     162  970.22   171.6  967.08
   181.1  962.34   190.6  955.26   209.7  937.54   219.2   931.9   228.8  930.29
   247.7  928.98   276.1  925.51     314  924.24   342.4  922.37   351.9   922.4
   360.5  923.49   380.3  929.08   389.7  929.68   399.2  929.88   408.7  929.39
   418.1  929.89   427.6  932.35   437.1  936.12   446.6  940.79     456  946.04
#Mann= 3 , 0 , 0
       0      .1       0   342.4    .045       0   360.5      .1       0
Bank Sta=342.4,360.5
XS Rating Curve= 0 ,0
Exp/Cntr=0.3,0.1

Type RM Length L Ch R = 1 ,11879.5 ,237.6,215.4,192.7
XS GIS Cut Line= 3
     1851666.077      475326.356      1851650.92      475512.595
     1851477.189      475674.967
#Sta/Elev= 30
       0 1001.97      59  980.14    68.8  976.02    78.7  971.16    88.5   965.8
    98.3  960.04     118   947.4   127.8  942.08   137.7  938.16   147.5   935.1
   157.4  933.16     177  930.72   215.4  923.54   224.9  922.44   243.9  922.07
     263  920.47   272.5  920.02   291.5  920.48     301   920.4   310.5  920.89
     320  922.42   329.5  925.58     339  926.65   348.6  927.17   358.1  928.14
   377.1  927.87   386.6  929.04   396.1  932.38   415.1  937.23   424.6  942.88
#Mann= 3 , 0 , 0
       0      .1       0   291.5    .045       0   310.5      .1       0
Bank Sta=291.5,310.5
XS Rating Curve= 0 ,0
Exp/Cntr=0.3,0.1

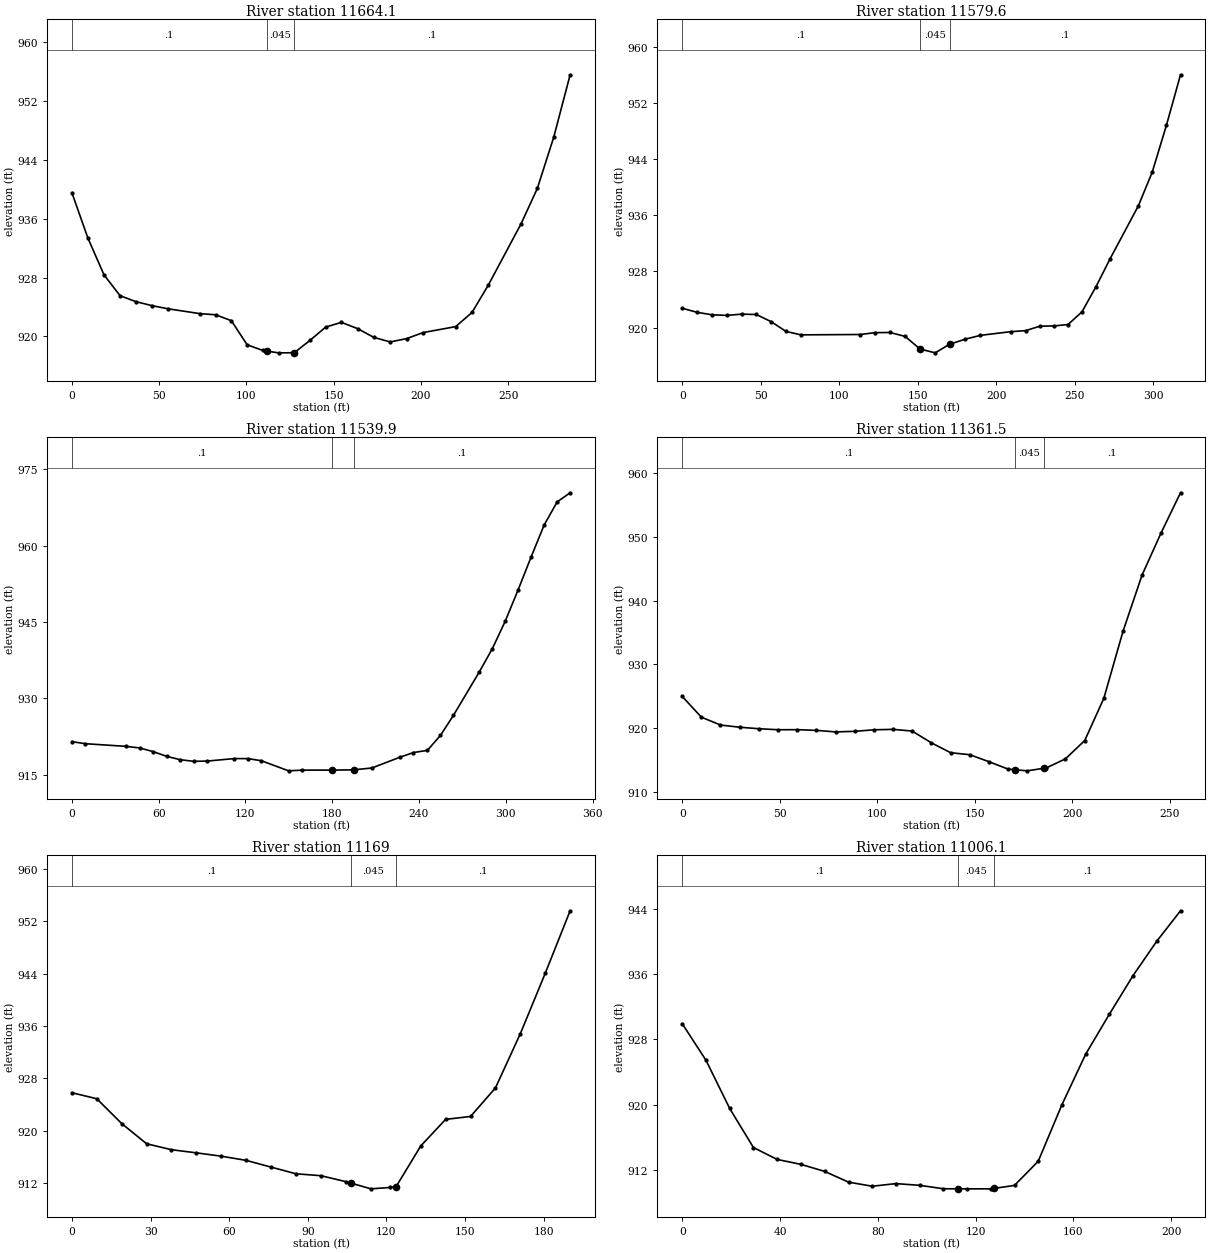
Type RM Length L Ch R = 1 ,11664.1 ,104.2,84.5,64.8
XS GIS Cut Line= 4
     1851426.784      475356.961      1851400.88      475425.705
     1851413.728      475505.566     1851371.391      475629.662
#Sta/Elev= 30
       0  939.51     9.2  933.34    18.4  928.36    27.6  925.53    36.7  924.72
    45.9  924.18    55.1  923.75    73.5  923.09    82.4  922.94    91.4  922.13
   100.4  918.87   109.4  918.09   111.6  918.01   118.4  917.77   127.4  917.78
   136.4  919.46   145.4  921.26   154.4  921.91   163.7  921.06   173.1  919.86
   182.4  919.25   191.8   919.7   201.2  920.52   219.9  921.33   229.3  923.26
   238.6  926.96   257.4   935.3   266.7  940.09   276.1  947.05   285.5  955.53
#Mann= 3 , 0 , 0
       0      .1       0   111.6    .045       0   127.4      .1       0
Bank Sta=111.6,127.4
XS Rating Curve= 0 ,0
Exp/Cntr=0.3,0.1

Type RM Length L Ch R = 1 ,11579.6 ,45.8,39.8,39.7
XS GIS Cut Line= 4
     1851296.115      475347.966     1851295.095      475470.725
     1851372.338      475527.873     1851357.662      475625.401
#Sta/Elev= 30
       0  922.76     9.4  922.18    18.9  921.83    28.3  921.74    37.8  921.92
    47.2  921.87    56.7  920.84    66.1  919.46    75.6  918.97   113.3  919.02
   122.8  919.28   132.4  919.31     142  918.75   151.6  916.94   161.2  916.41
   170.3  917.63   180.4  918.36     190   918.9   209.2  919.42   218.8  919.57
   227.8   920.2   236.8  920.24   245.8  920.44   254.7  922.24   263.7  925.85
   272.6  929.79   290.6  937.32   299.5  942.15   308.5  948.79   317.5     956
#Mann= 3 , 0 , 0
       0      .1       0   151.6    .045       0   170.3      .1       0
Bank Sta=151.6,170.3
XS Rating Curve= 0 ,0
Exp/Cntr=0.3,0.1

Type RM Length L Ch R = 1 ,11539.9 ,140.1,178.3,210.2
XS GIS Cut Line= 4
     1851260.133      475334.236     1851259.114      475483.981
     1851336.357      475541.129      1851321.68      475638.657
#Sta/Elev= 30
       0  921.46     9.4  921.06    37.4  920.54    46.8  920.23    56.2  919.51
    65.5  918.58    74.9  917.92    84.2   917.6    93.6  917.65   112.3  918.14
   121.7  918.13     131  917.72   149.8  915.73   159.4  915.87   179.9  915.87
   194.9  915.93   207.4  916.29   226.6  918.38   236.2  919.33   245.8  919.75
   254.8  922.68   263.8  926.63   281.7  935.16   290.7  939.73   299.6  945.12
   308.6  951.33   317.6  957.81   326.5  964.01   335.5  968.57   344.5  970.37
#Mann= 3 , 0 , 0
       0      .1       0   179.9    .045       0   194.9      .1       0
Bank Sta=179.9,194.9
XS Rating Curve= 0 ,0
Exp/Cntr=0.3,0.1

Type RM Length L Ch R = 1 ,11361.5 ,193.1,192.5,191.8
XS GIS Cut Line= 2
     1851192.047      475282.799     1851097.015      475519.941
#Sta/Elev= 29
       0  924.97     9.8  921.73    19.6   920.5    29.5  920.15    39.3  919.92
    49.1  919.76      59  919.77    68.8  919.66    78.6  919.42    88.4  919.51
    98.3  919.75   108.1  919.82   117.9  919.55   127.7  917.72   137.6  916.16
   147.4  915.85   157.2  914.76     167   913.6   170.4   913.5   176.9  913.32
   185.4  913.72   186.7  913.78   196.5   915.2   206.4  918.07   216.2   924.7
     226  935.17   235.8  944.01   245.6  950.64   255.5  956.89
#Mann= 3 , 0 , 0
       0      .1       0   170.4    .045       0   185.4      .1       0
Bank Sta=170.4,185.4
XS Rating Curve= 0 ,0
Exp/Cntr=0.3,0.1

Type RM Length L Ch R = 1 ,11169   ,163,162.9,162.8
XS GIS Cut Line= 2
     1850981.607      475286.061     1850915.773      475464.394
#Sta/Elev= 23
       0  925.81     9.5  924.89      19   921.1    28.5  918.01      38   917.1
    47.5  916.62      57  916.11    66.5  915.47      76  914.44    85.5  913.42
      95  913.13   104.6  912.21   106.5  911.99   114.1  911.12   121.5  911.33
   123.6  911.39   133.1  917.67   142.6  921.74   152.1  922.18   161.6  926.54
   171.1  934.83   180.6  944.06   190.1  953.62
#Mann= 3 , 0 , 0
       0      .1       0   106.5    .045       0   123.6      .1       0
Bank Sta=106.5,123.6
XS Rating Curve= 0 ,0
Exp/Cntr=0.3,0.1

Type RM Length L Ch R = 1 ,11006.1 ,47.4,89.6,128.7
XS GIS Cut Line= 2
     1850824.242      475248.148     1850755.343      475440.002
#Sta/Elev= 24
       0  929.91     9.7  925.44    19.4  919.54    29.1  914.76    38.8   913.3
    48.5   912.7    58.2  911.84      68  910.52    77.7  910.02    87.4  910.34
    97.1  910.13   106.8  909.71   112.7   909.7   116.5   909.7   126.2   909.7
   127.7  909.76   135.9  910.12   145.6  913.08   155.3     920     165  926.18
   174.7  931.08   184.4  935.81   194.1  940.02   203.8  943.74
#Mann= 3 , 0 , 0
       0      .1       0   112.7    .045       0   127.7      .1       0
Bank Sta=112.7,127.7
XS Rating Curve= 0 ,0
Exp/Cntr=0.3,0.1

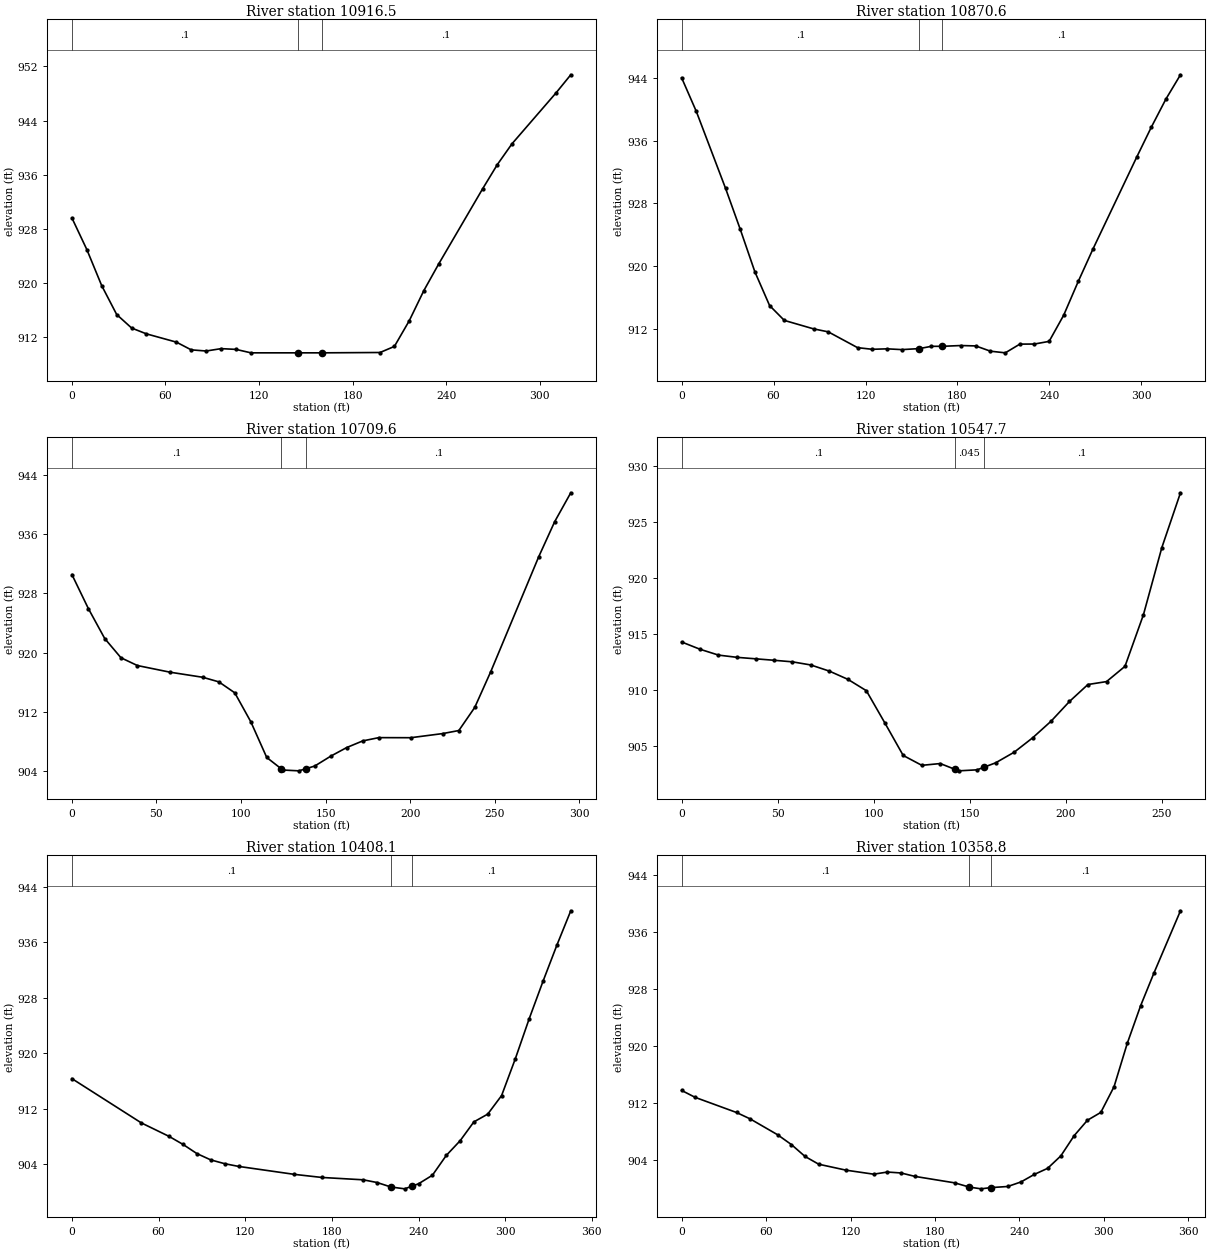
Type RM Length L Ch R = 1 ,10916.5 ,49.9,45.9,58.5
XS GIS Cut Line= 4
     1850802.318      475238.088     1850740.869      475335.042
     1850652.606      475308.868     1850598.888      475408.335
#Sta/Elev= 24
       0  929.61     9.6  924.93    19.1  919.62    28.7  915.36    38.3  913.36
    47.8   912.5      67  911.28    76.5  910.14    86.1  909.97    95.7  910.32
   105.2  910.21   114.8   909.7   145.2   909.7   160.2   909.7   197.6  909.75
   206.8  910.65   216.3  914.43   225.7   918.9   235.1  922.78   263.4  933.93
   272.8  937.49   282.2  940.56   310.5  948.09   319.9  950.75
#Mann= 3 , 0 , 0
       0      .1       0   145.2    .045       0   160.2      .1       0
Bank Sta=145.2,160.2
XS Rating Curve= 0 ,0
Exp/Cntr=0.3,0.1

Type RM Length L Ch R = 1 ,10870.6 ,197.8,161,109
XS GIS Cut Line= 4
     1850792.219      475199.855     1850730.769      475296.809
     1850638.372      475269.409     1850584.821      475370.462
#Sta/Elev= 30
       0     944     9.6  939.71    28.7  929.91    38.3  924.69    47.8   919.3
    57.4  915.01      67  913.12    86.1  912.04    95.7  911.66   114.8  909.65
   124.4  909.44   134.1   909.5   143.7   909.4   155.1  909.53     163  909.82
   170.1  909.82   182.2  909.92   191.9  909.87   201.5   909.2   211.2  908.99
   220.7   910.1   230.2  910.11   239.8  910.45   249.3  913.78   258.8  918.08
   268.3  922.16   296.9  933.88   306.5  937.72     316  941.29   325.5  944.38
#Mann= 3 , 0 , 0
       0      .1       0   155.1    .045       0   170.1      .1       0
Bank Sta=155.1,170.1
XS Rating Curve= 0 ,0
Exp/Cntr=0.3,0.1

Type RM Length L Ch R = 1 ,10709.6 ,163.9,161.9,160.8
XS GIS Cut Line= 3
     1850646.121      475071.408     1850590.634      475125.367
     1850504.905      475325.367
#Sta/Elev= 28
       0  930.54     9.7  925.95    19.4  921.89      29  919.29    38.7  918.24
      58  917.34    77.4  916.65    86.9  916.03    96.3  914.55   105.8  910.63
   115.2  905.81   123.6  904.31   124.7  904.11   134.2     904   138.6   904.3
   143.6  904.65   153.1  905.99   162.5  907.15     172  908.05   181.5  908.49
   200.4  908.48   219.3  909.04   228.8  909.45   238.2  912.57   247.7  917.42
   276.1  932.98   285.5   937.7     295   941.6
#Mann= 3 , 0 , 0
       0      .1       0   123.6    .045       0   138.6      .1       0
Bank Sta=123.6,138.6
XS Rating Curve= 0 ,0
Exp/Cntr=0.3,0.1

Type RM Length L Ch R = 1 ,10547.7 ,143.4,139.5,134.4
XS GIS Cut Line= 2
     1850458.655      475007.728     1850378.759      475254.881
#Sta/Elev= 30
       0  914.31     9.6  913.66    19.2  913.14    28.9  912.94    38.5  912.81
    48.1  912.68    57.7  912.54    67.3  912.26      77  911.71    86.6  910.98
    96.2  909.97   105.8  907.11   115.4   904.2   125.1  903.32   134.7  903.48
   142.4  902.96   144.3  902.83   153.9  902.92   157.4  903.15   163.5  903.54
   173.2  904.49   182.8  905.77   192.4  907.25     202  909.01   211.6  910.52
   221.3  910.78   230.9  912.14   240.5  916.73   250.1  922.72   259.8   927.6
#Mann= 3 , 0 , 0
       0      .1       0   142.4    .045       0   157.4      .1       0
Bank Sta=142.4,157.4
XS Rating Curve= 0 ,0
Exp/Cntr=0.3,0.1

Type RM Length L Ch R = 1 ,10408.1 ,47.4,49.3,50.9
XS GIS Cut Line= 3
     1850313.364      474931.582     1850282.114      475091.999
     1850259.891      475272.554
#Sta/Elev= 27
       0  916.34    48.1  909.96    67.3  908.02    76.9  906.87    86.5  905.55
    96.1  904.64   105.8  904.09   115.4   903.7   153.8  902.56     173  902.11
   201.7  901.77   211.3  901.38   220.8  900.74   230.4  900.47   235.8  900.88
     240   901.2   249.6  902.43   259.2  905.28   268.8   907.4   278.3  910.11
   287.9  911.23   297.5   913.9     307   919.2   316.6  924.96   326.2  930.37
   335.8  935.57   345.4  940.51
#Mann= 3 , 0 , 0
       0      .1       0   220.8    .045       0   235.8      .1       0
Bank Sta=220.8,235.8
XS Rating Curve= 0 ,0
Exp/Cntr=0.3,0.1

Type RM Length L Ch R = 1 ,10358.8 ,52.5,52,52.2
XS GIS Cut Line= 3
     1850178.077      474942.872     1850236.671       475097.82
     1850198.911      475282.716
#Sta/Elev= 30
       0  913.78     9.7   912.8      39  910.68    48.7  909.78    68.2  907.55
      78  906.17    87.7   904.5    97.4  903.41   116.9  902.57   136.4  902.01
   146.2  902.31   155.9  902.18   165.7   901.7     194  900.79   204.5  900.19
   212.8  899.95   219.5  900.12   231.7  900.28   241.1  900.92   250.6  901.98
     260  902.83   269.4  904.58   278.9  907.43   288.3  909.59   297.8  910.69
   307.2   914.3   316.6   920.4   326.1  925.69   335.5  930.26   354.4  939.03
#Mann= 3 , 0 , 0
       0      .1       0   204.5    .045       0   219.5      .1       0
Bank Sta=204.5,219.5
XS Rating Curve= 0 ,0
Exp/Cntr=0.3,0.1

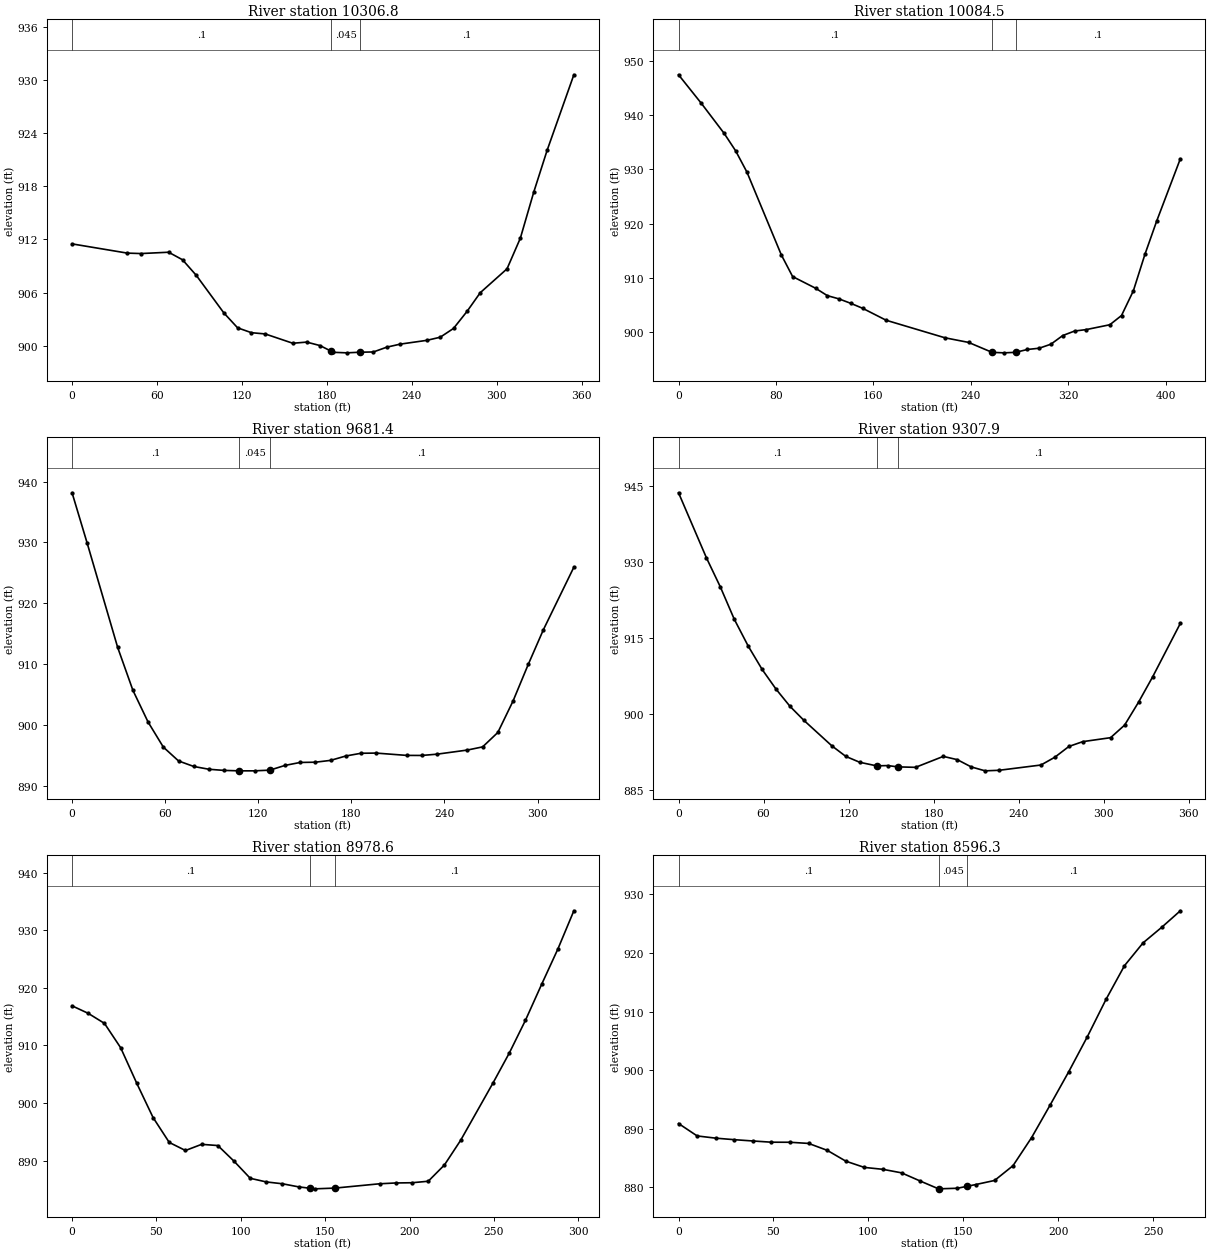
Type RM Length L Ch R = 1 ,10306.8 ,238.8,222.3,205.1
XS GIS Cut Line= 3
     1850125.357       474944.95      1850183.95      475099.898
      1850146.19      475284.794
#Sta/Elev= 30
       0   911.5      39  910.46    48.7  910.41    68.2  910.56      78  909.71
    87.7  907.96   107.2  903.72   116.9  902.04   126.7  901.49   136.4  901.35
   155.9   900.3   165.7  900.43   175.1  900.04   183.2  899.39   184.5  899.28
     194  899.22   203.4  899.29   212.8  899.32   222.3  899.86   231.7   900.2
   250.6  900.63     260  900.98   269.4  901.97   278.9  903.88   288.3     906
   307.2  908.69   316.6  912.14   326.1  917.35   335.5  922.04   354.4  930.56
#Mann= 3 , 0 , 0
       0      .1       0   183.2    .045       0   203.4      .1       0
Bank Sta=183.2,203.4
XS Rating Curve= 0 ,0
Exp/Cntr=0.3,0.1

Type RM Length L Ch R = 1 ,10084.5 ,410.5,403.1,395.6
XS GIS Cut Line= 3
     1849811.558      475002.138     1849906.002      475063.249
      1850058.78      475321.026
#Sta/Elev= 30
       0  947.39    18.8  942.11    37.5  936.59    46.9  933.39    56.2  929.46
    84.4  914.24    93.7  910.24   112.5   908.1   122.2  906.73   131.8  906.13
   141.5  905.31   151.2   904.4   170.5   902.2   218.8  898.97   238.2  898.12
   257.5  896.29   267.2   896.2   276.8  896.29   286.5  896.82   296.2  897.05
   305.8  897.79   315.5  899.38   325.2  900.21   334.8  900.48   354.2  901.37
   363.8  903.07   373.5   907.6   383.1  914.38   392.8  920.53   412.1  931.92
#Mann= 3 , 0 , 0
       0      .1       0   257.5    .045       0   276.8      .1       0
Bank Sta=257.5,276.8
XS Rating Curve= 0 ,0
Exp/Cntr=0.3,0.1

Type RM Length L Ch R = 1 ,9681.4  ,378,373.5,369.3
XS GIS Cut Line= 2
     1849560.877      475312.797     1849805.322      475524.603
#Sta/Elev= 30
       0  938.16     9.8  929.82    29.4  912.72    39.2  905.68      49  900.45
    58.8  896.34    68.6  894.06    78.4  893.15    88.2  892.69      98   892.5
   107.8  892.43   117.6  892.43   127.4  892.54   137.2  893.32     147  893.81
   156.8  893.85   166.6  894.15   176.4  894.87   186.2  895.32     196  895.35
   215.6  894.97   225.4  894.96   235.2  895.17   254.8  895.85   264.6  896.37
   274.4  898.74   284.2  903.91     294  909.93   303.8  915.66   323.4  925.92
#Mann= 3 , 0 , 0
       0      .1       0   107.8    .045       0   127.4      .1       0
Bank Sta=107.8,127.4
XS Rating Curve= 0 ,0
Exp/Cntr=0.3,0.1

Type RM Length L Ch R = 1 ,9307.9  ,323.7,329.3,334.6
XS GIS Cut Line= 2
     1849315.044      475625.818     1849621.989      475802.207
#Sta/Elev= 30
       0  943.62    19.7  930.78    29.5  925.05    39.3  918.69    49.2  913.36
      59  908.77    68.8  904.89    78.7  901.48    88.5  898.72   108.2   893.7
     118  891.63   127.8  890.47   139.8  889.76   147.5  889.82   154.8  889.56
   167.2  889.47   186.8  891.63   196.7  890.98   206.5  889.55   216.3  888.78
   226.2  888.89   255.7  889.93   265.5  891.47   275.4  893.59   285.2  894.54
   304.8  895.32   314.7   897.8   324.5  902.31   334.4  907.28     354  917.86
#Mann= 3 , 0 , 0
       0      .1       0   139.8    .045       0   154.8      .1       0
Bank Sta=139.8,154.8
XS Rating Curve= 0 ,0
Exp/Cntr=0.3,0.1

Type RM Length L Ch R = 1 ,8978.6  ,364.5,382.3,398.4
XS GIS Cut Line= 2
     1849207.166      475887.266     1849422.166      476092.822
#Sta/Elev= 30
       0  916.87     9.6  915.56    19.2  913.82    28.8  909.59    38.4  903.38
      48  897.47    57.6  893.14    67.2  891.74    76.8  892.81    86.4   892.6
      96  889.88   105.6  886.91   115.1  886.28   124.7  885.96   134.3  885.42
   140.8  885.19   143.9  885.08   155.8  885.21   182.3  885.96   191.9   886.1
   201.5  886.14   211.1   886.4   220.7  889.23   230.3  893.51   249.5  903.48
   259.1  908.65   268.7  914.35   278.3   920.6   287.9  926.72   297.4  933.38
#Mann= 3 , 0 , 0
       0      .1       0   140.8    .045       0   155.8      .1       0
Bank Sta=140.8,155.8
XS Rating Curve= 0 ,0
Exp/Cntr=0.3,0.1

Type RM Length L Ch R = 1 ,8596.3  ,225.9,229,232
XS GIS Cut Line= 2
     1849023.398      475977.172     1849036.176      476241.061
#Sta/Elev= 29
       0   890.9     9.8  888.78    19.6   888.4    29.4  888.14    39.1  887.92
    48.9  887.71    58.7   887.7    68.5   887.5    78.3  886.32    88.1  884.47
    97.8  883.41   107.6  883.08   117.4  882.48   127.2  881.09   136.9  879.75
   146.8  879.85   151.9  880.18   156.6  880.49   166.4  881.18   176.1   883.7
   185.9   888.5   195.7  894.08   205.5  899.77   215.3  905.75   225.1   912.1
   234.8  917.84   244.6  921.74   254.4  924.39   264.2  927.21
#Mann= 3 , 0 , 0
       0      .1       0   136.9    .045       0   151.9      .1       0
Bank Sta=136.9,151.9
XS Rating Curve= 0 ,0
Exp/Cntr=0.3,0.1