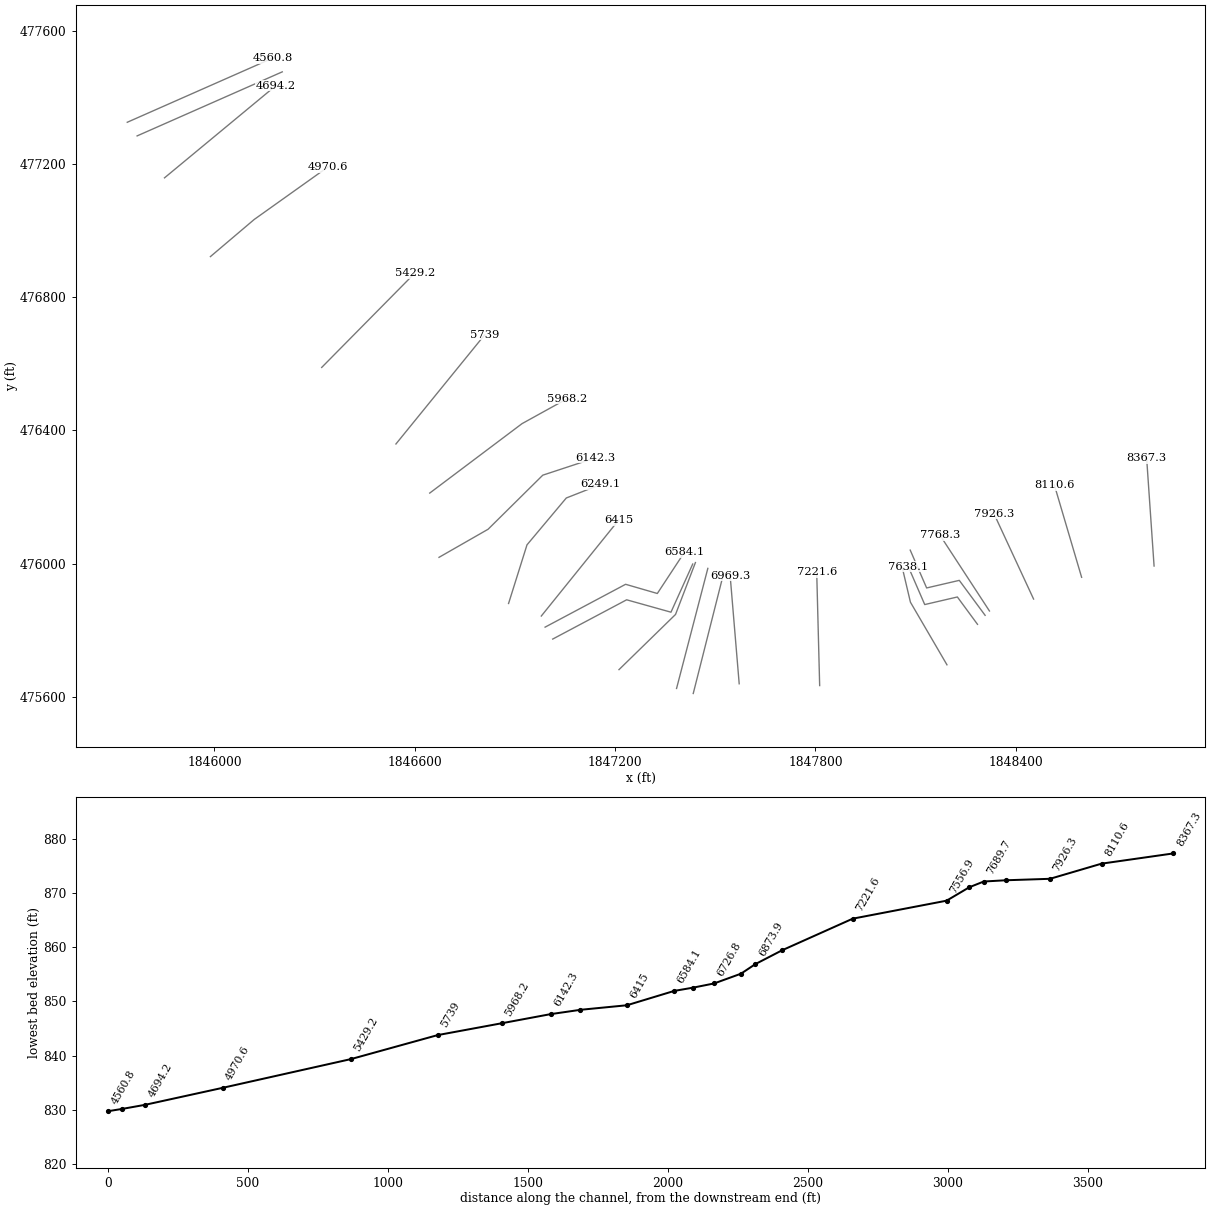
HEC-RAS study CAMPBLSCK.prj: CAMPBLSCK

--- CAMPBLSCK.g01 (geometry) --- (continued)

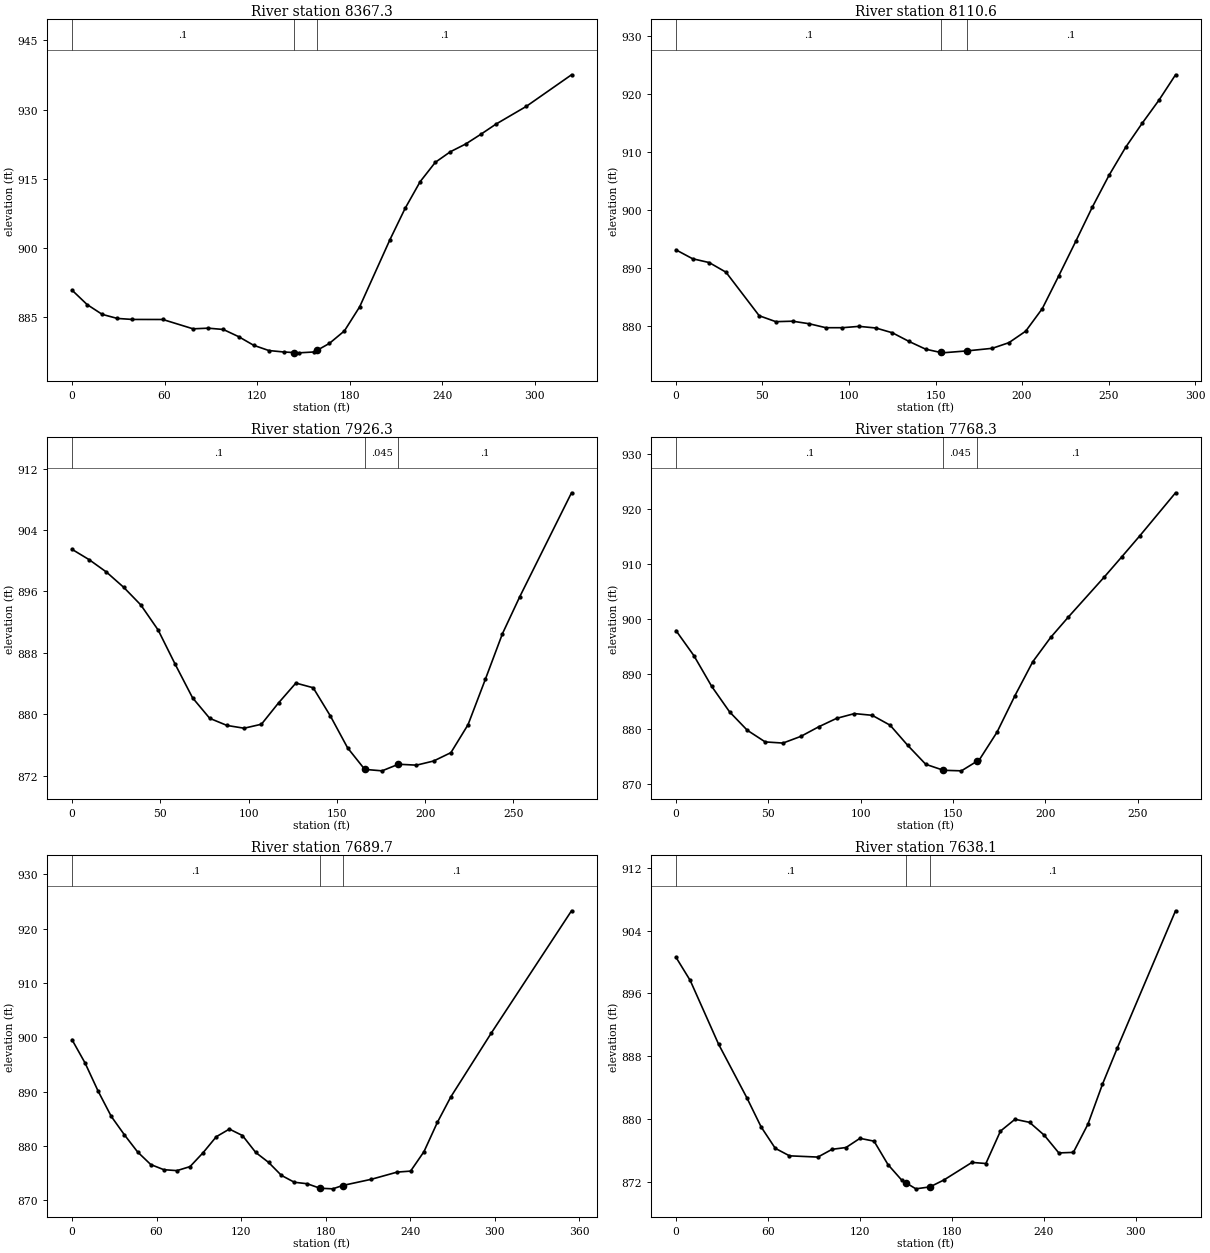
Type RM Length L Ch R = 1 ,8367.3  ,251.8,256.7,261.3
XS GIS Cut Line= 2
     1848814.492      475993.065      1848792.27      476316.155
#Sta/Elev= 30
       0  890.91     9.8  887.78    19.6  885.65    29.4  884.77    39.2  884.55
    58.9  884.54    78.5  882.52    88.3  882.66    98.1  882.38     108  880.83
   117.8  878.95   127.6  877.82   137.4   877.5     144  877.38   147.2  877.32
     157  877.51     159  877.89   166.8  879.35   176.6  882.07   186.5   887.3
   206.1  901.82   215.9  908.58   225.7  914.39   235.5  918.57   245.3  920.87
   255.2  922.54     265  924.64   274.8  926.84   294.4  930.67   323.8  937.53
#Mann= 3 , 0 , 0
       0      .1       0     144    .045       0     159      .1       0
Bank Sta=144,159
XS Rating Curve= 0 ,0
Exp/Cntr=0.3,0.1

Type RM Length L Ch R = 1 ,8110.6  ,180.9,184.3,187.5
XS GIS Cut Line= 2
     1848597.478      475959.211     1848515.881       476236.12
#Sta/Elev= 30
       0  893.17     9.6  891.64    19.2  890.98    28.9  889.32    48.1  881.82
    57.7   880.8    67.4  880.88      77  880.44    86.6  879.76    96.2  879.76
   105.8  879.99   115.5  879.71   125.1  878.88   134.7  877.39   144.3  876.06
     153  875.49     154  875.43     168  875.76   182.8  876.21   192.4  877.18
   202.1  879.16   211.7  883.05   221.3  888.75     231  894.62   240.6  900.53
   250.2  905.98   259.8  910.81   269.4  914.97   279.1  918.95   288.7  923.33
#Mann= 3 , 0 , 0
       0      .1       0     153    .045       0     168      .1       0
Bank Sta=153,168
XS Rating Curve= 0 ,0
Exp/Cntr=0.3,0.1

Type RM Length L Ch R = 1 ,7926.3  ,154.6,158.1,161.1
XS GIS Cut Line= 2
     1848453.575      475893.961     1848334.687      476150.627
#Sta/Elev= 28
       0  901.48     9.8  900.12    19.5  898.52    29.3  896.53      39  894.23
    48.8  890.97    58.5  886.49    68.3  882.14      78  879.47    87.8  878.54
    97.5  878.18   107.3   878.7     117  881.48   126.8  884.06   136.6  883.45
   146.3  879.79   156.1  875.62   165.8  872.82   175.6  872.63   184.9  873.49
   195.1  873.37   204.8  873.91   214.6     875   224.3  878.64   234.1  884.55
   243.8   890.5   253.6  895.31   282.9  908.84
#Mann= 3 , 0 , 0
       0      .1       0   165.8    .045       0   184.9      .1       0
Bank Sta=165.8,184.9
XS Rating Curve= 0 ,0
Exp/Cntr=0.3,0.1

Type RM Length L Ch R = 1 ,7768.3  ,40.8,78.6,107.3
XS GIS Cut Line= 2
     1848321.376       475858.15     1848173.806      476084.713
#Sta/Elev= 28
       0  897.87     9.7  893.31    19.3  887.74      29  883.09    38.6  879.74
    48.3  877.62    57.9  877.41    67.6  878.63    77.2  880.36    86.9   881.9
    96.6  882.77   106.2  882.46   115.9  880.66   125.5  876.97   135.2  873.55
   144.8  872.46   154.5  872.36   162.9   874.1   164.2  874.37   173.8  879.41
   183.5  886.05   193.1  892.19   202.8  896.62   212.4  900.34   231.8   907.6
   241.4  911.32   251.1  915.12   270.4  922.93
#Mann= 3 , 0 , 0
       0      .1       0   144.8    .045       0   162.9      .1       0
Bank Sta=144.8,162.9
XS Rating Curve= 0 ,0
Exp/Cntr=0.3,0.1

Type RM Length L Ch R = 1 ,7689.7  ,59.9,51.6,58.7
XS GIS Cut Line= 4
     1848308.397      475845.121     1848231.018      475950.034
     1848133.226      475927.247     1848084.093      476040.841
#Sta/Elev= 30
       0  899.57     9.3  895.27    18.6  890.08    27.9  885.45    37.2  882.07
    46.6  878.91    55.9   876.6    65.2  875.65    74.5  875.48    83.8  876.22
    93.1  878.79   102.4  881.71   111.7  883.12     121  881.93   130.4  878.82
   139.5     877   148.6  874.61   157.8  873.34   166.9  873.07     176  872.24
   185.1  872.13     192  872.74   212.5  873.89   230.8  875.21   240.3  875.39
   249.8  878.97   259.3  884.35   268.8  889.02   297.4  900.71   354.5  923.26
#Mann= 3 , 0 , 0
       0      .1       0     176    .045       0     192      .1       0
Bank Sta=176,192
XS Rating Curve= 0 ,0
Exp/Cntr=0.3,0.1

Type RM Length L Ch R = 1 ,7638.1  ,111.2,81.2,43.8
XS GIS Cut Line= 4
      1848285.61      475818.062     1848225.321      475900.188
     1848127.529      475877.402     1848078.396      475990.995
#Sta/Elev= 30
       0   900.6     9.3  897.64    27.8  889.52    46.3  882.67    55.6  878.96
    64.8  876.24    74.1  875.28    92.6  875.12   101.9  876.11     111  876.34
   120.1  877.51   129.3  877.15   138.4  874.16   147.5  872.15     150  871.85
   156.6  871.07   165.8  871.32   174.9   872.2   193.2  874.44   202.3   874.3
   211.8  878.43   221.3  879.94   230.8  879.55   240.4  877.91   249.9  875.65
   259.4  875.72   268.9  879.31   278.4  884.41     288  888.99   326.1  906.53
#Mann= 3 , 0 , 0
       0      .1       0     150    .045       0   165.8      .1       0
Bank Sta=150,165.8
XS Rating Curve= 0 ,0
Exp/Cntr=0.3,0.1

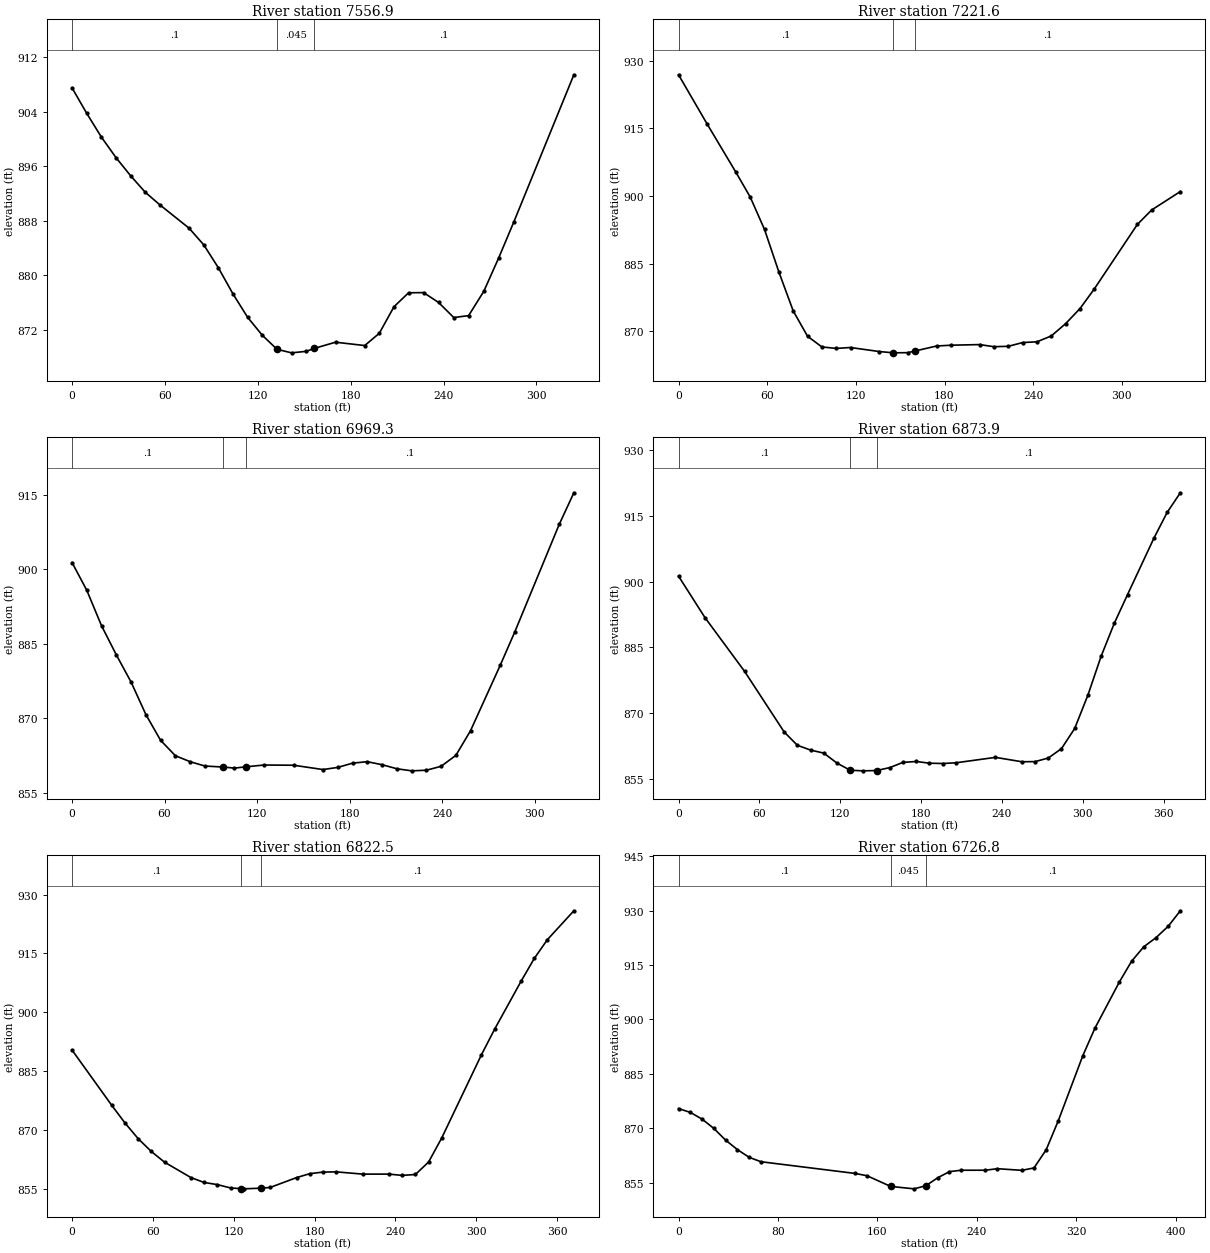
Type RM Length L Ch R = 1 ,7556.9  ,346.1,335.2,323.4
XS GIS Cut Line= 3
     1848194.085        475696.6     1848084.687      475884.516
     1848060.242      475988.405
#Sta/Elev= 30
       0  907.46     9.4  903.76    18.9  900.26    28.4  897.23    37.8  894.58
    47.3  892.15    56.7  890.31    75.6  886.88    85.1  884.43    94.5  881.08
     104  877.22   113.4  873.81   122.9  871.17   132.4  869.11   141.8  868.59
   151.3  868.81   156.5  869.24   170.2  870.15   189.1  869.66   198.5  871.46
     208  875.36   217.4   877.4   227.1  877.43   236.8  875.98   246.6  873.77
   256.2  874.05     266  877.61   275.7  882.55   285.4  887.79   324.2  909.39
#Mann= 3 , 0 , 0
       0      .1       0   132.4    .045       0   156.5      .1       0
Bank Sta=132.4,156.5
XS Rating Curve= 0 ,0
Exp/Cntr=0.3,0.1

Type RM Length L Ch R = 1 ,7221.6  ,251.1,252.4,253.4
XS GIS Cut Line= 2
     1847812.835      475634.239     1847804.005      475973.705
#Sta/Elev= 30
       0   926.9    19.4  915.96    38.8  905.31    48.5  899.81    58.2  892.61
    67.9   883.2    77.6  874.57    87.3  868.95      97  866.58   106.7  866.25
   116.4  866.45   135.8  865.56   145.2  865.28   145.5  865.27   155.2  865.31
   160.2  865.69   174.6  866.78   184.3  866.96   203.8   867.1   213.4  866.63
   223.2  866.72   232.9  867.55   242.6  867.72   252.3  869.02     262  871.75
   271.7  875.08   281.4  879.44   310.5  893.72   320.2  896.93   339.6  901.02
#Mann= 3 , 0 , 0
       0      .1       0   145.2    .045       0   160.2      .1       0
Bank Sta=145.2,160.2
XS Rating Curve= 0 ,0
Exp/Cntr=0.3,0.1

Type RM Length L Ch R = 1 ,6969.3  ,102.9,95.4,87.8
XS GIS Cut Line= 2
     1847571.793      475639.655      1847544.71      475963.961
#Sta/Elev= 30
       0  901.37     9.6  895.75    19.1  888.65    28.7  882.78    38.3  877.29
    47.9  870.74    57.4  865.58      67  862.47    76.6  861.27    86.1   860.4
    98.1  860.19   105.3  859.98   113.1  860.25   124.4   860.6   143.6  860.56
   162.7  859.69   172.3  860.12   181.9  860.98   191.4  861.27     201  860.67
   210.6  859.85   220.2  859.43   229.7  859.55   239.3  860.34   248.9  862.55
   258.4  867.52   277.6  880.65   287.2  887.48   315.9  909.05   325.4  915.42
#Mann= 3 , 0 , 0
       0      .1       0    98.1    .045       0   113.1      .1       0
Bank Sta=98.1,113.1
XS Rating Curve= 0 ,0
Exp/Cntr=0.3,0.1

Type RM Length L Ch R = 1 ,6873.9  ,51.5,51.4,51.4
XS GIS Cut Line= 2
     1847434.148      475610.474     1847525.222      475971.552
#Sta/Elev= 30
       0  901.24    19.6   891.8      49  879.55    78.4  865.73    88.2   862.7
      98  861.61   107.8  860.92   117.6  858.64   127.4  857.01   137.2  856.88
     147  856.95   156.8  857.62   166.6  858.81   176.4  859.01   186.2  858.62
     196  858.55   205.8  858.71   235.2  859.95   254.8  858.95   264.6  858.98
   274.4   859.8   284.2  861.94     294  866.53   303.8  874.12   313.6  882.97
   323.4   890.5   333.2  897.02   352.8  909.89   362.6  915.74   372.4  920.23
#Mann= 3 , 0 , 0
       0      .1       0   127.4    .045       0     147      .1       0
Bank Sta=127.4,147
XS Rating Curve= 0 ,0
Exp/Cntr=0.3,0.1

Type RM Length L Ch R = 1 ,6822.5  ,108.2,95.8,83.7
XS GIS Cut Line= 2
      1847384.19      475625.604      1847477.86      475986.017
#Sta/Elev= 30
       0  890.42    29.4  876.38    39.2   871.9      49   867.9    58.8  864.62
    68.6   861.9    88.2  857.98      98  856.73   107.8  856.19   117.6  855.34
   125.1  855.16   127.4  855.11   140.1  855.28     147  855.46   166.6  857.97
   176.4  858.97   186.2  859.37     196  859.43   215.6  858.86   235.2  858.86
     245  858.53   254.8  858.76   264.6  861.94   274.4   868.1   303.8  889.22
   313.6  895.74   333.2  907.92     343  913.73   352.8  918.54   372.4  925.87
#Mann= 3 , 0 , 0
       0      .1       0   125.1    .045       0   140.1      .1       0
Bank Sta=125.1,140.1
XS Rating Curve= 0 ,0
Exp/Cntr=0.3,0.1

Type RM Length L Ch R = 1 ,6726.8  ,105.7,75.6,44.2
XS GIS Cut Line= 3
     1847211.765      475682.101     1847381.116       475847.73
     1847440.668      476003.433
#Sta/Elev= 30
       0  875.43     9.5  874.37      19  872.51    28.4  869.95    37.9  866.72
    47.4  864.11    56.8  861.99    66.3  860.78   142.1  857.55   151.6  856.92
   170.6  853.98   189.5  853.31     199  854.18   208.5  856.37   217.9  858.05
   227.4  858.44   246.7  858.44   256.5  858.86   276.1  858.41   285.9  859.07
   295.7  864.07   305.5  872.12   325.1  889.94   334.9  897.57   354.6  910.33
   364.4  916.02   374.2  920.01     384  922.51   393.8  925.64   403.6  929.93
#Mann= 3 , 0 , 0
       0      .1       0   170.6    .045       0     199      .1       0
Bank Sta=170.6,199
XS Rating Curve= 0 ,0
Exp/Cntr=0.3,0.1

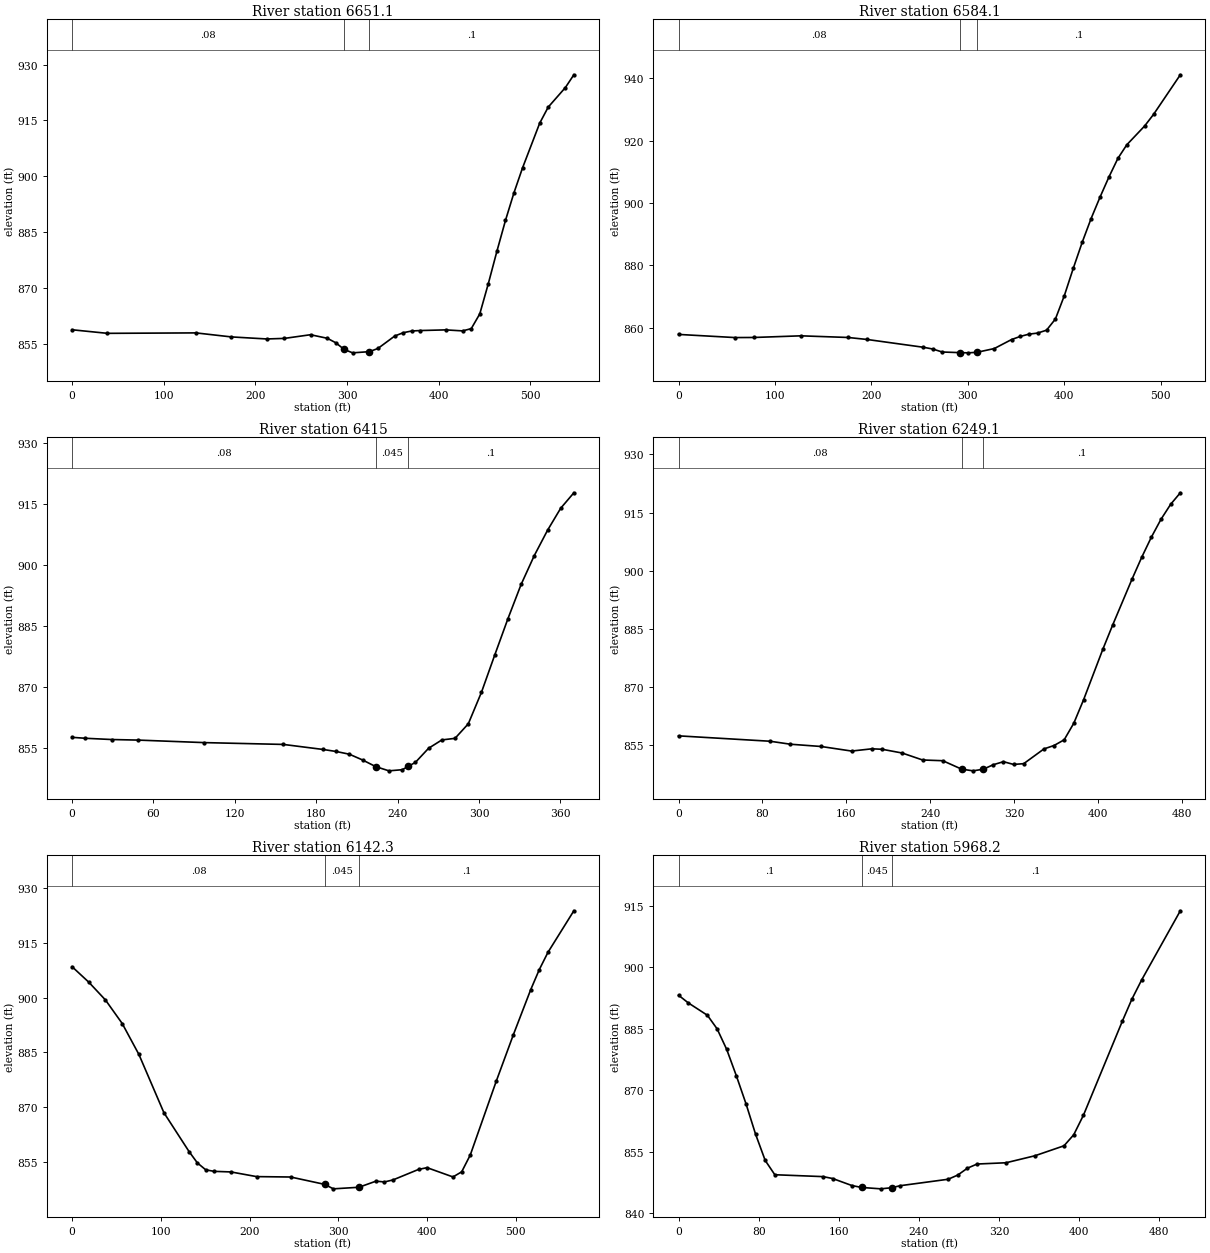
Type RM Length L Ch R = 1 ,6651.1  ,69.8,67,67.3
XS GIS Cut Line= 4
     1847013.231      475773.863      1847234.69      475891.726
     1847367.441      475854.506     1847432.576      475999.044
#Sta/Elev= 30
       0  858.73    38.6  857.77   135.1  857.89   173.7  856.81   212.3  856.26
   231.6  856.41   260.1   857.4   278.4  856.44   287.6  855.24   296.8  853.44
     306  852.53   324.4  852.85   333.6  853.71     352  857.06   361.2  857.94
   370.4   858.4   379.6  858.52   407.4   858.7     426  858.43   435.4  859.04
   444.7     863     454  871.12   463.3  879.77   472.7  888.11     482  895.57
   491.3  902.22     510  914.23   519.3  918.56     538  923.81   547.3  927.26
#Mann= 3 , 0 , 0
       0     .08       0   296.8    .045       0   324.4      .1       0
Bank Sta=296.8,324.4
XS Rating Curve= 0 ,0
Exp/Cntr=0.3,0.1

Type RM Length L Ch R = 1 ,6584.1  ,132.9,169.1,202.4
XS GIS Cut Line= 4
      1846990.43       475809.65     1847231.588      475938.251
     1847326.587      475910.649     1847407.763      476034.403
#Sta/Elev= 30
       0  857.84    58.6  856.83    78.1  856.86   126.9  857.39   175.7  856.86
   195.2  856.23   253.8  853.72   263.5  853.16   273.3   852.2   291.3     852
   300.3  851.93   309.3   852.1   327.3   853.3   345.2  856.19   354.2  857.19
   363.2  857.92   372.2  858.27   381.5   859.2   390.7  862.78     400  870.32
   409.2  879.03   418.5  887.42   427.7  895.02     437  901.93   446.2  908.36
   455.5  914.34   464.7  918.68   483.2  924.72   492.5  928.46   520.2  941.15
#Mann= 3 , 0 , 0
       0     .08       0   291.3    .045       0   309.3      .1       0
Bank Sta=291.3,309.3
XS Rating Curve= 0 ,0
Exp/Cntr=0.3,0.1

Type RM Length L Ch R = 1 ,6415    ,166.2,165.9,165.4
XS GIS Cut Line= 2
     1846979.055      475842.995     1847210.999       476131.19
#Sta/Elev= 27
       0  857.54     9.7  857.31    29.2     857    48.7  856.86    97.4  856.24
   155.8  855.79     185  854.55   194.7  854.05   204.4  853.38   214.2  851.95
   223.9  850.31   233.6  849.28   243.4  849.56   247.8  850.38   253.1  851.37
   262.8  854.84   272.6   856.9   282.3  857.29   292.1  860.88   301.8  868.66
   311.5  877.76   321.3  886.79     331  895.22   340.7  902.33   350.5  908.59
   360.2  914.02   369.9  917.83
#Mann= 3 , 0 , 0
       0     .08       0   223.9    .045       0   247.8      .1       0
Bank Sta=223.9,247.8
XS Rating Curve= 0 ,0
Exp/Cntr=0.3,0.1

Type RM Length L Ch R = 1 ,6249.1  ,108.9,106.8,104.7
XS GIS Cut Line= 4
     1846880.994      475880.627     1846936.203      476056.669
     1847053.911      476197.294     1847157.036      476237.919
#Sta/Elev= 30
       0  857.46    87.4  856.07   106.8   855.3   135.9  854.72   165.1  853.54
   184.5  854.12   194.2     854   213.4  853.03   232.8  851.24   252.1  851.05
   270.1  848.87     281  848.44   290.7  848.86   300.3  850.02     310   850.8
   319.6  850.09   329.3  850.29   348.6  854.09   358.2  854.97   367.9  856.44
   377.1  860.73   386.4  866.76   404.8   879.8   414.1     886   432.5  897.79
   441.8  903.46     451  908.65   460.2  913.27   469.5  917.17   478.7  920.13
#Mann= 3 , 0 , 0
       0     .08       0   270.1    .045       0   290.7      .1       0
Bank Sta=270.1,290.7
XS Rating Curve= 0 ,0
Exp/Cntr=0.3,0.1

Type RM Length L Ch R = 1 ,6142.3  ,177.1,174.1,171
XS GIS Cut Line= 4
     1846672.661      476019.169     1846819.641      476103.448
     1846983.464      476265.773     1847140.522      476317.558
#Sta/Elev= 30
       0  908.49    18.8  904.26    37.6  899.38    56.5  892.93    75.3  884.46
   103.5  868.49   131.8  857.86   141.2  854.74   150.6  852.85     160  852.43
     179  852.27   207.9  850.99   246.3  850.88   284.7  848.86   294.4  847.64
   323.2  848.07   342.4  849.74     352  849.53   361.6  850.08   390.4  852.96
     400  853.44   429.2   850.9     439   852.3   448.7  856.92   477.9  877.09
   497.3   889.9   516.8  902.21   526.5  907.72   536.2  912.42   565.4  923.81
#Mann= 3 , 0 , 0
       0     .08       0   284.7    .045       0   323.2      .1       0
Bank Sta=284.7,323.2
XS Rating Curve= 0 ,0
Exp/Cntr=0.3,0.1

Type RM Length L Ch R = 1 ,5968.2  ,223.3,229.2,234.5
XS GIS Cut Line= 3
     1846644.855      476212.042     1846921.244      476420.375
     1847056.661      476495.375
#Sta/Elev= 30
       0  893.18     9.6  891.33    28.8  888.29    38.5  884.98    48.1  879.95
    57.7  873.54    67.3  866.74    76.9  859.29    86.5  852.89    96.1   849.4
   144.2  848.94   153.8  848.48   173.1  846.76   182.7   846.3   201.9  845.96
   213.1  846.24   221.1  846.72   269.2   848.3   278.8  849.33   288.4     851
     298  852.01   326.9  852.32   355.8  854.03   384.8  856.46   394.5  859.15
   404.2  863.92   442.9  886.78   452.5  892.19   462.2  896.86   500.9  913.77
#Mann= 3 , 0 , 0
       0      .1       0   182.7    .045       0   213.1      .1       0
Bank Sta=182.7,213.1
XS Rating Curve= 0 ,0
Exp/Cntr=0.3,0.1

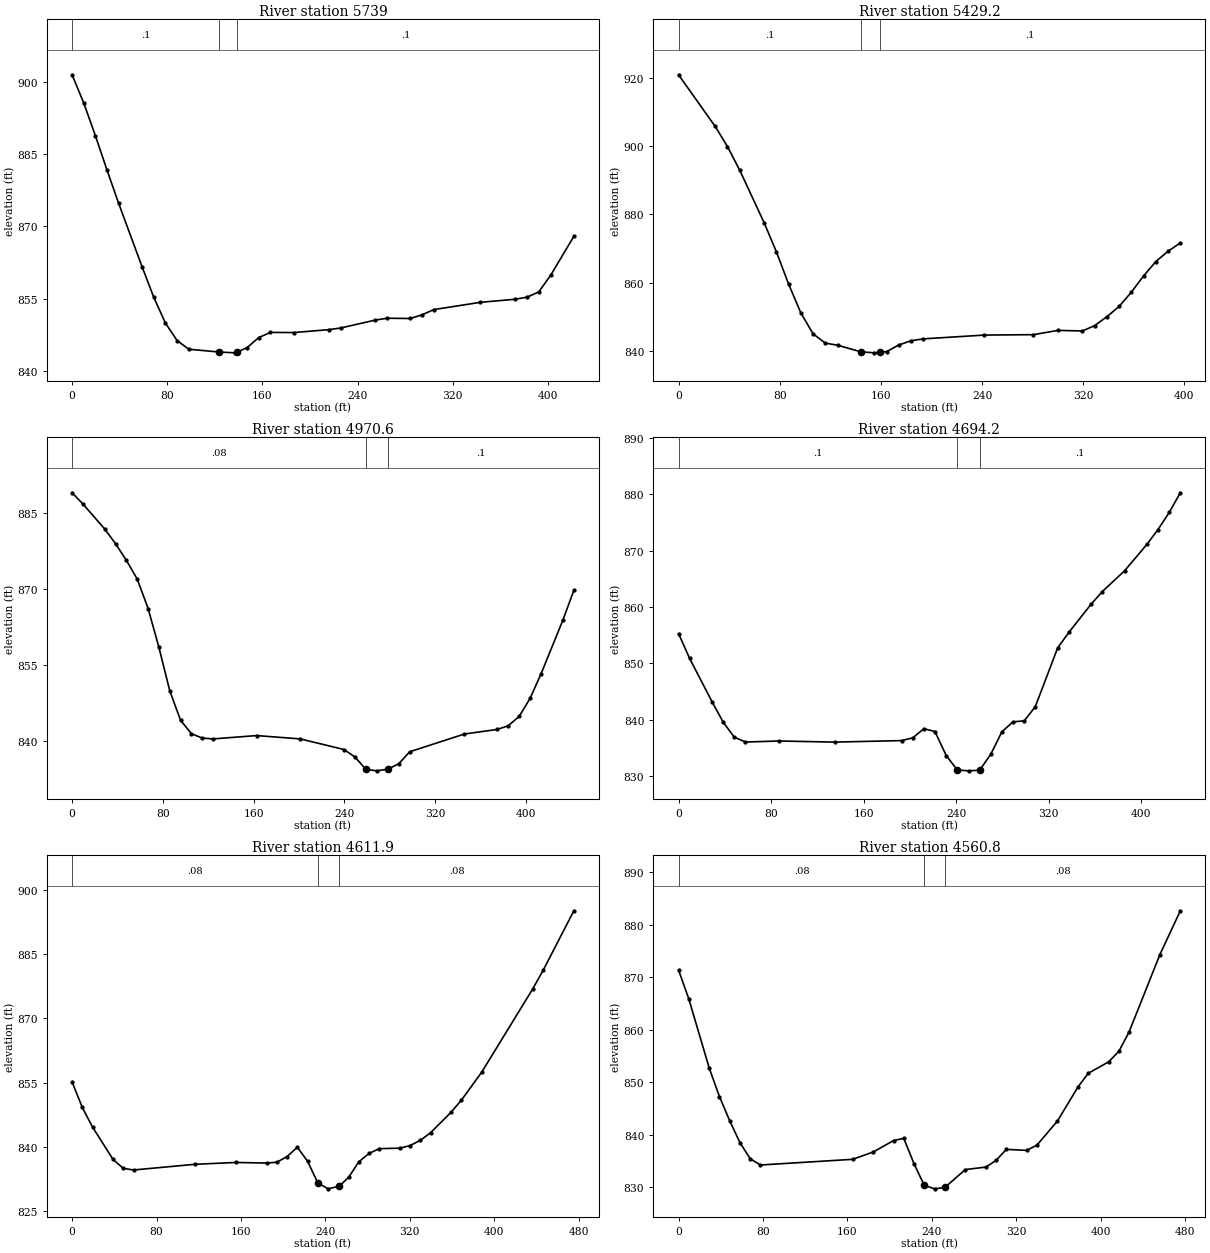
Type RM Length L Ch R = 1 ,5739    ,312,309.8,307.6
XS GIS Cut Line= 2
     1846543.644      476359.408     1846809.439      476687.042
#Sta/Elev= 30
       0  901.49     9.8  895.65    19.6  888.86    29.4  881.69    39.2  874.78
    58.9  861.61    68.7   855.3    78.5  849.94    88.3  846.33    98.1  844.52
   123.7  843.94   137.4  843.77   138.7  843.91   147.2  844.86     157  846.95
   166.8  848.01   186.4  847.98   215.8  848.58   225.7  848.92   255.1  850.58
   264.9  850.95   284.5   850.9   294.3  851.67   304.2  852.75   343.4  854.26
   372.8   854.9   382.6  855.33   392.4  856.42   402.3  859.84   421.9  867.95
#Mann= 3 , 0 , 0
       0      .1       0   123.7    .045       0   138.7      .1       0
Bank Sta=123.7,138.7
XS Rating Curve= 0 ,0
Exp/Cntr=0.3,0.1

Type RM Length L Ch R = 1 ,5429.2  ,462.5,458.6,454.6
XS GIS Cut Line= 2
     1846321.244      476589.125     1846599.717      476871.764
#Sta/Elev= 30
       0  921.03      29  905.85    38.7  899.95    48.4  892.98    67.7  877.56
    77.4     869    87.1  859.47    96.8  851.01   106.4  844.92   116.1   842.2
   125.8  841.57   144.1  839.65   154.8  839.34   159.1  839.49   164.5  839.68
   174.2  841.66   183.9   842.9   193.6  843.45   241.9  844.56   280.6  844.68
     300  845.93   319.4  845.77     329  847.33   338.7  849.94   348.4  852.98
   358.1  857.17   367.7  861.92   377.4  866.15   387.1  869.19   396.8  871.64
#Mann= 3 , 0 , 0
       0      .1       0   144.1    .045       0   159.1      .1       0
Bank Sta=144.1,159.1
XS Rating Curve= 0 ,0
Exp/Cntr=0.3,0.1

Type RM Length L Ch R = 1 ,4970.6  ,274.8,276.4,278
XS GIS Cut Line= 3
     1845987.955      476921.814     1846119.152      477033.279
     1846338.881      477190.075
#Sta/Elev= 30
       0  888.98     9.6  886.76    28.7  881.83    38.3  878.92    47.8  875.65
    57.4  871.93      67  866.11    76.5  858.44    86.1  849.83    95.6  844.02
   105.2  841.36   114.8   840.5   124.3  840.34   162.6     841   201.1  840.34
   239.6  838.24   249.3  836.75   258.9   834.3   268.6  834.03   278.2  834.37
   287.8  835.42   297.5   837.8   345.7  841.31   374.6  842.21   384.2  842.93
   393.9  844.78   403.5  848.33   413.2  853.21   432.4  863.79   442.1   869.7
#Mann= 3 , 0 , 0
       0     .08       0   258.9    .045       0   278.2      .1       0
Bank Sta=258.9,278.2
XS Rating Curve= 0 ,0
Exp/Cntr=0.3,0.1

Type RM Length L Ch R = 1 ,4694.2  ,88.6,82.3,75.9
XS GIS Cut Line= 2
     1845850.399      477158.163     1846184.441      477435.265
#Sta/Elev= 30
       0  855.27     9.6  850.85    28.9   843.2    38.6  839.55    48.2  836.88
    57.9  836.01    86.8   836.2     135     836   192.9  836.27   202.5  836.75
   212.2  838.38   221.8  837.88   231.5  833.62   241.1  831.05   250.8   830.9
   260.4  831.01     270  833.82   279.7  837.84   289.3   839.6     299  839.77
   308.6  842.31   327.9  852.72   337.6  855.48   356.9   860.5   366.5  862.72
   385.8  866.42   405.1   871.1   414.7  873.74   424.4  876.77     434  880.26
#Mann= 3 , 0 , 0
       0      .1       0   241.1    .045       0   260.4      .1       0
Bank Sta=241.1,260.4
XS Rating Curve= 0 ,0
Exp/Cntr=0.3,0.1

Type RM Length L Ch R = 1 ,4611.9  ,51.1,51.1,51.1
XS GIS Cut Line= 2
     1845768.374      477284.076     1846203.161      477476.352
#Sta/Elev= 30
       0  855.17     9.7  849.17    19.4  844.59    38.8  837.02    48.5  834.93
    58.2  834.55   116.4  835.88   155.2  836.31   184.3  836.17     194  836.36
   203.7  837.69   213.4  839.88   223.2  836.56   232.8  831.52   242.6  830.14
   253.2  830.77     262  832.82   271.7  836.47   281.4  838.44   291.1  839.54
   310.5  839.65   320.2  840.26   329.9  841.48   339.6  843.26     359  848.04
   368.7  850.84   388.1  857.43   436.6  876.97   446.3  881.25   475.4  895.18
#Mann= 3 , 0 , 0
       0     .08       0   232.8    .045       0   253.2     .08       0
Bank Sta=232.8,253.2
XS Rating Curve= 0 ,0
Exp/Cntr=0.3,0.1

Type RM Length L Ch R = 1 ,4560.8  ,196.8,201.5,206.2
XS GIS Cut Line= 2
     1845738.861      477324.997     1846173.647      477517.273
#Sta/Elev= 30
       0  871.37     9.7   865.9    29.1  852.69    38.8  847.26    48.5  842.66
    58.2   838.5    67.9  835.45    77.6  834.25   164.9  835.33   184.3  836.71
   203.7   838.9   213.4  839.33   223.2  834.44   232.8  830.39   242.6  829.71
   252.3  829.97   271.7  833.38   291.1  833.85   300.8  835.11   310.5  837.23
   329.9  837.03   339.6  838.05     359  842.63   378.4   849.1   388.1  851.71
   407.5  853.89   417.2  855.91   426.9   859.6     456   874.3   475.4  882.66
#Mann= 3 , 0 , 0
       0     .08       0   232.8    .045       0   252.3     .08       0
Bank Sta=232.8,252.3
XS Rating Curve= 0 ,0
Exp/Cntr=0.3,0.1