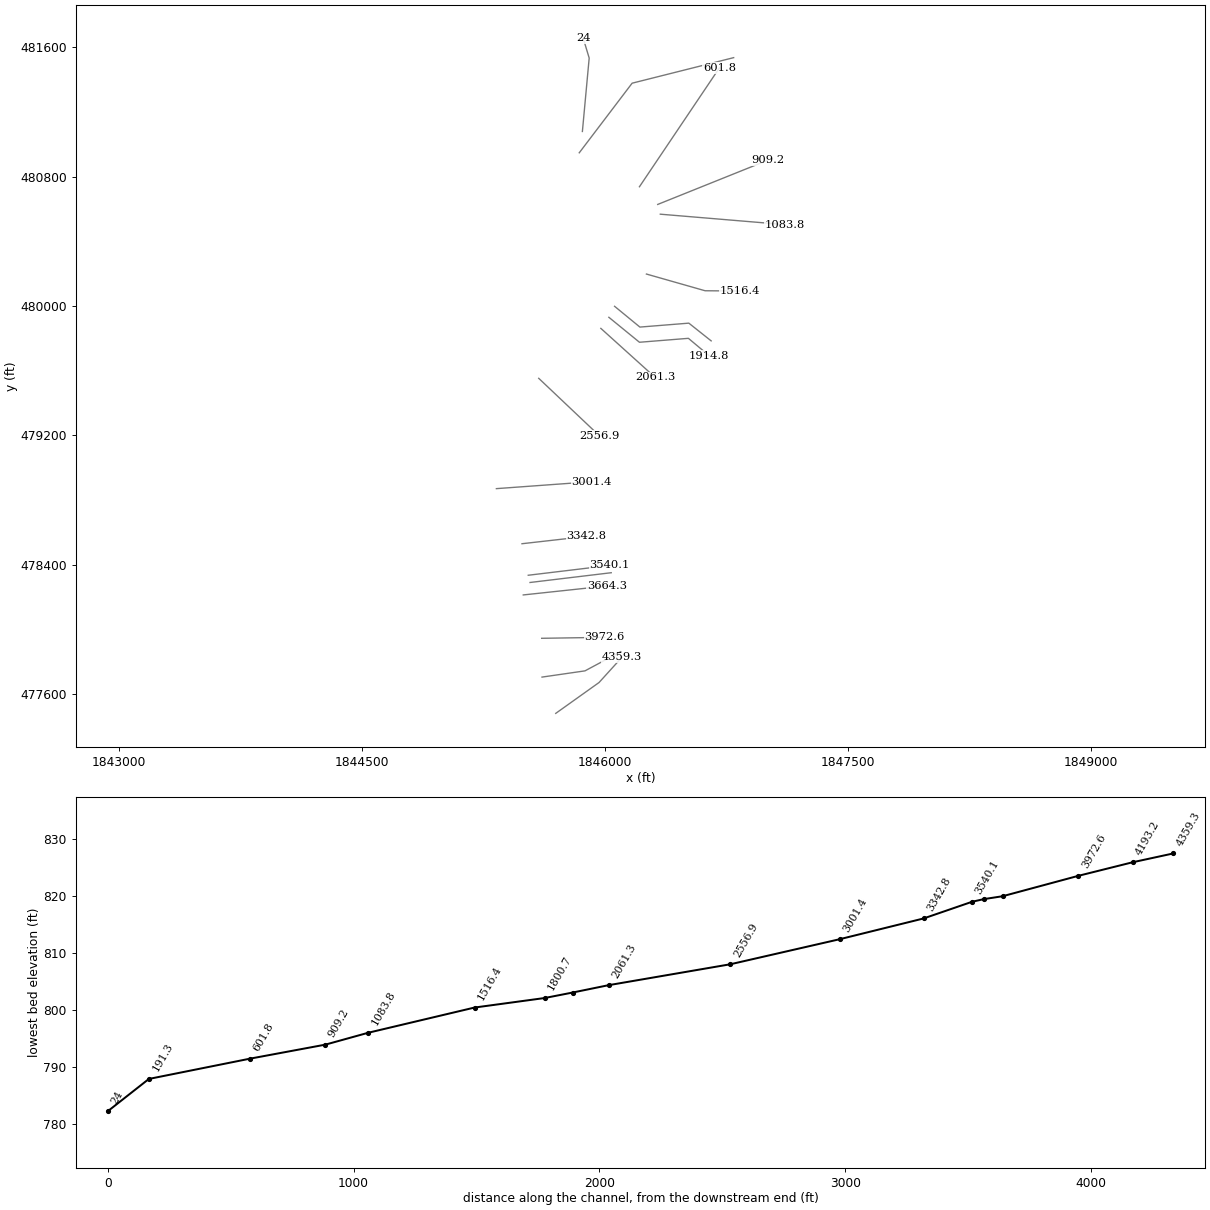
HEC-RAS study CAMPBLSCK.prj: CAMPBLSCK

--- CAMPBLSCK.g01 (geometry) --- (continued)

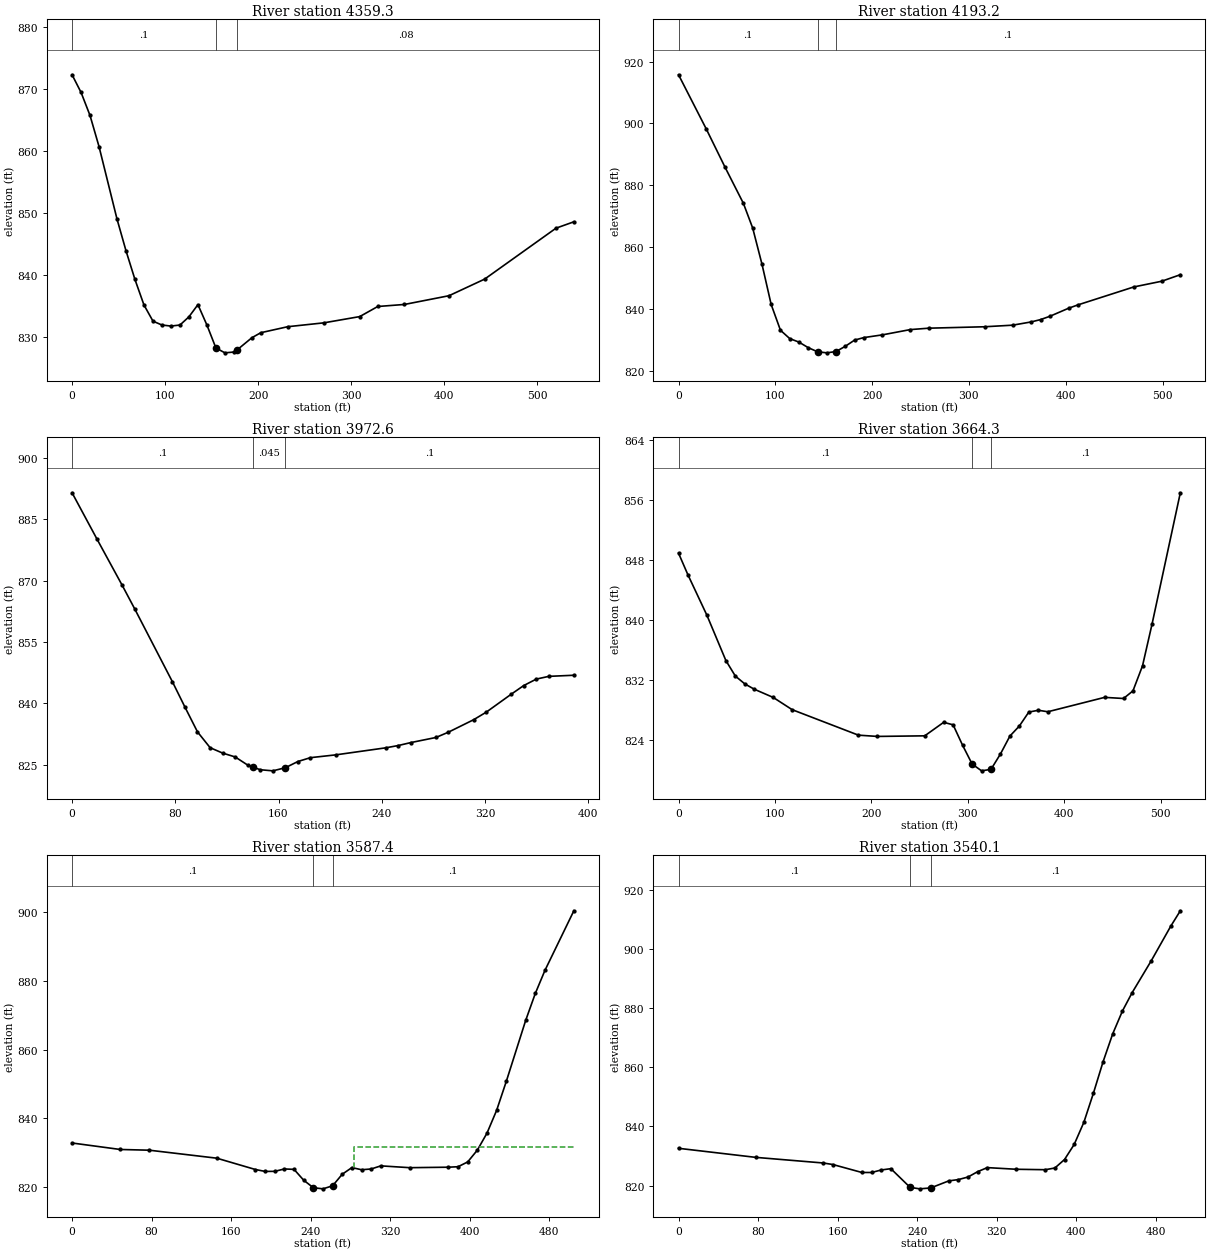
Type RM Length L Ch R = 1 ,4359.3  ,176.8,166.1,155.3
XS GIS Cut Line= 3
     1845695.371      477480.308     1845962.733       477671.28
     1846104.226       477827.53
#Sta/Elev= 30
       0  872.28     9.7  869.42    19.3  865.71      29  860.68    48.3     849
      58  843.86    67.6  839.24    77.3  835.12      87  832.51    96.6  831.89
   106.3  831.72     116  831.89   125.6  833.21   135.3  835.18     145  831.87
   154.6  828.19   164.3   827.4   173.9  827.53   177.7  827.91   193.3  829.84
   202.9  830.65   231.9  831.62   270.6  832.24   309.2  833.25   328.6  834.88
   357.3  835.21   405.2  836.62   443.5   839.3   520.2  847.52   539.4  848.55
#Mann= 3 , 0 , 0
       0      .1       0   154.6    .045       0   177.7     .08       0
Bank Sta=154.6,177.7
XS Rating Curve= 0 ,0
Exp/Cntr=0.3,0.1

Type RM Length L Ch R = 1 ,4193.2  ,223.5,220.6,217.7
XS GIS Cut Line= 3
     1845610.689      477704.771     1845875.934        477743.3
     1846096.508      477861.821
#Sta/Elev= 30
       0  915.74    28.7  898.19    47.9  885.95      67  874.18    76.6   866.2
    86.2  854.52    95.7  841.48   105.3  833.15   114.9  830.45   124.4  829.32
     134  827.52   143.6   826.2   153.2  825.85   162.7  826.27   172.3  827.97
   181.9  829.97   191.4  830.78   210.6  831.66   239.3  833.36   258.5  833.82
   316.2  834.28   345.1  834.79   364.3  835.84     374   836.6   383.6  837.66
   402.9  840.26   412.5  841.34   470.3  847.15   499.2     849   518.4  851.11
#Mann= 3 , 0 , 0
       0      .1       0   143.6    .045       0   162.7      .1       0
Bank Sta=143.6,162.7
XS Rating Curve= 0 ,0
Exp/Cntr=0.3,0.1

Type RM Length L Ch R = 1 ,3972.6  ,306.3,308.3,310.3
XS GIS Cut Line= 2
     1845608.566      477944.717     1845997.455      477950.794
#Sta/Elev= 30
       0  891.49    19.4  880.11    38.9  868.83    48.6  863.06    77.8  845.25
    87.5  839.06    97.2  833.01     107  829.14   116.7  827.82   126.4  826.88
   136.1  824.89   139.9  824.44   145.8  823.75   155.6  823.48   165.3  824.24
     175  825.76   184.7   826.7   204.2  827.38   243.1  829.11   252.8  829.67
   262.5  830.39     282  831.64   291.7  832.94   311.2  835.98   320.9  837.81
   340.3  842.21     350  844.33   359.8  845.92   369.5  846.59   388.9  846.86
#Mann= 3 , 0 , 0
       0      .1       0   139.9    .045       0   165.3      .1       0
Bank Sta=139.9,165.3
XS Rating Curve= 0 ,0
Exp/Cntr=0.3,0.1

Type RM Length L Ch R = 1 ,3664.3  ,76.7,76.9,77
XS GIS Cut Line= 2
     1845494.851      478212.947     1846012.212      478268.502
#Sta/Elev= 30
       0  848.94     9.8  846.04    29.4  840.67    49.1  834.62    58.9  832.55
    68.7  831.51    78.5   830.8    98.2   829.7   117.8  828.07   186.5  824.67
   206.2   824.5   255.3  824.58   274.9  826.38   284.7  826.05   294.5  823.33
   304.4  820.82   314.2  819.91     324  820.11   333.8  822.16   343.6  824.55
   353.4  825.89   363.2  827.75   373.1  827.99   382.9  827.79   441.8  829.71
   461.4  829.56   471.2  830.58   481.1  833.92   490.9  839.44   520.3     857
#Mann= 3 , 0 , 0
       0      .1       0   304.4    .045       0     324      .1       0
Bank Sta=304.4,324
XS Rating Curve= 0 ,0
Exp/Cntr=0.3,0.1

Type RM Length L Ch R = 1 ,3587.4  ,47.2,47.3,47.5
XS GIS Cut Line= 2
     1845536.698      478289.972     1846037.868      478350.391
#Sta/Elev= 30
       0  832.77    48.5  830.88    77.7  830.67   145.6  828.34   184.4  825.04
   194.2  824.48   203.9   824.5   213.6   825.2   223.3  825.08     233  821.92
   242.7  819.73   252.4   819.4   262.1  820.29   271.8  823.66   281.5   825.6
   291.2  824.97   300.9  825.19   310.6   826.1   339.8  825.57   378.6  825.71
   388.3  825.85     398  827.25   407.7  830.69   417.4  835.64   427.1  842.29
   436.8  850.71   456.3   868.5     466  876.38   475.7  883.11   504.8   900.5
#Mann= 3 , 0 , 0
       0      .1       0   242.7    .045       0   262.1      .1       0
#XS Ineff= 2 , 0
                          283.31           831.5
Permanent Ineff=
       F       F
Bank Sta=242.7,262.1
XS Rating Curve= 0 ,0
Exp/Cntr=0.3,0.1

Type RM Length L Ch R = 1 ,3540.1  ,197.5,197.3,197.2
XS GIS Cut Line= 2
     1845525.747      478334.771     1846026.918       478395.19
#Sta/Elev= 30
       0  832.63    77.7  829.57   145.6  827.67   155.3  827.15   184.4  824.47
   194.2  824.46   203.9  825.31   213.6  825.75     233  819.42   242.7  818.94
   253.6  819.24   271.8  821.62   281.5  822.07   291.2  822.93   300.9  824.74
   310.6  826.11   339.8  825.55   368.9   825.4   378.6  825.98   388.3  828.84
     398  833.92   407.7  841.36   417.4  851.28   427.1  861.88   436.8  871.31
   446.6  879.04   456.3  885.19   475.7  896.06   495.1  907.61   504.8  912.86
#Mann= 3 , 0 , 0
       0      .1       0     233    .045       0   253.6      .1       0
Bank Sta=233,253.6
XS Rating Curve= 0 ,0
Exp/Cntr=0.3,0.1

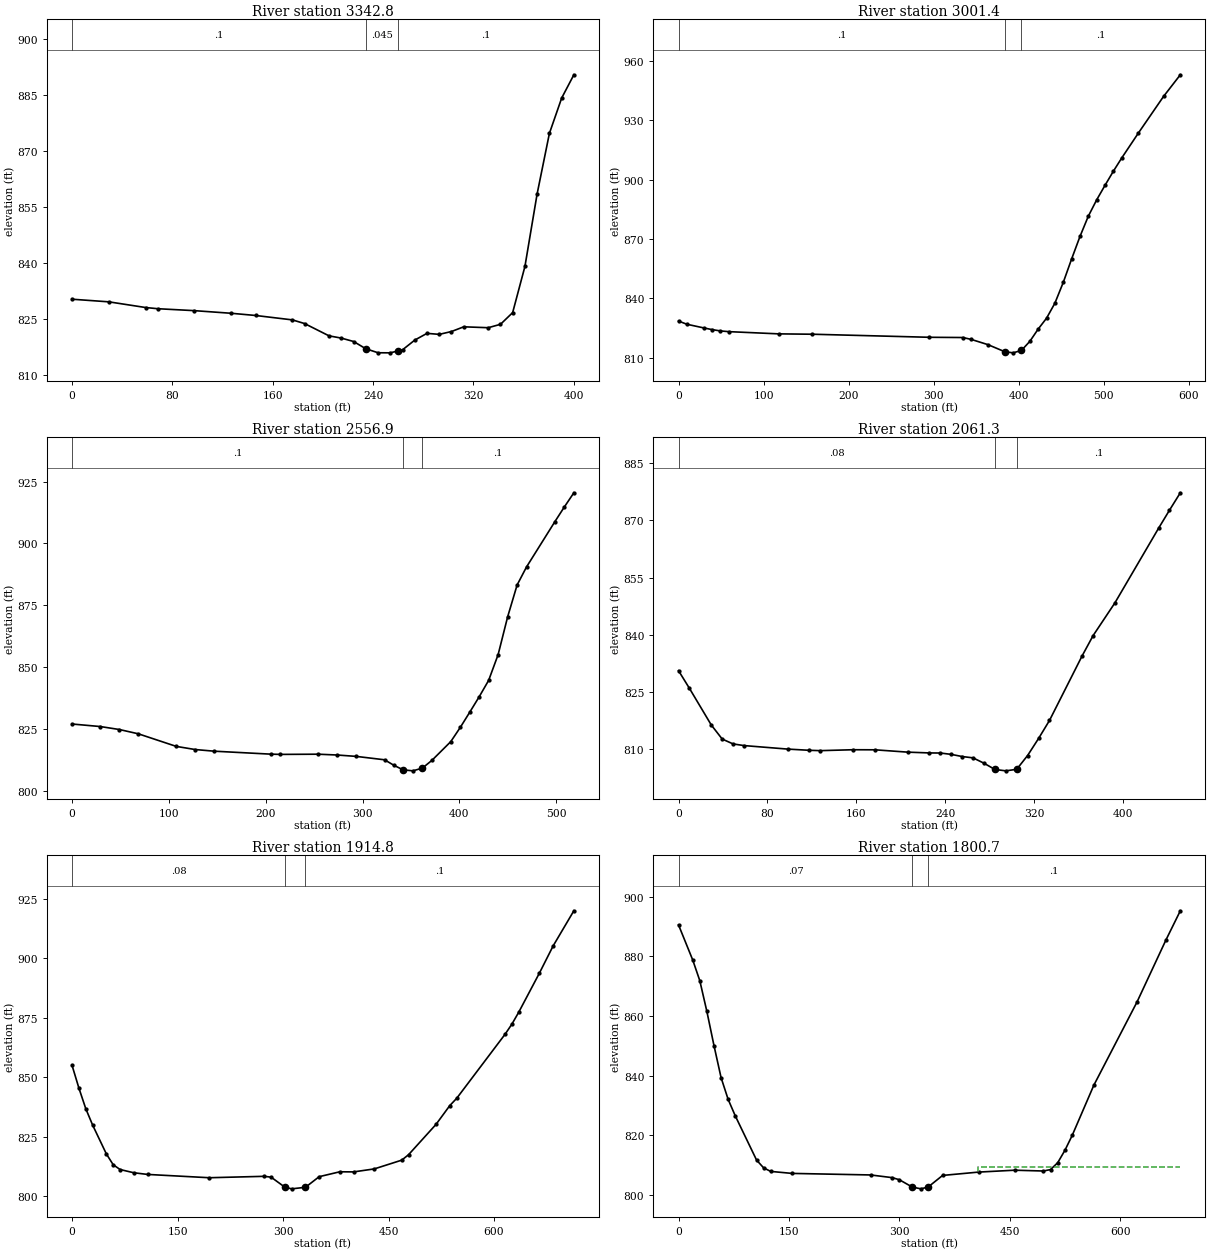
Type RM Length L Ch R = 1 ,3342.8  ,342.2,341.3,340.4
XS GIS Cut Line= 2
     1845487.038      478529.787     1845884.608      478574.926
#Sta/Elev= 30
       0  830.36    29.3  829.66    58.6  828.14    68.3  827.82    97.6   827.3
   126.9   826.6   146.4  826.01   175.7  824.83   185.4  823.85   204.9  820.56
   214.7  819.96   224.5  819.05   234.2  817.11     244  816.04   253.7  816.02
   260.2  816.56   263.5  816.83   273.3  819.44     283  821.23   292.8  820.96
   302.5  821.72   312.3  822.98   331.8  822.74   341.6  823.65   351.3  826.78
   361.1  839.15   370.8  858.51   380.6  874.71   390.4  884.17   400.1  890.38
#Mann= 3 , 0 , 0
       0      .1       0   234.2    .045       0   260.2      .1       0
Bank Sta=234.2,260.2
XS Rating Curve= 0 ,0
Exp/Cntr=0.3,0.1

Type RM Length L Ch R = 1 ,3001.4  ,463,444.6,425.5
XS GIS Cut Line= 2
      1845329.05      478870.495     1845917.591      478913.464
#Sta/Elev= 30
       0  828.48     9.8  826.86    29.5  825.02    39.3  824.16    49.2  823.48
      59  823.12     118  821.99   157.4  821.81     295  820.26   334.4  820.14
   344.2  819.19   363.9  816.53   383.6  812.97   393.4  812.39   403.2   813.6
   413.1  818.19   422.9   824.4   432.8  829.93   442.6  837.53   452.4     848
   462.2  859.82   472.1   871.3   481.9  881.55   491.8  889.88   501.6  897.22
   511.4  904.34   521.3  911.09   540.9  923.71   570.4  942.18   590.1  953.12
#Mann= 3 , 0 , 0
       0      .1       0   383.6    .045       0   403.2      .1       0
Bank Sta=383.6,403.2
XS Rating Curve= 0 ,0
Exp/Cntr=0.3,0.1

Type RM Length L Ch R = 1 ,2556.9  ,495,495.6,496.1
XS GIS Cut Line= 2
     1845590.334       479552.96     1845966.202       479196.19
#Sta/Elev= 30
       0  826.95    29.3  825.92    48.9  824.72    68.4  822.99   107.6   817.9
   127.1  816.63   146.7  815.96   205.3  814.76   215.1  814.66   254.2  814.74
   273.8  814.41   293.3  813.86   322.7  812.48   332.4  810.24   341.9  808.41
     352  808.01   361.8  809.13   371.6  812.24   391.1  819.83   400.9  825.57
   410.7  831.74   420.4  837.95   430.2   844.6     440  855.03   449.8  870.28
   459.6  883.19   469.3  890.47   498.7  908.86   508.4  914.76   518.2  920.48
#Mann= 3 , 0 , 0
       0      .1       0   341.9    .045       0   361.8      .1       0
Bank Sta=341.9,361.8
XS Rating Curve= 0 ,0
Exp/Cntr=0.3,0.1

Type RM Length L Ch R = 1 ,2061.3  ,125.1,146.5,167.4
XS GIS Cut Line= 2
      1845973.82      479861.804      1846308.89      479558.853
#Sta/Elev= 30
       0  830.59     9.8  825.97    29.5  816.35    39.3  812.68    49.1   811.4
    58.9  810.97    98.2  810.05   117.8  809.73   127.7  809.64   157.1  809.88
   176.8  809.86   206.2  809.25   225.9  809.04   235.7  809.02   245.5  808.66
   255.3   808.1   265.1  807.75     275  806.34   284.8  804.71   294.6  804.35
   304.4  804.75   314.2  808.36   324.1  812.83   333.9  817.54   363.3  834.47
   373.2  839.79   392.8  848.35   432.1   867.9   441.9  872.62   451.7   877.2
#Mann= 3 , 0 , 0
       0     .08       0   284.8    .045       0   304.4      .1       0
Bank Sta=284.8,304.4
XS Rating Curve= 0 ,0
Exp/Cntr=0.3,0.1

Type RM Length L Ch R = 1 ,1914.8  ,116.3,114,112.4
XS GIS Cut Line= 4
     1846023.299      479930.381     1846212.134      479775.998
     1846514.218      479800.303     1846641.959      479693.266
#Sta/Elev= 30
       0  854.93     9.8  845.33    19.5  836.75    29.3  829.82    48.8  817.72
    58.5  813.19    68.3  811.18    87.8  809.82   107.3  809.12   195.1  807.73
   273.2  808.32     283  807.98   302.6  803.76   312.3  803.06   331.9  803.71
   351.4  808.17   380.8  810.23   400.3  810.18   429.7  811.43   468.8  815.12
   478.5   817.4   517.6  830.16   537.2  838.07     547  841.12   615.6  867.97
   625.4  872.25   635.2   877.3   664.6  893.74   684.2  905.21   713.6  919.94
#Mann= 3 , 0 , 0
       0     .08       0   302.6    .045       0   331.9      .1       0
Bank Sta=302.6,331.9
XS Rating Curve= 0 ,0
Exp/Cntr=0.3,0.1

Type RM Length L Ch R = 1 ,1800.7  ,293.2,284.4,275.4
XS GIS Cut Line= 4
     1846058.587       479998.38     1846214.837      479869.908
      1846516.92      479894.213     1846654.796      479784.474
#Sta/Elev= 30
       0  890.48    19.3  878.73    28.9   871.8    38.5   861.5    48.2  850.02
    57.8  839.33    67.4  832.05    77.1  826.52     106  811.73   115.6  809.12
   125.2  807.94   154.1  807.27   260.9  806.75   290.3  805.85     300  805.14
   317.6  802.68   329.4   802.1   339.2  802.74   358.7  806.59   407.6  807.71
   456.5  808.34   495.6  808.07   505.3  808.55   515.1  810.87   524.9  815.03
   534.7  819.98   564.1  836.79   622.8  864.69     662  885.41   681.6  895.22
#Mann= 3 , 0 , 0
       0     .07       0   317.6    .045       0   339.2      .1       0
#XS Ineff= 2 , 0
                          407.17          809.28
Permanent Ineff=
       F       F
Bank Sta=317.6,339.2
XS Rating Curve= 0 ,0
Exp/Cntr=0.3,0.1

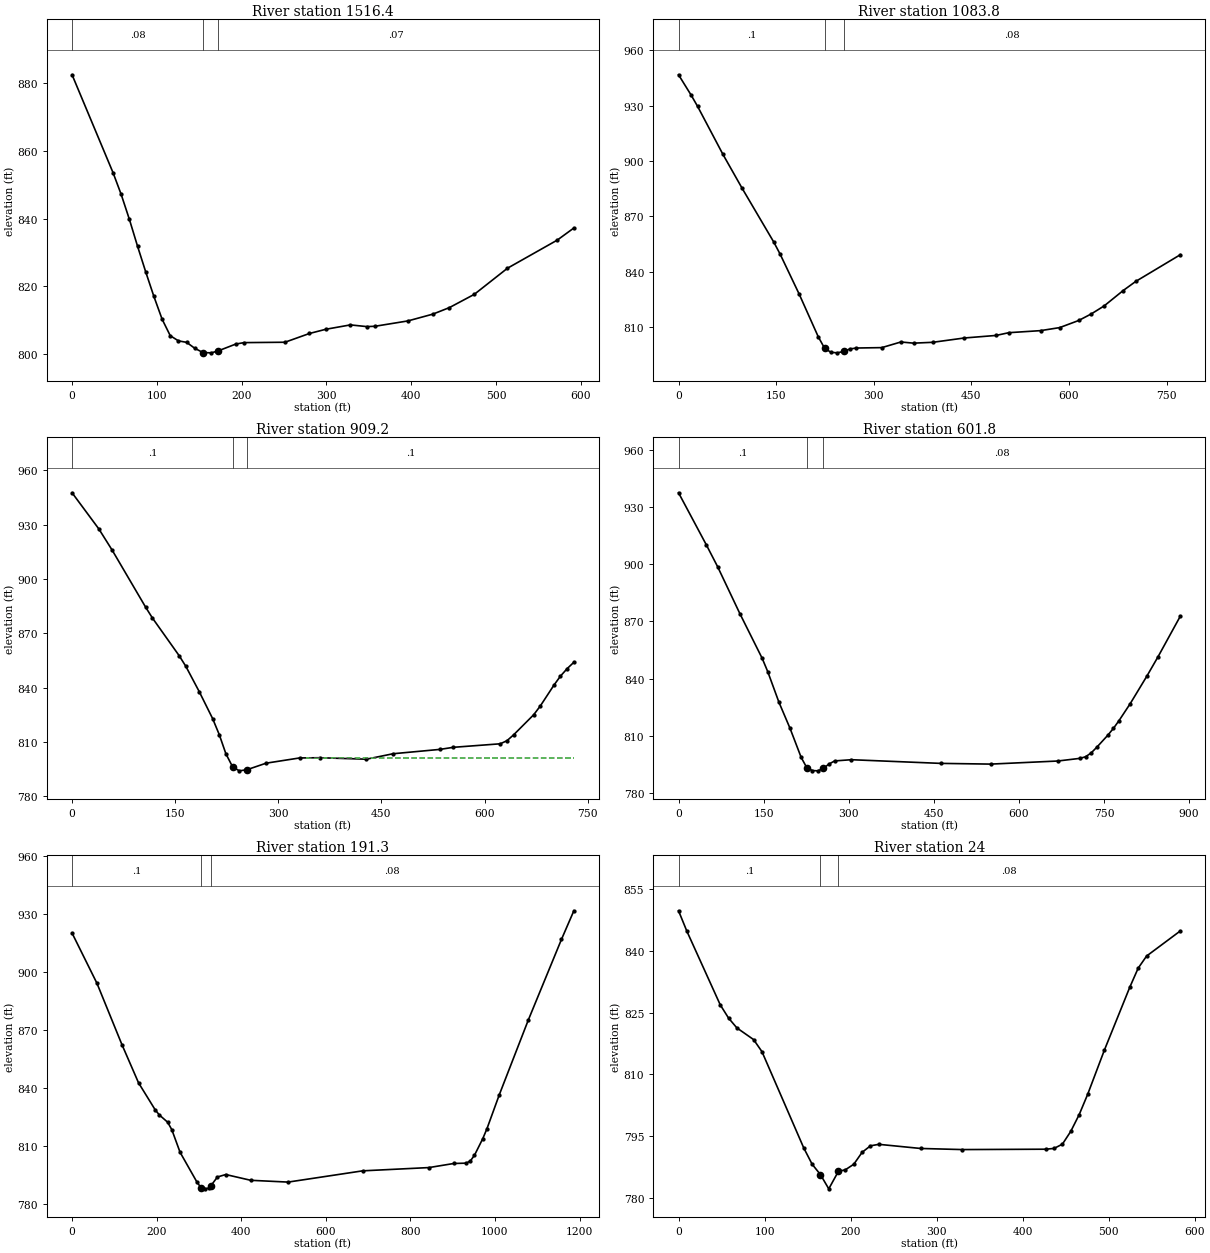
Type RM Length L Ch R = 1 ,1516.4  ,428.3,432.6,436.9
XS GIS Cut Line= 3
     1846255.265      480197.926     1846617.244      480094.627
     1846832.522      480092.891
#Sta/Elev= 30
       0  882.34    48.3  853.51    57.9  847.11    67.6  839.74    77.2  831.85
    86.9  824.24    96.5  817.04   106.2  810.33   115.8  805.48   125.5  803.96
   135.1  803.53   144.8  801.76   154.4  800.52   164.1  800.44   171.5  800.94
     193  803.02   202.7  803.45     251  803.56   279.9  806.14   299.2  807.38
   328.2  808.67   347.5  808.17   357.1  808.26     396  809.84   425.4  811.84
   444.9  813.76   474.3  817.67   513.4  825.36   572.1  833.64   591.7  837.21
#Mann= 3 , 0 , 0
       0     .08       0   154.4    .045       0   171.5     .07       0
Bank Sta=154.4,171.5
XS Rating Curve= 0 ,0
Exp/Cntr=0.3,0.1

Type RM Length L Ch R = 1 ,1083.8  ,163.9,174.5,184.9
XS GIS Cut Line= 2
     1846340.863      480568.225     1847109.369      480503.808
#Sta/Elev= 30
       0   946.7    19.5   935.6    29.3  929.57    68.3  903.53    97.6  885.27
   146.4  856.03   156.2  849.46   185.5  827.79   214.8  804.68   224.5  798.51
   234.3  796.32     244  796.03   253.8   796.8   263.6  798.15   273.3  798.64
   312.4  798.86   341.7  801.91   361.2  801.28   390.5  801.73   439.3  804.08
   488.1  805.46   507.6  806.95   556.4  808.06   585.7   809.7     615  813.56
   634.5  817.15   654.1  821.45   683.3  829.77   702.9  834.78   771.2   849.2
#Mann= 3 , 0 , 0
       0      .1       0   224.5    .045       0   253.8     .08       0
Bank Sta=224.5,253.8
XS Rating Curve= 0 ,0
Exp/Cntr=0.3,0.1

Type RM Length L Ch R = 1 ,909.2   ,293.9,307.4,320.9
XS GIS Cut Line= 2
     1846324.887       480628.58     1847001.971      480901.149
#Sta/Elev= 30
       0  947.67    38.9  927.71    58.4  915.91     107  884.43   116.8  878.48
   155.7  857.65   165.4  851.78   184.9  837.79   204.4  822.88   214.1  813.98
   223.8  803.33   233.6  796.11   243.3  793.95   254.4  794.57   282.2  798.18
   330.9  801.07   360.1   801.2   428.2  800.39   467.1  803.41   535.2  805.81
   554.7  806.96   622.8   808.9   632.6  810.61   642.3  813.86   671.5  824.97
   681.2  829.86   700.7   841.2   710.4  846.31   720.2  850.48   729.9  853.97
#Mann= 3 , 0 , 0
       0      .1       0   233.6    .045       0   254.4      .1       0
#XS Ineff= 2 , 0
                          340.15          801.26
Permanent Ineff=
       F       F
Bank Sta=233.6,254.4
XS Rating Curve= 0 ,0
Exp/Cntr=0.3,0.1

Type RM Length L Ch R = 1 ,601.8   ,411.7,410.5,409.1
XS GIS Cut Line= 2
      1846212.04      480737.955     1846705.096       481472.33
#Sta/Elev= 30
       0  937.62    49.1   910.2    68.8  898.83   108.1  874.12   147.4  850.64
   157.2  843.66   176.9   827.6   196.6  813.78   216.2  798.52     226  793.18
   235.9  791.65   245.7  791.49   255.5  792.85   265.4   795.1   275.2   796.7
   304.7  797.34   461.9  795.41   550.4  795.03   668.3  796.65   707.6  798.05
   717.5  798.89   727.3   800.9   737.1  803.84   756.8  810.25   766.6  813.82
   776.4  817.87   796.1  826.76   825.6   841.3   845.2  851.44   884.5  872.78
#Mann= 3 , 0 , 0
       0      .1       0     226    .045       0   255.5     .08       0
Bank Sta=226,255.5
XS Rating Curve= 0 ,0
Exp/Cntr=0.3,0.1

Type RM Length L Ch R = 1 ,191.3   ,154.7,167.3,179.8
XS GIS Cut Line= 3
     1845840.512      480948.024     1846166.901       481378.58
     1846793.637      481536.566
#Sta/Elev= 30
       0  920.24    58.9  894.25   117.9  862.56   157.2  842.78   196.5  828.84
   206.3  826.18   225.9  822.44   235.8  818.59   255.4  806.85   294.7  791.68
   304.5  788.61   314.4  787.95   324.2  788.39   328.1789.5166   343.8  794.09
   363.5  795.35   422.4  792.37   510.8  791.44   687.2  797.26   843.9  798.95
   902.6  801.06     932  801.24   941.8  802.36   951.6  805.33   971.2   813.9
     981     819  1010.4  836.69  1078.9  875.28  1157.2  916.93  1186.6  931.78
#Mann= 3 , 0 , 0
       0      .1       0   304.5    .045       0   328.1     .08       0
#XS Ineff= 2 , 0
                          363.58          794.44
Permanent Ineff=
       F       F
Bank Sta=304.5,328.1
XS Rating Curve= 0 ,0
Exp/Cntr=0.3,0.1

Type RM Length L Ch R = 1 ,24      ,26.9,24,21.1
BEGIN DESCRIPTION:
Invert manually set at 782.3 to match effective invert at XS BQ.
END DESCRIPTION:
XS GIS Cut Line= 3
      1845859.87      481079.896     1845901.817      481534.076
     1845865.048      481656.026
#Sta/Elev= 30
       0  849.65     9.7   844.7    48.5  826.87    58.2  823.65    67.9  821.27
    87.3  818.45      97  815.53   145.6  792.21   155.3  788.28     165  785.75
   174.7   782.3   185.8   786.5   194.1  786.93   203.8  788.26   213.5  791.15
   223.2  792.72   232.9  793.08   281.4  792.08     330  791.81     427   791.9
   436.7  792.09   446.4  793.13   456.1  796.22   465.9  800.28   475.7  805.16
   495.3  815.96   524.7  831.12   534.5  835.76   544.3  838.69   583.5  844.77
#Mann= 3 , 0 , 0
       0      .1       0     165    .045       0   185.8     .08       0
Bank Sta=165,185.8
XS Rating Curve= 0 ,0
Exp/Cntr=0.3,0.1

Chan Stop Cuts=-1
Use User Specified Reach Order=0
Composite Channel Slope=5

--- CAMPBLSCK.g02 (geometry) ---

Geom Title=USGS 10m DEM_copy
Program Version=4.10

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
River Reach=CAMPBLSCK       ,Main
Reach XY= 30
     1854425.086      476782.412     1853851.318      476703.422
     1853275.797      476843.179     1853067.898       476822.78
     1852554.002      477026.779     1852419.026      476867.484
     1852246.717      476827.988     1851816.595      476535.887
     1851709.407      475834.411     1851501.452      475499.012
     1851264.314      475510.481      1850753.59      475354.893
     1850506.986       475151.07     1850141.647      475108.994
     1849740.705      475290.247     1849463.657      475651.987
     1849291.559      476068.143     1849155.436      476159.761
     1848475.303      476099.126     1848211.091      475971.528
     1848041.453      475779.742     1847395.789      475761.625
      1846550.65      476542.528     1845766.825      477701.683
     1845812.398      478191.049     1845729.933      479091.657
     1846332.146      479867.482     1846576.415      480568.723
     1846486.163      480832.848     1845966.717       481250.06

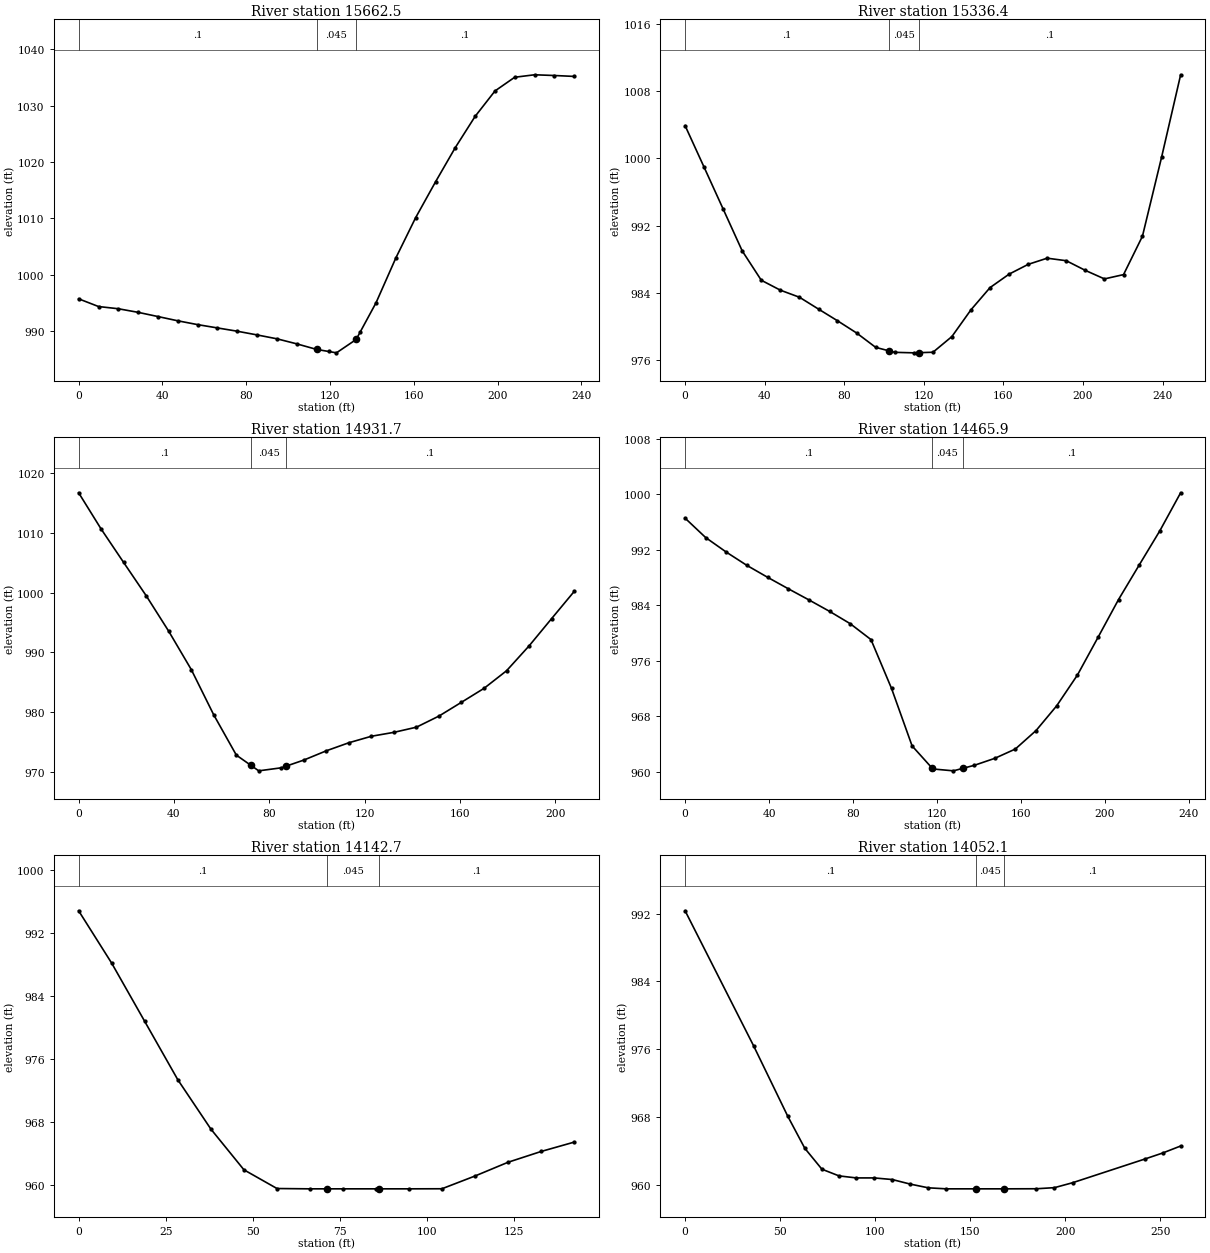
Type RM Length L Ch R = 1 ,15662.5 ,324.5,326.1,326.9
XS GIS Cut Line= 2
     1854423.479      476653.958     1854407.507      476890.069
#Sta/Elev= 28
       0   995.7     9.5  994.33    18.9  993.94    28.4   993.3    37.9  992.55
    47.3   991.8    56.8  991.12    66.3  990.53    75.7  989.95    85.2  989.29
    94.7   988.6   104.1  987.71   113.6  986.72   119.4  986.35   123.1  986.11
   132.5  988.48   134.4  989.78     142     995   151.5 1002.99   160.9  1010.1
   170.4 1016.46   179.8 1022.52   189.3 1028.08   198.8  1032.6   208.2 1035.03
   217.7 1035.47   227.2 1035.34   236.6 1035.18
#Mann= 3 , 0 , 0
       0      .1       0   113.6    .045       0   132.5      .1       0
Bank Sta=113.6,132.5
XS Rating Curve= 0 ,0
Exp/Cntr=0.3,0.1

Type RM Length L Ch R = 1 ,15336.4 ,409.8,404.8,399.4
XS GIS Cut Line= 2
     1854114.451      476664.374     1854083.895      476911.596
#Sta/Elev= 29
       0 1003.88     9.6  998.92    19.2  993.94    28.7  989.01    38.3  985.52
    47.9  984.34    57.5   983.5    67.1  982.09    76.6  980.71    86.2  979.26
    95.8  977.55   102.6  977.13   105.4  976.96     115   976.9   117.6  976.92
   124.6  976.97   134.1  978.83   143.7  982.01   153.3  984.65   162.9  986.25
   172.5  987.41     182  988.14   191.6  987.84   201.2  986.69   210.8  985.68
   220.4  986.19   229.9  990.75   239.5 1000.11   249.1 1009.92
#Mann= 3 , 0 , 0
       0      .1       0   102.6    .045       0   117.6      .1       0
Bank Sta=102.6,117.6
XS Rating Curve= 0 ,0
Exp/Cntr=0.3,0.1

Type RM Length L Ch R = 1 ,14931.7 ,463.9,465.8,467.6
XS GIS Cut Line= 2
     1853709.243      476651.874     1853730.076      476858.819
#Sta/Elev= 25
       0  1016.7     9.4 1010.66    18.9 1005.03    28.4  999.44    37.8  993.53
    47.3  987.09    56.7  979.53    66.2  972.78    72.2   971.1    75.6  970.15
    85.1  970.66    87.2  970.95    94.5  971.95     104  973.51   113.4  974.85
   122.9  975.94   132.4   976.6   141.8  977.46   151.3  979.33   160.7  981.63
   170.2  983.97   179.6   986.9   189.1  991.08   198.5  995.62     208 1000.18
#Mann= 3 , 0 , 0
       0      .1       0    72.2    .045       0    87.2      .1       0
Bank Sta=72.2,87.2
XS Rating Curve= 0 ,0
Exp/Cntr=0.3,0.1

Type RM Length L Ch R = 1 ,14465.9 ,331.4,323.2,314.6
XS GIS Cut Line= 2
     1853264.798      476718.541     1853269.659      476954.652
#Sta/Elev= 27
       0  996.57     9.8  993.78    19.7  991.67    29.5  989.76    39.4  988.04
    49.2   986.4      59   984.8    68.9  983.14    78.7  981.37    88.6  979.08
    98.4  972.04   108.2  963.76   117.5  960.64   118.1  960.44   127.9  960.17
   132.5  960.54   137.8  960.96   147.6  961.97   157.4  963.31   167.3  965.98
   177.1  969.53     187  973.97   196.8  979.39   206.6  984.85   216.5  989.85
   226.3  994.76   236.2 1000.23
#Mann= 3 , 0 , 0
       0      .1       0   117.5    .045       0   132.5      .1       0
Bank Sta=117.5,132.5
XS Rating Curve= 0 ,0
Exp/Cntr=0.3,0.1

Type RM Length L Ch R = 1 ,14142.7 ,118.3,90.6,60.5
XS GIS Cut Line= 2
     1852933.479       476801.55     1852986.951      476933.495
#Sta/Elev= 18
       0  994.85     9.5  988.19      19  980.78    28.5  973.37      38   967.1
    47.5  961.92      57  959.54    66.4   959.5    71.4   959.5    75.9   959.5
    85.4   959.5    86.4   959.5    94.9   959.5   104.4  959.51   113.9  961.13
   123.4  962.88   132.9  964.25   142.4  965.44
#Mann= 3 , 0 , 0
       0      .1       0    71.4    .045       0    86.4      .1       0
Bank Sta=71.4,86.4
XS Rating Curve= 0 ,0
Exp/Cntr=0.3,0.1

Type RM Length L Ch R = 1 ,14052.1 ,64.4,47.5,53.8
XS GIS Cut Line= 3
     1852788.998      476811.529     1852811.483      476898.733
     1852979.285      476930.164
#Sta/Elev= 20
       0  992.35      36  976.42      54  968.09      63  964.29      72  961.82
      81  961.03    90.1  960.79    99.5  960.79     109   960.6   118.5  960.06
     128  959.62   137.5   959.5     153   959.5     168   959.5   184.9  959.51
   194.4  959.64   203.9  960.22   241.8  963.01   251.3  963.73   260.8  964.56
#Mann= 3 , 0 , 0
       0      .1       0     153    .045       0     168      .1       0
Bank Sta=153,168
XS Rating Curve= 0 ,0
Exp/Cntr=0.3,0.1

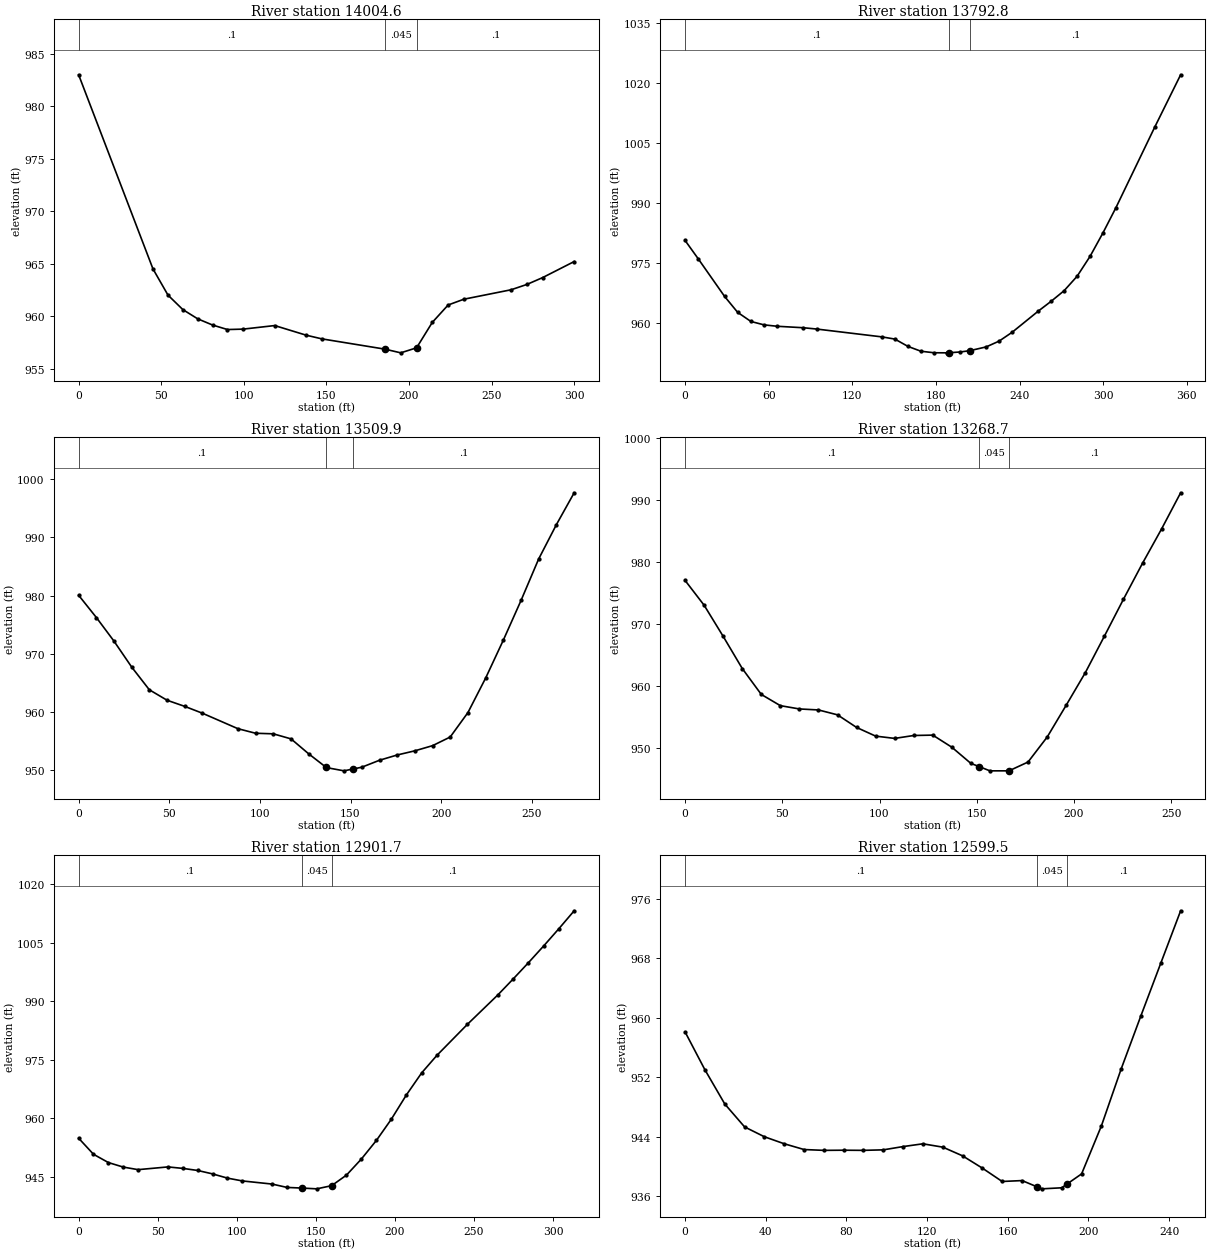
Type RM Length L Ch R = 1 ,14004.6 ,163.8,211.7,238.1
XS GIS Cut Line= 3
     1852705.689      476826.103     1852733.271      476911.878
     1852936.786      476963.155
#Sta/Elev= 21
       0  983.02      45  964.52    54.1  962.02    63.1  960.64    72.1  959.76
    81.1  959.17    90.1  958.74    99.6  958.78   118.7  959.12   137.8   958.2
   147.3  957.85   185.5  956.87     195  956.52   204.6     957   214.1  959.42
   223.7  961.08   233.2  961.63   261.8  962.53   271.4  963.04   280.9  963.69
     300  965.22
#Mann= 3 , 0 , 0
       0      .1       0   185.5    .045       0   204.6      .1       0
Bank Sta=185.5,204.6
XS Rating Curve= 0 ,0
Exp/Cntr=0.3,0.1

Type RM Length L Ch R = 1 ,13792.8 ,262.9,282.9,302.2
XS GIS Cut Line= 4
     1852647.645      476819.745     1852629.312      476931.411
      1852667.09      477066.411     1852641.534        477165.3
#Sta/Elev= 30
       0  980.64     9.4  976.08    28.3   966.7    37.7  962.71    47.2  960.44
    56.6  959.59      66  959.24    84.9  958.87    94.3  958.55   141.2  956.59
   150.5  956.04   159.9  954.21   169.2  953.01   178.6  952.63   187.9  952.61
   189.4  952.64   197.3  952.82   204.4  953.16     216  954.09   225.3  955.54
   234.7  957.76   253.4  963.03   262.6  965.47   271.9  968.11   281.2   971.7
   290.5  976.67   299.8  982.55   309.1  988.84   336.9 1008.91   355.5 1021.98
#Mann= 3 , 0 , 0
       0      .1       0   189.4    .045       0   204.4      .1       0
Bank Sta=189.4,204.4
XS Rating Curve= 0 ,0
Exp/Cntr=0.3,0.1

Type RM Length L Ch R = 1 ,13509.9 ,242,241.1,240.4
XS GIS Cut Line= 2
     1852525.587      476769.015     1852370.815      476994.363
#Sta/Elev= 30
       0  980.05     9.8  976.22    19.5  972.17    29.3   967.7      39  963.81
    48.8  962.01    58.6  960.95    68.3  959.78    87.9  957.12    97.6  956.34
   107.4  956.24   117.2  955.37   126.9  952.81   136.3  950.54   136.7  950.44
   146.4  949.88   151.3  950.19   156.2   950.5     166   951.7   175.7   952.6
   185.5  953.32   195.3  954.21     205  955.69   214.8   959.9   224.6  965.85
   234.3  972.33   244.1  979.17   253.8  986.28   263.6  992.19   273.4  997.66
#Mann= 3 , 0 , 0
       0      .1       0   136.3    .045       0   151.3      .1       0
Bank Sta=136.3,151.3
XS Rating Curve= 0 ,0
Exp/Cntr=0.3,0.1

Type RM Length L Ch R = 1 ,13268.7 ,363.5,367,369.9
XS GIS Cut Line= 2
     1852304.868      476673.633     1852171.534      476890.856
#Sta/Elev= 29
       0  977.06     9.8  973.06    19.6  968.04    29.4  962.86    39.2  958.68
      49  956.87    58.8  956.34    68.6  956.18    78.4  955.39    88.2  953.36
      98  951.96   107.8  951.59   117.6  952.06   127.4  952.12   137.2  950.17
     147  947.56   151.2  947.05   156.8  946.36   166.2  946.36   166.6  946.36
   176.4  947.78   186.3  951.83   196.1  956.98   205.9  962.21   215.7  968.09
   225.5  974.04   235.3  979.84   245.1  985.37   254.9   991.2
#Mann= 3 , 0 , 0
       0      .1       0   151.2    .045       0   166.6      .1       0
Bank Sta=151.2,166.6
XS Rating Curve= 0 ,0
Exp/Cntr=0.3,0.1

Type RM Length L Ch R = 1 ,12901.7 ,288.1,302.2,316.4
XS GIS Cut Line= 3
     1852014.868      476491.967     1851888.757      476644.189
     1851860.423      476756.411
#Sta/Elev= 30
       0  954.94     9.4  950.82    18.8   948.7    28.2  947.54    37.6  946.88
    56.5  947.58    65.9   947.2    75.3  946.67    84.7  945.79    94.1  944.71
   103.5  943.99   122.4  943.18   131.8  942.32   141.2  942.16   150.6  941.96
     160  942.77   169.4  945.48   178.8  949.59   188.3  954.36   197.7  959.77
   207.3  966.04     217  971.71   226.6  976.18   245.9  984.14   265.2   991.7
   274.8  995.75   284.5  999.94   294.1 1004.22   303.8 1008.68   313.4 1013.24
#Mann= 3 , 0 , 0
       0      .1       0   141.2    .045       0     160      .1       0
Bank Sta=141.2,160
XS Rating Curve= 0 ,0
Exp/Cntr=0.3,0.1

Type RM Length L Ch R = 1 ,12599.5 ,246.6,248.6,250.4
XS GIS Cut Line= 2
     1851934.677       476325.89     1851696.829      476387.522
#Sta/Elev= 28
       0   958.1     9.8  953.03    19.7  948.41    29.5  945.34    39.3  944.02
    49.1  943.08      59   942.3    68.8  942.19    78.6  942.21    88.4  942.19
    98.3  942.26   108.1   942.7   117.9  943.07   127.8  942.62   137.6  941.45
   147.4   939.8   157.2  938.01   167.1  938.13   174.5  937.29   176.9  937.02
   186.7  937.16   189.5  937.69   196.6  939.03   206.4  945.47   216.2  953.12
     226  960.27   235.9  967.37   245.7  974.38
#Mann= 3 , 0 , 0
       0      .1       0   174.5    .045       0   189.5      .1       0
Bank Sta=174.5,189.5
XS Rating Curve= 0 ,0
Exp/Cntr=0.3,0.1

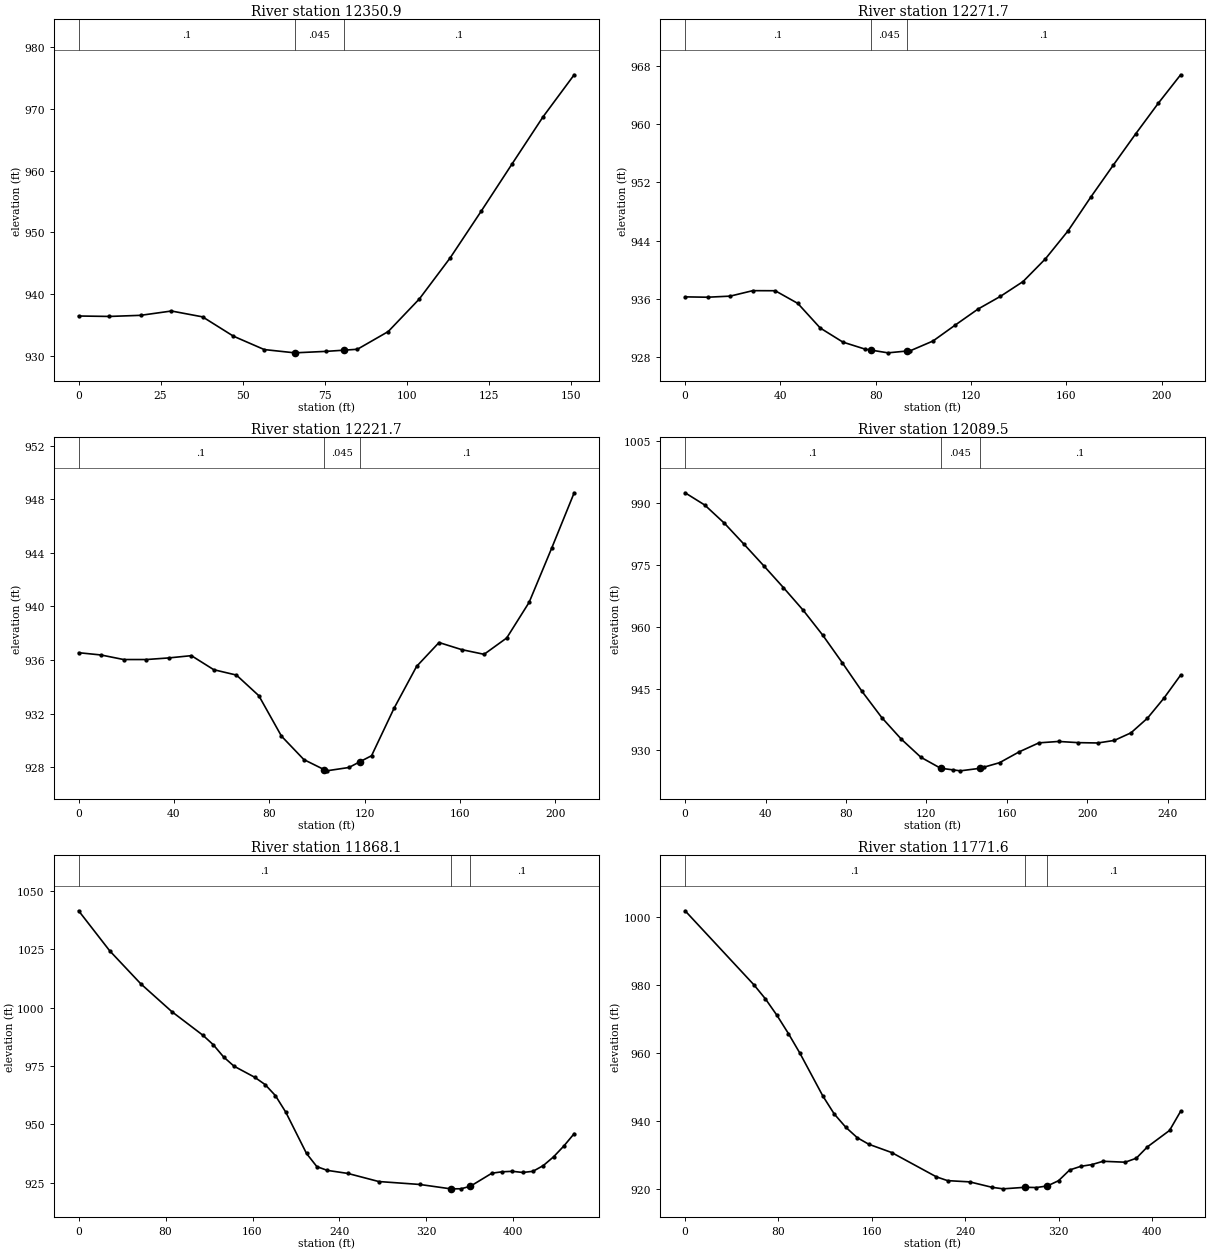
Type RM Length L Ch R = 1 ,12350.9 ,57.1,79.2,100.9
XS GIS Cut Line= 2
     1851779.659      476116.249      1851630.77      476141.805
#Sta/Elev= 18
       0  936.44     9.4  936.37    18.9  936.55    28.3  937.25    37.8   936.3
    47.2  933.17    56.6     931    65.9  930.47    75.5  930.71    80.9   930.9
      85  931.05    94.4  933.92   103.9  939.21   113.3  945.87   122.7  953.39
   132.2  961.12   141.6  968.72   151.1  975.54
#Mann= 3 , 0 , 0
       0      .1       0    65.9    .045       0    80.9      .1       0
Bank Sta=65.9,80.9
XS Rating Curve= 0 ,0
Exp/Cntr=0.3,0.1

Type RM Length L Ch R = 1 ,12271.7 ,51.1,50,50.6
XS GIS Cut Line= 2
     1851769.029      476102.485     1851605.183      475974.446
#Sta/Elev= 25
       0   936.3     9.4  936.25    18.9   936.4    28.4  937.15    37.8  937.14
    47.3   935.4    56.7  932.03    66.2   930.1    75.6  929.13    78.1     929
    85.1  928.63    93.1  928.88    94.5  928.92     104  930.25   113.4  932.45
   122.9  934.63   132.3  936.37   141.8   938.4   151.2  941.52   160.7  945.36
   170.1  949.92   179.6  954.33     189  958.62   198.5  962.82   207.9  966.73
#Mann= 3 , 0 , 0
       0      .1       0    78.1    .045       0    93.1      .1       0
Bank Sta=78.1,93.1
XS Rating Curve= 0 ,0
Exp/Cntr=0.3,0.1

Type RM Length L Ch R = 1 ,12221.7 ,151.5,132.3,111
XS GIS Cut Line= 2
      1851788.56      476067.762     1851624.715      475939.724
#Sta/Elev= 25
       0  936.54     9.4  936.37    18.9  936.03    28.4  936.03    37.8  936.15
    47.3  936.32    56.7  935.27    66.2  934.87    75.6  933.33    85.1  930.31
    94.5  928.56   102.9  927.82     104  927.72   113.4  927.97   117.9  928.39
   122.9  928.85   132.3  932.38   141.8  935.52   151.2   937.3   160.7  936.77
   170.1  936.42   179.6  937.64     189   940.3   198.5  944.36   207.9  948.48
#Mann= 3 , 0 , 0
       0      .1       0   102.9    .045       0   117.9      .1       0
Bank Sta=102.9,117.9
XS Rating Curve= 0 ,0
Exp/Cntr=0.3,0.1

Type RM Length L Ch R = 1 ,12089.5 ,230.4,221.3,212.2
XS GIS Cut Line= 3
     1851852.188      475854.936     1851648.022      475876.463
     1851608.785      475888.963
#Sta/Elev= 29
       0  992.52     9.8  989.54    19.6  985.11    29.3  980.04    39.1  974.83
    48.9  969.52    58.7  964.05    68.4  958.02    78.2  951.28      88  944.34
    97.8     938   107.5  932.77   117.3  928.35   127.1  925.69   133.5  925.28
   136.9  925.06   146.6  925.67   148.5  925.93   156.4  927.03   166.2  929.67
     176  931.85   185.8  932.19   195.5   931.9   205.3  931.82   213.5  932.44
   221.8  934.28     230  937.84   238.2   942.7   246.5  948.29
#Mann= 3 , 0 , 0
       0      .1       0   127.1    .045       0   146.6      .1       0
Bank Sta=127.1,146.6
XS Rating Curve= 0 ,0
Exp/Cntr=0.3,0.1

Type RM Length L Ch R = 1 ,11868.1 ,102,96.5,91
XS GIS Cut Line= 3
     1851951.494       475627.05     1851723.022      475615.245
     1851524.411      475725.662
#Sta/Elev= 30
       0  1041.6    28.6 1024.43    57.2 1010.28    85.8  998.34   114.4  988.21
   123.9  984.16   133.4  978.92     143  974.96     162  970.22   171.6  967.08
   181.1  962.34   190.6  955.26   209.7  937.54   219.2   931.9   228.8  930.29
   247.7  928.98   276.1  925.51     314  924.24   342.4  922.37   351.9   922.4
   360.5  923.49   380.3  929.08   389.7  929.68   399.2  929.88   408.7  929.39
   418.1  929.89   427.6  932.35   437.1  936.12   446.6  940.79     456  946.04
#Mann= 3 , 0 , 0
       0      .1       0   342.4    .045       0   360.5      .1       0
Bank Sta=342.4,360.5
XS Rating Curve= 0 ,0
Exp/Cntr=0.3,0.1

Type RM Length L Ch R = 1 ,11771.6 ,237.6,215.4,192.7
XS GIS Cut Line= 3
     1851666.077      475326.356      1851650.92      475512.595
     1851477.189      475674.967
#Sta/Elev= 30
       0 1001.97      59  980.14    68.8  976.02    78.7  971.16    88.5   965.8
    98.3  960.04     118   947.4   127.8  942.08   137.7  938.16   147.5   935.1
   157.4  933.16     177  930.72   215.4  923.54   224.9  922.44   243.9  922.07
     263  920.47   272.5  920.02   291.5  920.48     301   920.4   310.5  920.89
     320  922.42   329.5  925.58     339  926.65   348.6  927.17   358.1  928.14
   377.1  927.87   386.6  929.04   396.1  932.38   415.1  937.23   424.6  942.88
#Mann= 3 , 0 , 0
       0      .1       0   291.5    .045       0   310.5      .1       0
Bank Sta=291.5,310.5
XS Rating Curve= 0 ,0
Exp/Cntr=0.3,0.1