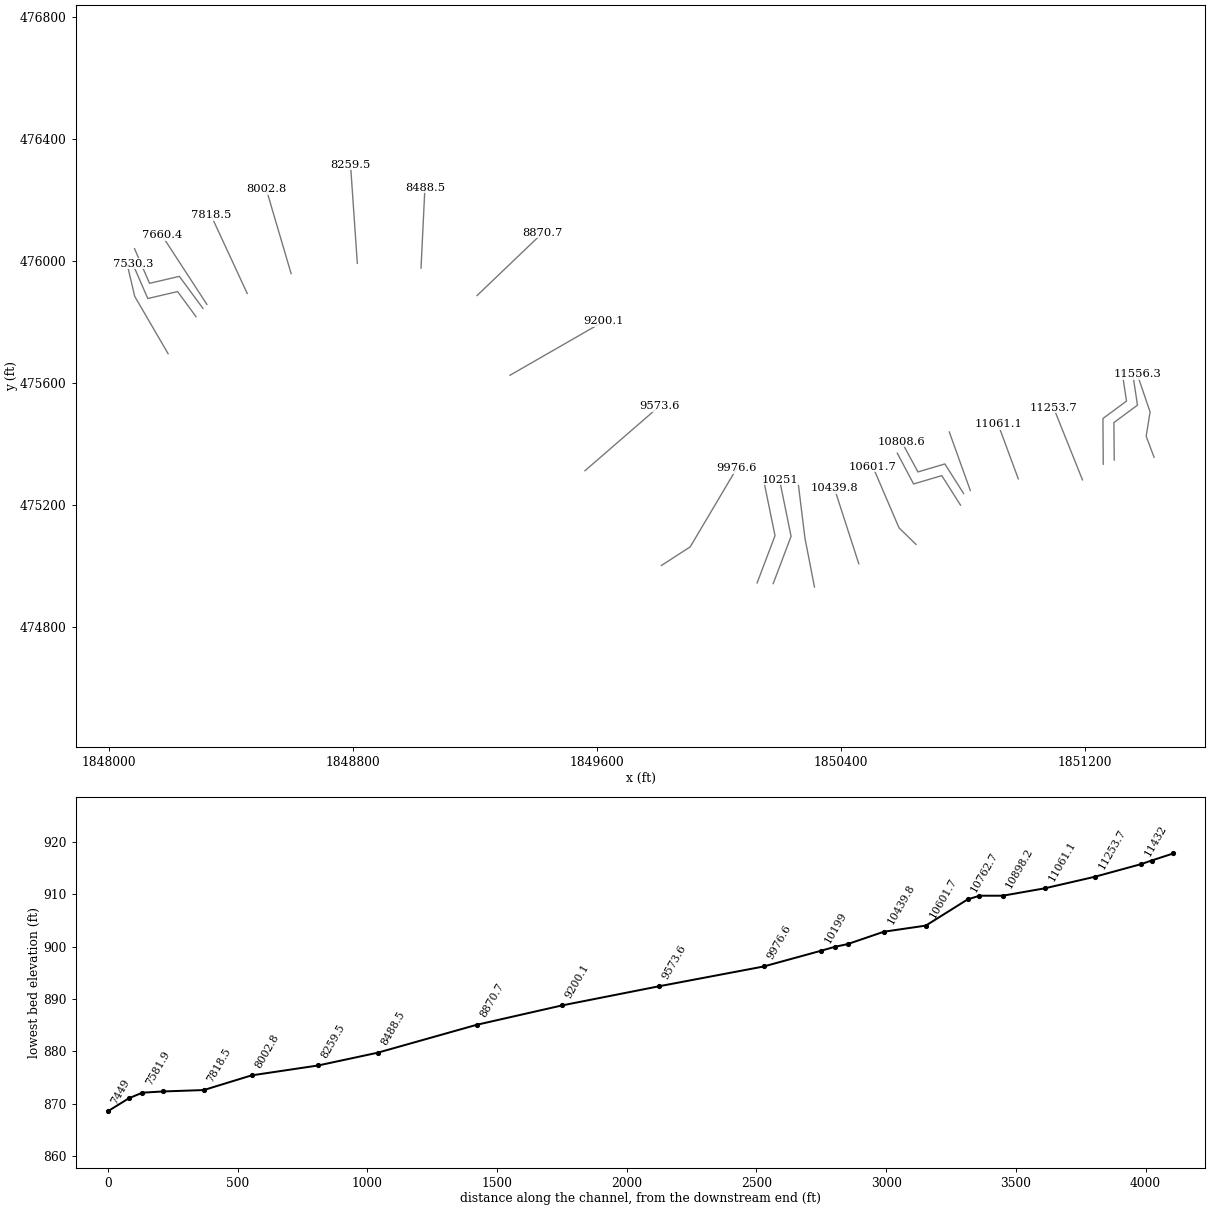
HEC-RAS study CAMPBLSCK.prj: CAMPBLSCK

--- CAMPBLSCK.g02 (geometry) --- (continued)

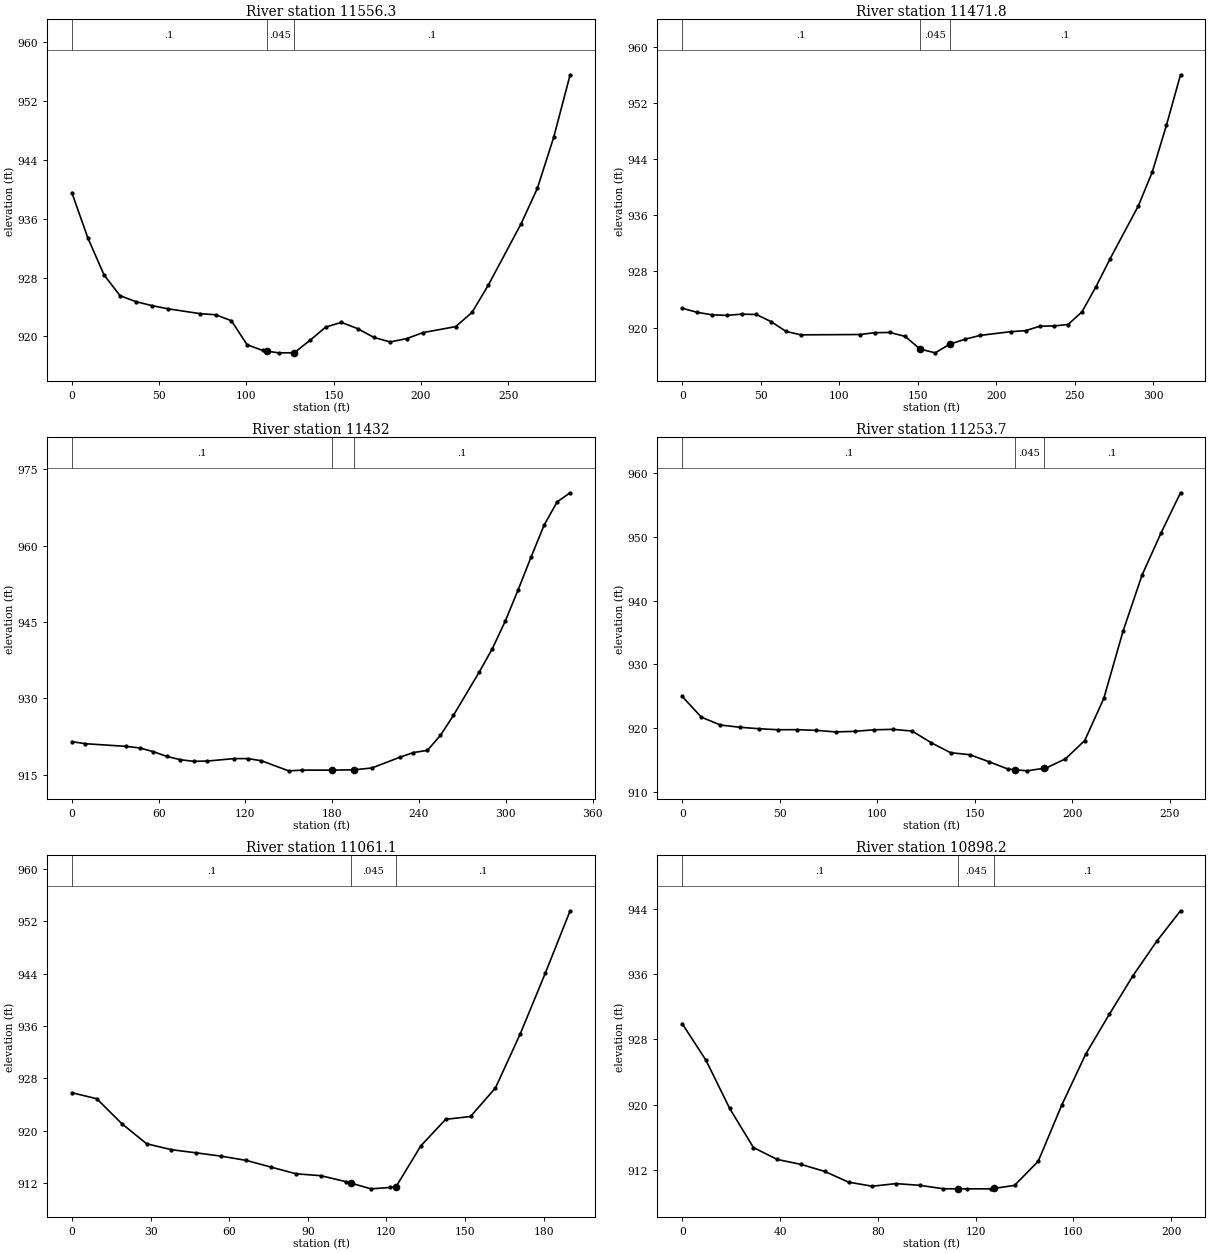
Type RM Length L Ch R = 1 ,11556.3 ,104.2,84.5,64.8
XS GIS Cut Line= 4
     1851426.784      475356.961      1851400.88      475425.705
     1851413.728      475505.566     1851371.391      475629.662
#Sta/Elev= 30
       0  939.51     9.2  933.34    18.4  928.36    27.6  925.53    36.7  924.72
    45.9  924.18    55.1  923.75    73.5  923.09    82.4  922.94    91.4  922.13
   100.4  918.87   109.4  918.09   111.6  918.01   118.4  917.77   127.4  917.78
   136.4  919.46   145.4  921.26   154.4  921.91   163.7  921.06   173.1  919.86
   182.4  919.25   191.8   919.7   201.2  920.52   219.9  921.33   229.3  923.26
   238.6  926.96   257.4   935.3   266.7  940.09   276.1  947.05   285.5  955.53
#Mann= 3 , 0 , 0
       0      .1       0   111.6    .045       0   127.4      .1       0
Bank Sta=111.6,127.4
XS Rating Curve= 0 ,0
Exp/Cntr=0.3,0.1

Type RM Length L Ch R = 1 ,11471.8 ,45.8,39.8,39.7
XS GIS Cut Line= 4
     1851296.115      475347.966     1851295.095      475470.725
     1851372.338      475527.873     1851357.662      475625.401
#Sta/Elev= 30
       0  922.76     9.4  922.18    18.9  921.83    28.3  921.74    37.8  921.92
    47.2  921.87    56.7  920.84    66.1  919.46    75.6  918.97   113.3  919.02
   122.8  919.28   132.4  919.31     142  918.75   151.6  916.94   161.2  916.41
   170.3  917.63   180.4  918.36     190   918.9   209.2  919.42   218.8  919.57
   227.8   920.2   236.8  920.24   245.8  920.44   254.7  922.24   263.7  925.85
   272.6  929.79   290.6  937.32   299.5  942.15   308.5  948.79   317.5     956
#Mann= 3 , 0 , 0
       0      .1       0   151.6    .045       0   170.3      .1       0
Bank Sta=151.6,170.3
XS Rating Curve= 0 ,0
Exp/Cntr=0.3,0.1

Type RM Length L Ch R = 1 ,11432   ,140.1,178.3,210.2
XS GIS Cut Line= 4
     1851260.133      475334.236     1851259.114      475483.981
     1851336.357      475541.129      1851321.68      475638.657
#Sta/Elev= 30
       0  921.46     9.4  921.06    37.4  920.54    46.8  920.23    56.2  919.51
    65.5  918.58    74.9  917.92    84.2   917.6    93.6  917.65   112.3  918.14
   121.7  918.13     131  917.72   149.8  915.73   159.4  915.87   179.9  915.87
   194.9  915.93   207.4  916.29   226.6  918.38   236.2  919.33   245.8  919.75
   254.8  922.68   263.8  926.63   281.7  935.16   290.7  939.73   299.6  945.12
   308.6  951.33   317.6  957.81   326.5  964.01   335.5  968.57   344.5  970.37
#Mann= 3 , 0 , 0
       0      .1       0   179.9    .045       0   194.9      .1       0
Bank Sta=179.9,194.9
XS Rating Curve= 0 ,0
Exp/Cntr=0.3,0.1

Type RM Length L Ch R = 1 ,11253.7 ,193.1,192.5,191.8
XS GIS Cut Line= 2
     1851192.047      475282.799     1851097.015      475519.941
#Sta/Elev= 29
       0  924.97     9.8  921.73    19.6   920.5    29.5  920.15    39.3  919.92
    49.1  919.76      59  919.77    68.8  919.66    78.6  919.42    88.4  919.51
    98.3  919.75   108.1  919.82   117.9  919.55   127.7  917.72   137.6  916.16
   147.4  915.85   157.2  914.76     167   913.6   170.4   913.5   176.9  913.32
   185.4  913.72   186.7  913.78   196.5   915.2   206.4  918.07   216.2   924.7
     226  935.17   235.8  944.01   245.6  950.64   255.5  956.89
#Mann= 3 , 0 , 0
       0      .1       0   170.4    .045       0   185.4      .1       0
Bank Sta=170.4,185.4
XS Rating Curve= 0 ,0
Exp/Cntr=0.3,0.1

Type RM Length L Ch R = 1 ,11061.1 ,163,162.9,162.8
XS GIS Cut Line= 2
     1850981.607      475286.061     1850915.773      475464.394
#Sta/Elev= 23
       0  925.81     9.5  924.89      19   921.1    28.5  918.01      38   917.1
    47.5  916.62      57  916.11    66.5  915.47      76  914.44    85.5  913.42
      95  913.13   104.6  912.21   106.5  911.99   114.1  911.12   121.5  911.33
   123.6  911.39   133.1  917.67   142.6  921.74   152.1  922.18   161.6  926.54
   171.1  934.83   180.6  944.06   190.1  953.62
#Mann= 3 , 0 , 0
       0      .1       0   106.5    .045       0   123.6      .1       0
Bank Sta=106.5,123.6
XS Rating Curve= 0 ,0
Exp/Cntr=0.3,0.1

Type RM Length L Ch R = 1 ,10898.2 ,47.4,89.6,128.7
XS GIS Cut Line= 2
     1850824.242      475248.148     1850755.343      475440.002
#Sta/Elev= 24
       0  929.91     9.7  925.44    19.4  919.54    29.1  914.76    38.8   913.3
    48.5   912.7    58.2  911.84      68  910.52    77.7  910.02    87.4  910.34
    97.1  910.13   106.8  909.71   112.7   909.7   116.5   909.7   126.2   909.7
   127.7  909.76   135.9  910.12   145.6  913.08   155.3     920     165  926.18
   174.7  931.08   184.4  935.81   194.1  940.02   203.8  943.74
#Mann= 3 , 0 , 0
       0      .1       0   112.7    .045       0   127.7      .1       0
Bank Sta=112.7,127.7
XS Rating Curve= 0 ,0
Exp/Cntr=0.3,0.1

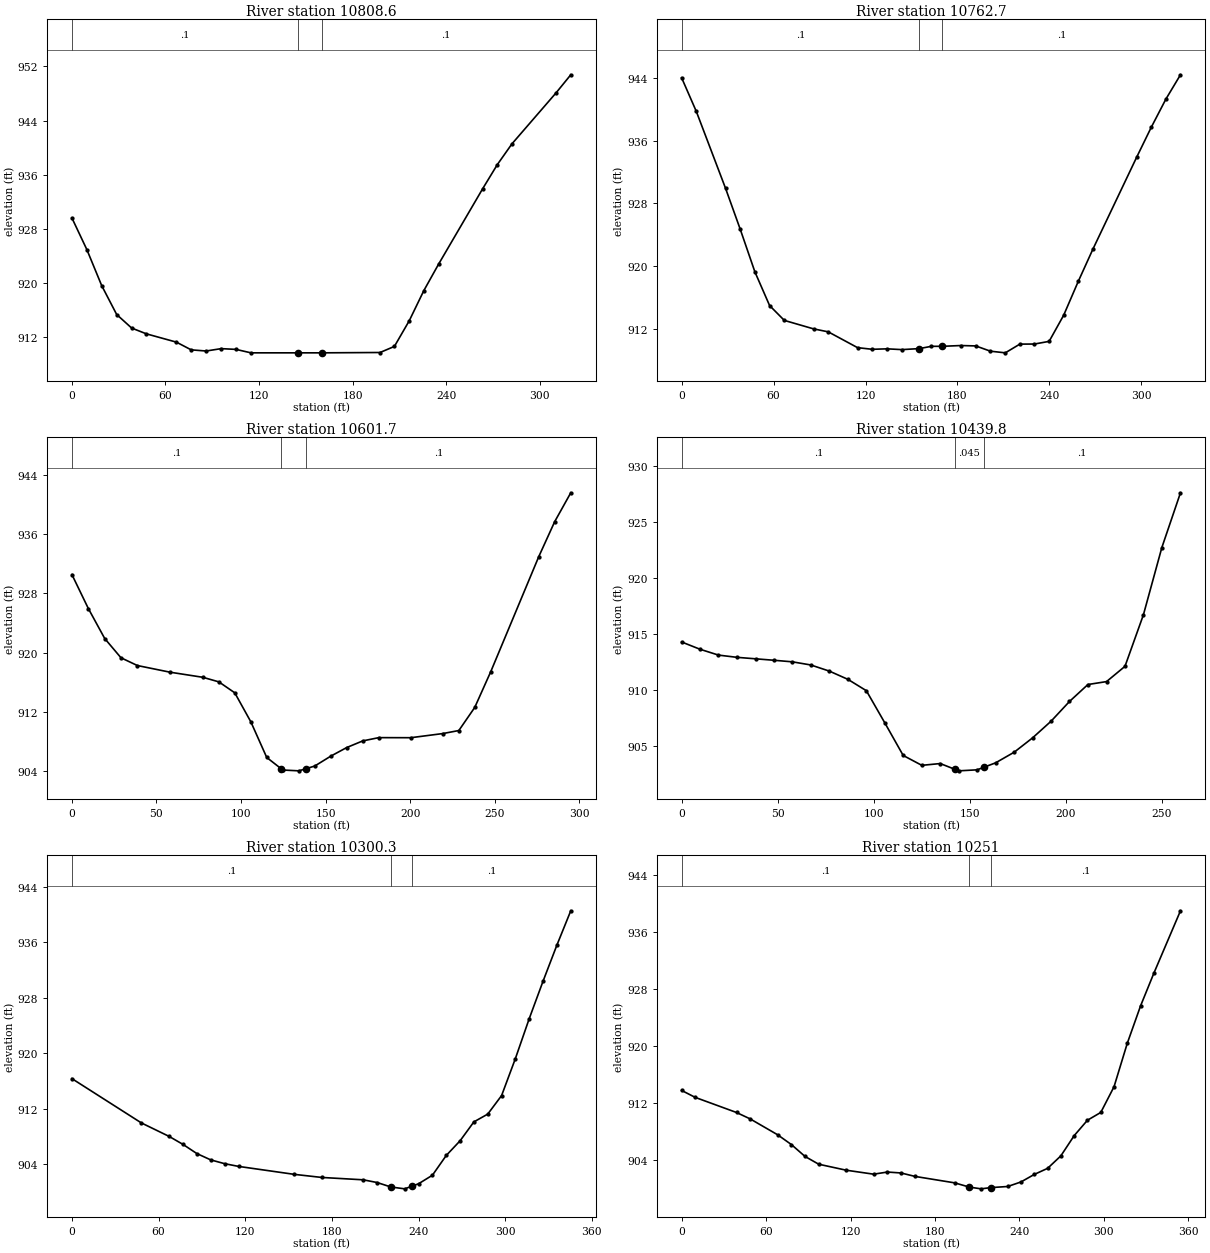
Type RM Length L Ch R = 1 ,10808.6 ,49.9,45.9,58.5
XS GIS Cut Line= 4
     1850802.318      475238.088     1850740.869      475335.042
     1850652.606      475308.868     1850598.888      475408.335
#Sta/Elev= 24
       0  929.61     9.6  924.93    19.1  919.62    28.7  915.36    38.3  913.36
    47.8   912.5      67  911.28    76.5  910.14    86.1  909.97    95.7  910.32
   105.2  910.21   114.8   909.7   145.2   909.7   160.2   909.7   197.6  909.75
   206.8  910.65   216.3  914.43   225.7   918.9   235.1  922.78   263.4  933.93
   272.8  937.49   282.2  940.56   310.5  948.09   319.9  950.75
#Mann= 3 , 0 , 0
       0      .1       0   145.2    .045       0   160.2      .1       0
Bank Sta=145.2,160.2
XS Rating Curve= 0 ,0
Exp/Cntr=0.3,0.1

Type RM Length L Ch R = 1 ,10762.7 ,197.8,161,109
XS GIS Cut Line= 4
     1850792.219      475199.855     1850730.769      475296.809
     1850638.372      475269.409     1850584.821      475370.462
#Sta/Elev= 30
       0     944     9.6  939.71    28.7  929.91    38.3  924.69    47.8   919.3
    57.4  915.01      67  913.12    86.1  912.04    95.7  911.66   114.8  909.65
   124.4  909.44   134.1   909.5   143.7   909.4   155.1  909.53     163  909.82
   170.1  909.82   182.2  909.92   191.9  909.87   201.5   909.2   211.2  908.99
   220.7   910.1   230.2  910.11   239.8  910.45   249.3  913.78   258.8  918.08
   268.3  922.16   296.9  933.88   306.5  937.72     316  941.29   325.5  944.38
#Mann= 3 , 0 , 0
       0      .1       0   155.1    .045       0   170.1      .1       0
Bank Sta=155.1,170.1
XS Rating Curve= 0 ,0
Exp/Cntr=0.3,0.1

Type RM Length L Ch R = 1 ,10601.7 ,163.9,161.9,160.8
XS GIS Cut Line= 3
     1850646.121      475071.408     1850590.634      475125.367
     1850504.905      475325.367
#Sta/Elev= 28
       0  930.54     9.7  925.95    19.4  921.89      29  919.29    38.7  918.24
      58  917.34    77.4  916.65    86.9  916.03    96.3  914.55   105.8  910.63
   115.2  905.81   123.6  904.31   124.7  904.11   134.2     904   138.6   904.3
   143.6  904.65   153.1  905.99   162.5  907.15     172  908.05   181.5  908.49
   200.4  908.48   219.3  909.04   228.8  909.45   238.2  912.57   247.7  917.42
   276.1  932.98   285.5   937.7     295   941.6
#Mann= 3 , 0 , 0
       0      .1       0   123.6    .045       0   138.6      .1       0
Bank Sta=123.6,138.6
XS Rating Curve= 0 ,0
Exp/Cntr=0.3,0.1

Type RM Length L Ch R = 1 ,10439.8 ,143.4,139.5,134.4
XS GIS Cut Line= 2
     1850458.655      475007.728     1850378.759      475254.881
#Sta/Elev= 30
       0  914.31     9.6  913.66    19.2  913.14    28.9  912.94    38.5  912.81
    48.1  912.68    57.7  912.54    67.3  912.26      77  911.71    86.6  910.98
    96.2  909.97   105.8  907.11   115.4   904.2   125.1  903.32   134.7  903.48
   142.4  902.96   144.3  902.83   153.9  902.92   157.4  903.15   163.5  903.54
   173.2  904.49   182.8  905.77   192.4  907.25     202  909.01   211.6  910.52
   221.3  910.78   230.9  912.14   240.5  916.73   250.1  922.72   259.8   927.6
#Mann= 3 , 0 , 0
       0      .1       0   142.4    .045       0   157.4      .1       0
Bank Sta=142.4,157.4
XS Rating Curve= 0 ,0
Exp/Cntr=0.3,0.1

Type RM Length L Ch R = 1 ,10300.3 ,47.4,49.3,50.9
XS GIS Cut Line= 3
     1850313.364      474931.582     1850282.114      475091.999
     1850259.891      475272.554
#Sta/Elev= 27
       0  916.34    48.1  909.96    67.3  908.02    76.9  906.87    86.5  905.55
    96.1  904.64   105.8  904.09   115.4   903.7   153.8  902.56     173  902.11
   201.7  901.77   211.3  901.38   220.8  900.74   230.4  900.47   235.8  900.88
     240   901.2   249.6  902.43   259.2  905.28   268.8   907.4   278.3  910.11
   287.9  911.23   297.5   913.9     307   919.2   316.6  924.96   326.2  930.37
   335.8  935.57   345.4  940.51
#Mann= 3 , 0 , 0
       0      .1       0   220.8    .045       0   235.8      .1       0
Bank Sta=220.8,235.8
XS Rating Curve= 0 ,0
Exp/Cntr=0.3,0.1

Type RM Length L Ch R = 1 ,10251   ,52.5,52,52.2
XS GIS Cut Line= 3
     1850178.077      474942.872     1850236.671       475097.82
     1850198.911      475282.716
#Sta/Elev= 30
       0  913.78     9.7   912.8      39  910.68    48.7  909.78    68.2  907.55
      78  906.17    87.7   904.5    97.4  903.41   116.9  902.57   136.4  902.01
   146.2  902.31   155.9  902.18   165.7   901.7     194  900.79   204.5  900.19
   212.8  899.95   219.5  900.12   231.7  900.28   241.1  900.92   250.6  901.98
     260  902.83   269.4  904.58   278.9  907.43   288.3  909.59   297.8  910.69
   307.2   914.3   316.6   920.4   326.1  925.69   335.5  930.26   354.4  939.03
#Mann= 3 , 0 , 0
       0      .1       0   204.5    .045       0   219.5      .1       0
Bank Sta=204.5,219.5
XS Rating Curve= 0 ,0
Exp/Cntr=0.3,0.1

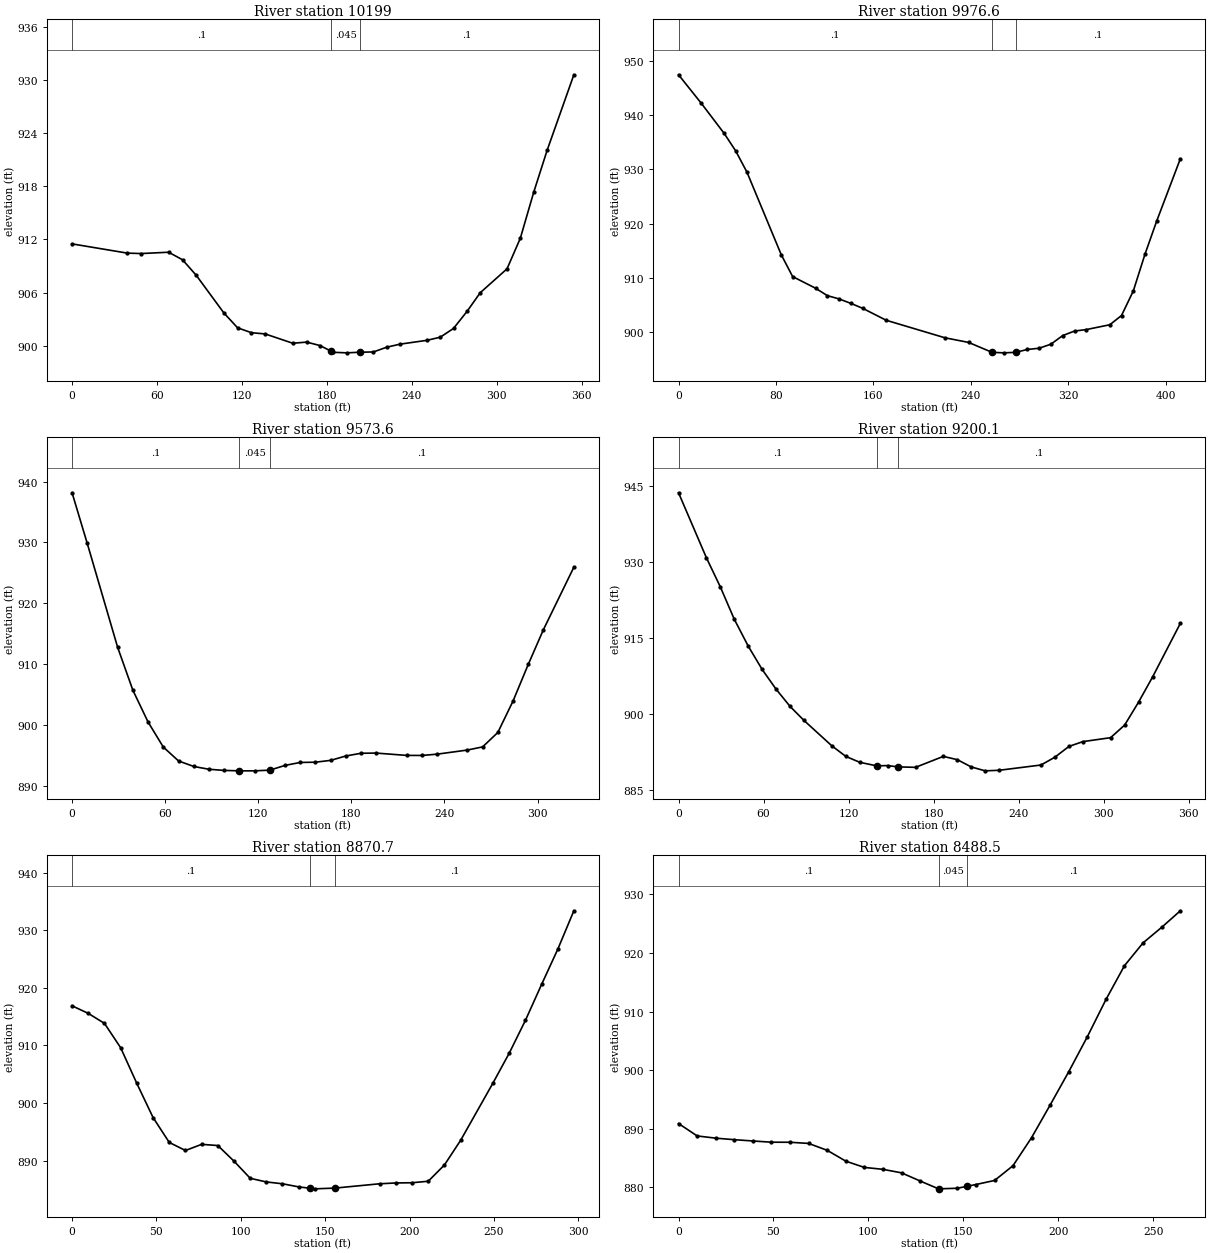
Type RM Length L Ch R = 1 ,10199   ,238.8,222.3,205.1
XS GIS Cut Line= 3
     1850125.357       474944.95      1850183.95      475099.898
      1850146.19      475284.794
#Sta/Elev= 30
       0   911.5      39  910.46    48.7  910.41    68.2  910.56      78  909.71
    87.7  907.96   107.2  903.72   116.9  902.04   126.7  901.49   136.4  901.35
   155.9   900.3   165.7  900.43   175.1  900.04   183.2  899.39   184.5  899.28
     194  899.22   203.4  899.29   212.8  899.32   222.3  899.86   231.7   900.2
   250.6  900.63     260  900.98   269.4  901.97   278.9  903.88   288.3     906
   307.2  908.69   316.6  912.14   326.1  917.35   335.5  922.04   354.4  930.56
#Mann= 3 , 0 , 0
       0      .1       0   183.2    .045       0   203.4      .1       0
Bank Sta=183.2,203.4
XS Rating Curve= 0 ,0
Exp/Cntr=0.3,0.1

Type RM Length L Ch R = 1 ,9976.6  ,410.5,403.1,395.6
XS GIS Cut Line= 3
     1849811.558      475002.138     1849906.002      475063.249
      1850058.78      475321.026
#Sta/Elev= 30
       0  947.39    18.8  942.11    37.5  936.59    46.9  933.39    56.2  929.46
    84.4  914.24    93.7  910.24   112.5   908.1   122.2  906.73   131.8  906.13
   141.5  905.31   151.2   904.4   170.5   902.2   218.8  898.97   238.2  898.12
   257.5  896.29   267.2   896.2   276.8  896.29   286.5  896.82   296.2  897.05
   305.8  897.79   315.5  899.38   325.2  900.21   334.8  900.48   354.2  901.37
   363.8  903.07   373.5   907.6   383.1  914.38   392.8  920.53   412.1  931.92
#Mann= 3 , 0 , 0
       0      .1       0   257.5    .045       0   276.8      .1       0
Bank Sta=257.5,276.8
XS Rating Curve= 0 ,0
Exp/Cntr=0.3,0.1

Type RM Length L Ch R = 1 ,9573.6  ,378,373.5,369.3
XS GIS Cut Line= 2
     1849560.877      475312.797     1849805.322      475524.603
#Sta/Elev= 30
       0  938.16     9.8  929.82    29.4  912.72    39.2  905.68      49  900.45
    58.8  896.34    68.6  894.06    78.4  893.15    88.2  892.69      98   892.5
   107.8  892.43   117.6  892.43   127.4  892.54   137.2  893.32     147  893.81
   156.8  893.85   166.6  894.15   176.4  894.87   186.2  895.32     196  895.35
   215.6  894.97   225.4  894.96   235.2  895.17   254.8  895.85   264.6  896.37
   274.4  898.74   284.2  903.91     294  909.93   303.8  915.66   323.4  925.92
#Mann= 3 , 0 , 0
       0      .1       0   107.8    .045       0   127.4      .1       0
Bank Sta=107.8,127.4
XS Rating Curve= 0 ,0
Exp/Cntr=0.3,0.1

Type RM Length L Ch R = 1 ,9200.1  ,323.7,329.3,334.6
XS GIS Cut Line= 2
     1849315.044      475625.818     1849621.989      475802.207
#Sta/Elev= 30
       0  943.62    19.7  930.78    29.5  925.05    39.3  918.69    49.2  913.36
      59  908.77    68.8  904.89    78.7  901.48    88.5  898.72   108.2   893.7
     118  891.63   127.8  890.47   139.8  889.76   147.5  889.82   154.8  889.56
   167.2  889.47   186.8  891.63   196.7  890.98   206.5  889.55   216.3  888.78
   226.2  888.89   255.7  889.93   265.5  891.47   275.4  893.59   285.2  894.54
   304.8  895.32   314.7   897.8   324.5  902.31   334.4  907.28     354  917.86
#Mann= 3 , 0 , 0
       0      .1       0   139.8    .045       0   154.8      .1       0
Bank Sta=139.8,154.8
XS Rating Curve= 0 ,0
Exp/Cntr=0.3,0.1

Type RM Length L Ch R = 1 ,8870.7  ,364.5,382.3,398.4
XS GIS Cut Line= 2
     1849207.166      475887.266     1849422.166      476092.822
#Sta/Elev= 30
       0  916.87     9.6  915.56    19.2  913.82    28.8  909.59    38.4  903.38
      48  897.47    57.6  893.14    67.2  891.74    76.8  892.81    86.4   892.6
      96  889.88   105.6  886.91   115.1  886.28   124.7  885.96   134.3  885.42
   140.8  885.19   143.9  885.08   155.8  885.21   182.3  885.96   191.9   886.1
   201.5  886.14   211.1   886.4   220.7  889.23   230.3  893.51   249.5  903.48
   259.1  908.65   268.7  914.35   278.3   920.6   287.9  926.72   297.4  933.38
#Mann= 3 , 0 , 0
       0      .1       0   140.8    .045       0   155.8      .1       0
Bank Sta=140.8,155.8
XS Rating Curve= 0 ,0
Exp/Cntr=0.3,0.1

Type RM Length L Ch R = 1 ,8488.5  ,225.9,229,232
XS GIS Cut Line= 2
     1849023.398      475977.172     1849036.176      476241.061
#Sta/Elev= 29
       0   890.9     9.8  888.78    19.6   888.4    29.4  888.14    39.1  887.92
    48.9  887.71    58.7   887.7    68.5   887.5    78.3  886.32    88.1  884.47
    97.8  883.41   107.6  883.08   117.4  882.48   127.2  881.09   136.9  879.75
   146.8  879.85   151.9  880.18   156.6  880.49   166.4  881.18   176.1   883.7
   185.9   888.5   195.7  894.08   205.5  899.77   215.3  905.75   225.1   912.1
   234.8  917.84   244.6  921.74   254.4  924.39   264.2  927.21
#Mann= 3 , 0 , 0
       0      .1       0   136.9    .045       0   151.9      .1       0
Bank Sta=136.9,151.9
XS Rating Curve= 0 ,0
Exp/Cntr=0.3,0.1

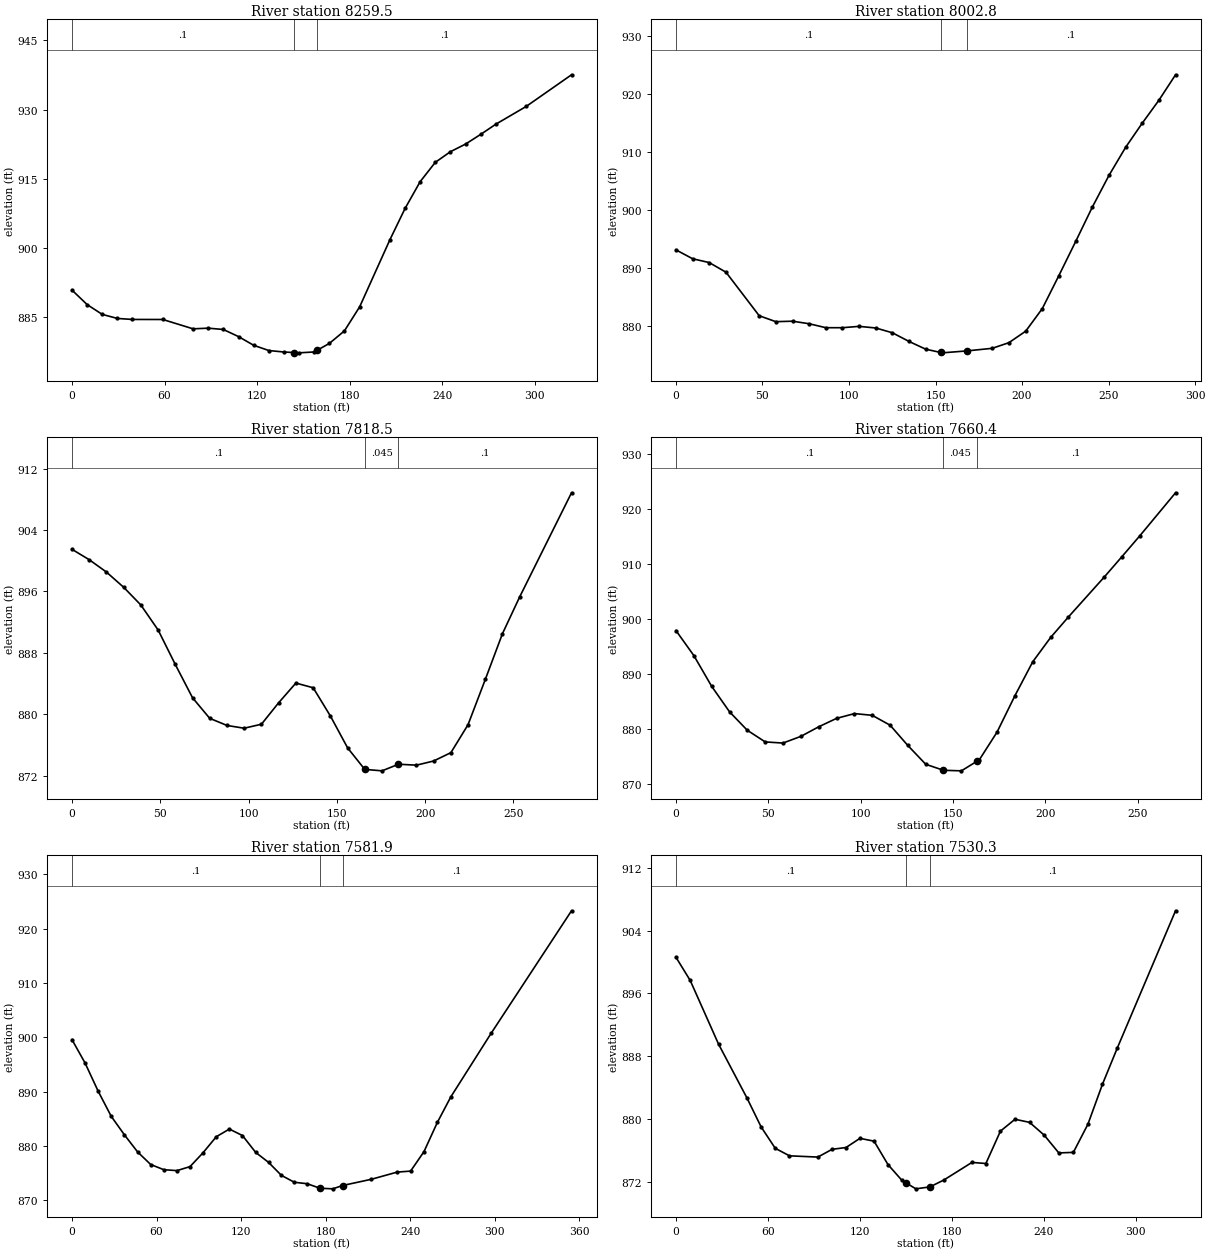
Type RM Length L Ch R = 1 ,8259.5  ,251.8,256.7,261.3
XS GIS Cut Line= 2
     1848814.492      475993.065      1848792.27      476316.155
#Sta/Elev= 30
       0  890.91     9.8  887.78    19.6  885.65    29.4  884.77    39.2  884.55
    58.9  884.54    78.5  882.52    88.3  882.66    98.1  882.38     108  880.83
   117.8  878.95   127.6  877.82   137.4   877.5     144  877.38   147.2  877.32
     157  877.51     159  877.89   166.8  879.35   176.6  882.07   186.5   887.3
   206.1  901.82   215.9  908.58   225.7  914.39   235.5  918.57   245.3  920.87
   255.2  922.54     265  924.64   274.8  926.84   294.4  930.67   323.8  937.53
#Mann= 3 , 0 , 0
       0      .1       0     144    .045       0     159      .1       0
Bank Sta=144,159
XS Rating Curve= 0 ,0
Exp/Cntr=0.3,0.1

Type RM Length L Ch R = 1 ,8002.8  ,180.9,184.3,187.5
XS GIS Cut Line= 2
     1848597.478      475959.211     1848515.881       476236.12
#Sta/Elev= 30
       0  893.17     9.6  891.64    19.2  890.98    28.9  889.32    48.1  881.82
    57.7   880.8    67.4  880.88      77  880.44    86.6  879.76    96.2  879.76
   105.8  879.99   115.5  879.71   125.1  878.88   134.7  877.39   144.3  876.06
     153  875.49     154  875.43     168  875.76   182.8  876.21   192.4  877.18
   202.1  879.16   211.7  883.05   221.3  888.75     231  894.62   240.6  900.53
   250.2  905.98   259.8  910.81   269.4  914.97   279.1  918.95   288.7  923.33
#Mann= 3 , 0 , 0
       0      .1       0     153    .045       0     168      .1       0
Bank Sta=153,168
XS Rating Curve= 0 ,0
Exp/Cntr=0.3,0.1

Type RM Length L Ch R = 1 ,7818.5  ,154.6,158.1,161.1
XS GIS Cut Line= 2
     1848453.575      475893.961     1848334.687      476150.627
#Sta/Elev= 28
       0  901.48     9.8  900.12    19.5  898.52    29.3  896.53      39  894.23
    48.8  890.97    58.5  886.49    68.3  882.14      78  879.47    87.8  878.54
    97.5  878.18   107.3   878.7     117  881.48   126.8  884.06   136.6  883.45
   146.3  879.79   156.1  875.62   165.8  872.82   175.6  872.63   184.9  873.49
   195.1  873.37   204.8  873.91   214.6     875   224.3  878.64   234.1  884.55
   243.8   890.5   253.6  895.31   282.9  908.84
#Mann= 3 , 0 , 0
       0      .1       0   165.8    .045       0   184.9      .1       0
Bank Sta=165.8,184.9
XS Rating Curve= 0 ,0
Exp/Cntr=0.3,0.1

Type RM Length L Ch R = 1 ,7660.4  ,40.8,78.6,107.3
XS GIS Cut Line= 2
     1848321.376       475858.15     1848173.806      476084.713
#Sta/Elev= 28
       0  897.87     9.7  893.31    19.3  887.74      29  883.09    38.6  879.74
    48.3  877.62    57.9  877.41    67.6  878.63    77.2  880.36    86.9   881.9
    96.6  882.77   106.2  882.46   115.9  880.66   125.5  876.97   135.2  873.55
   144.8  872.46   154.5  872.36   162.9   874.1   164.2  874.37   173.8  879.41
   183.5  886.05   193.1  892.19   202.8  896.62   212.4  900.34   231.8   907.6
   241.4  911.32   251.1  915.12   270.4  922.93
#Mann= 3 , 0 , 0
       0      .1       0   144.8    .045       0   162.9      .1       0
Bank Sta=144.8,162.9
XS Rating Curve= 0 ,0
Exp/Cntr=0.3,0.1

Type RM Length L Ch R = 1 ,7581.9  ,59.9,51.6,58.7
XS GIS Cut Line= 4
     1848308.397      475845.121     1848231.018      475950.034
     1848133.226      475927.247     1848084.093      476040.841
#Sta/Elev= 30
       0  899.57     9.3  895.27    18.6  890.08    27.9  885.45    37.2  882.07
    46.6  878.91    55.9   876.6    65.2  875.65    74.5  875.48    83.8  876.22
    93.1  878.79   102.4  881.71   111.7  883.12     121  881.93   130.4  878.82
   139.5     877   148.6  874.61   157.8  873.34   166.9  873.07     176  872.24
   185.1  872.13     192  872.74   212.5  873.89   230.8  875.21   240.3  875.39
   249.8  878.97   259.3  884.35   268.8  889.02   297.4  900.71   354.5  923.26
#Mann= 3 , 0 , 0
       0      .1       0     176    .045       0     192      .1       0
Bank Sta=176,192
XS Rating Curve= 0 ,0
Exp/Cntr=0.3,0.1

Type RM Length L Ch R = 1 ,7530.3  ,111.2,81.2,43.8
XS GIS Cut Line= 4
      1848285.61      475818.062     1848225.321      475900.188
     1848127.529      475877.402     1848078.396      475990.995
#Sta/Elev= 30
       0   900.6     9.3  897.64    27.8  889.52    46.3  882.67    55.6  878.96
    64.8  876.24    74.1  875.28    92.6  875.12   101.9  876.11     111  876.34
   120.1  877.51   129.3  877.15   138.4  874.16   147.5  872.15     150  871.85
   156.6  871.07   165.8  871.32   174.9   872.2   193.2  874.44   202.3   874.3
   211.8  878.43   221.3  879.94   230.8  879.55   240.4  877.91   249.9  875.65
   259.4  875.72   268.9  879.31   278.4  884.41     288  888.99   326.1  906.53
#Mann= 3 , 0 , 0
       0      .1       0     150    .045       0   165.8      .1       0
Bank Sta=150,165.8
XS Rating Curve= 0 ,0
Exp/Cntr=0.3,0.1

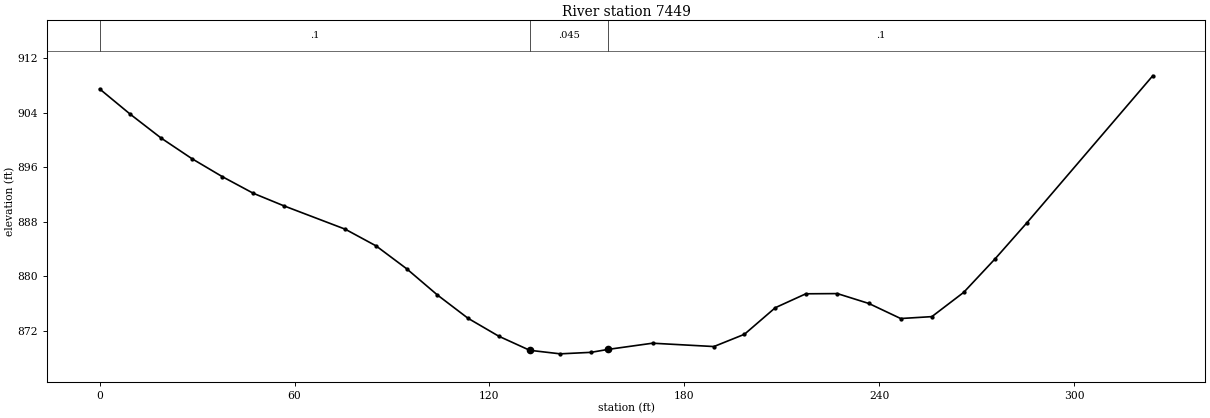
Type RM Length L Ch R = 1 ,7449    ,346.1,335.2,323.4
XS GIS Cut Line= 3
     1848194.085        475696.6     1848084.687      475884.516
     1848060.242      475988.405
#Sta/Elev= 30
       0  907.46     9.4  903.76    18.9  900.26    28.4  897.23    37.8  894.58
    47.3  892.15    56.7  890.31    75.6  886.88    85.1  884.43    94.5  881.08
     104  877.22   113.4  873.81   122.9  871.17   132.4  869.11   141.8  868.59
   151.3  868.81   156.5  869.24   170.2  870.15   189.1  869.66   198.5  871.46
     208  875.36   217.4   877.4   227.1  877.43   236.8  875.98   246.6  873.77
   256.2  874.05     266  877.61   275.7  882.55   285.4  887.79   324.2  909.39
#Mann= 3 , 0 , 0
       0      .1       0   132.4    .045       0   156.5      .1       0
Bank Sta=132.4,156.5
XS Rating Curve= 0 ,0
Exp/Cntr=0.3,0.1