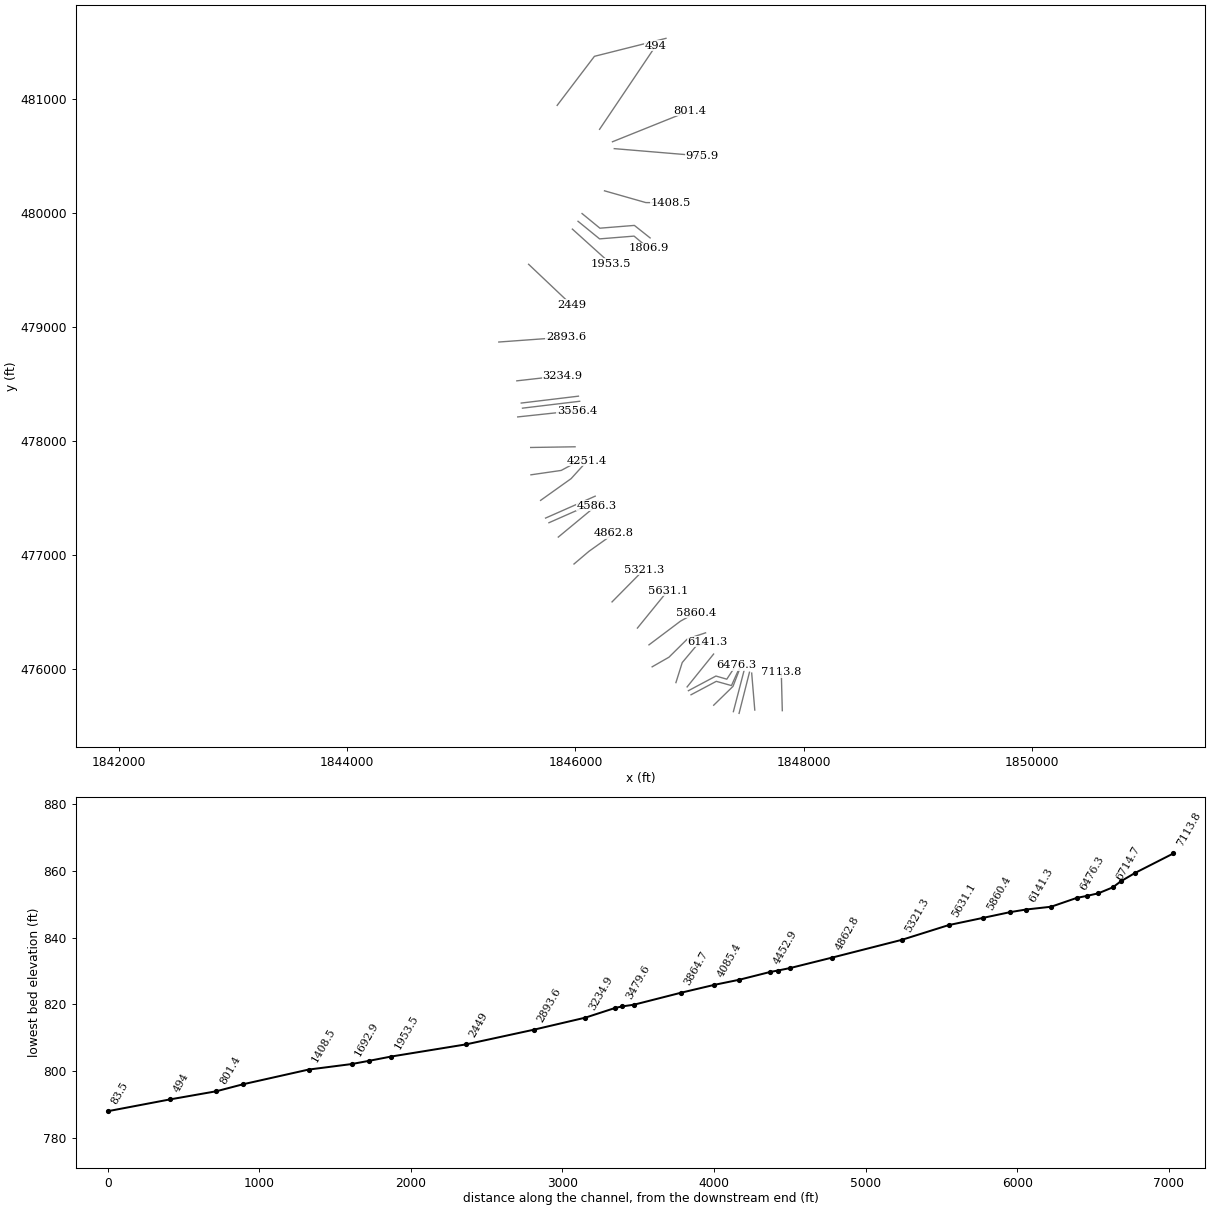
HEC-RAS study CAMPBLSCK.prj: CAMPBLSCK

--- CAMPBLSCK.g02 (geometry) --- (continued)

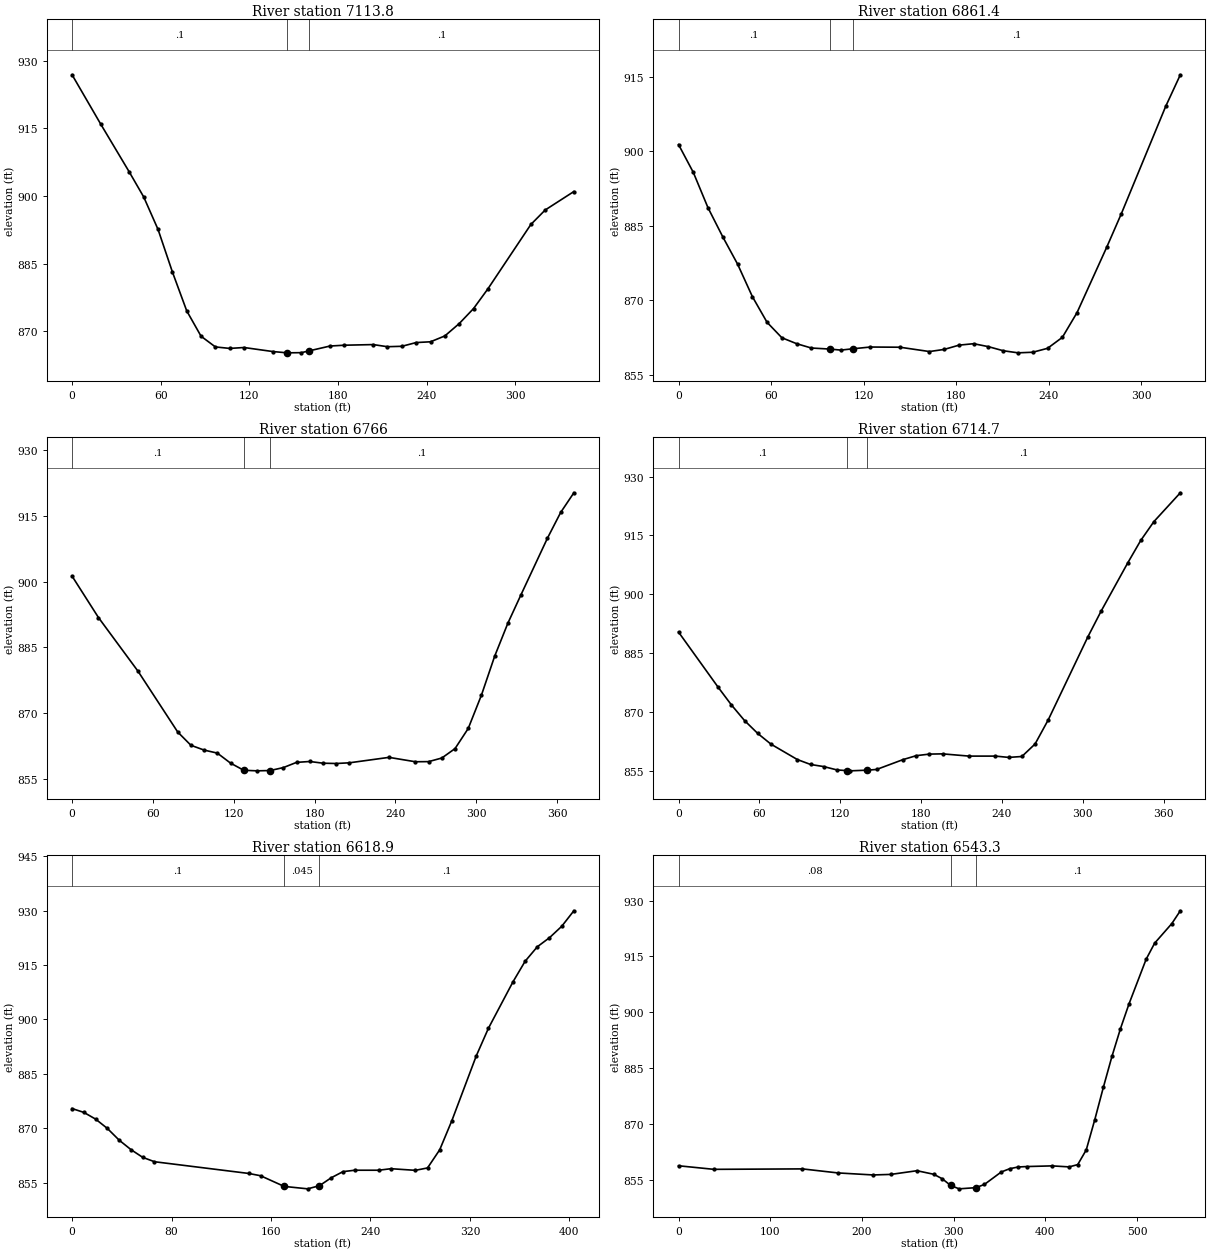
Type RM Length L Ch R = 1 ,7113.8  ,251.1,252.4,253.4
XS GIS Cut Line= 2
     1847812.835      475634.239     1847804.005      475973.705
#Sta/Elev= 30
       0   926.9    19.4  915.96    38.8  905.31    48.5  899.81    58.2  892.61
    67.9   883.2    77.6  874.57    87.3  868.95      97  866.58   106.7  866.25
   116.4  866.45   135.8  865.56   145.2  865.28   145.5  865.27   155.2  865.31
   160.2  865.69   174.6  866.78   184.3  866.96   203.8   867.1   213.4  866.63
   223.2  866.72   232.9  867.55   242.6  867.72   252.3  869.02     262  871.75
   271.7  875.08   281.4  879.44   310.5  893.72   320.2  896.93   339.6  901.02
#Mann= 3 , 0 , 0
       0      .1       0   145.2    .045       0   160.2      .1       0
Bank Sta=145.2,160.2
XS Rating Curve= 0 ,0
Exp/Cntr=0.3,0.1

Type RM Length L Ch R = 1 ,6861.4  ,102.9,95.4,87.8
XS GIS Cut Line= 2
     1847571.793      475639.655      1847544.71      475963.961
#Sta/Elev= 30
       0  901.37     9.6  895.75    19.1  888.65    28.7  882.78    38.3  877.29
    47.9  870.74    57.4  865.58      67  862.47    76.6  861.27    86.1   860.4
    98.1  860.19   105.3  859.98   113.1  860.25   124.4   860.6   143.6  860.56
   162.7  859.69   172.3  860.12   181.9  860.98   191.4  861.27     201  860.67
   210.6  859.85   220.2  859.43   229.7  859.55   239.3  860.34   248.9  862.55
   258.4  867.52   277.6  880.65   287.2  887.48   315.9  909.05   325.4  915.42
#Mann= 3 , 0 , 0
       0      .1       0    98.1    .045       0   113.1      .1       0
Bank Sta=98.1,113.1
XS Rating Curve= 0 ,0
Exp/Cntr=0.3,0.1

Type RM Length L Ch R = 1 ,6766    ,51.5,51.4,51.4
XS GIS Cut Line= 2
     1847434.148      475610.474     1847525.222      475971.552
#Sta/Elev= 30
       0  901.24    19.6   891.8      49  879.55    78.4  865.73    88.2   862.7
      98  861.61   107.8  860.92   117.6  858.64   127.4  857.01   137.2  856.88
     147  856.95   156.8  857.62   166.6  858.81   176.4  859.01   186.2  858.62
     196  858.55   205.8  858.71   235.2  859.95   254.8  858.95   264.6  858.98
   274.4   859.8   284.2  861.94     294  866.53   303.8  874.12   313.6  882.97
   323.4   890.5   333.2  897.02   352.8  909.89   362.6  915.74   372.4  920.23
#Mann= 3 , 0 , 0
       0      .1       0   127.4    .045       0     147      .1       0
Bank Sta=127.4,147
XS Rating Curve= 0 ,0
Exp/Cntr=0.3,0.1

Type RM Length L Ch R = 1 ,6714.7  ,108.2,95.8,83.7
XS GIS Cut Line= 2
      1847384.19      475625.604      1847477.86      475986.017
#Sta/Elev= 30
       0  890.42    29.4  876.38    39.2   871.9      49   867.9    58.8  864.62
    68.6   861.9    88.2  857.98      98  856.73   107.8  856.19   117.6  855.34
   125.1  855.16   127.4  855.11   140.1  855.28     147  855.46   166.6  857.97
   176.4  858.97   186.2  859.37     196  859.43   215.6  858.86   235.2  858.86
     245  858.53   254.8  858.76   264.6  861.94   274.4   868.1   303.8  889.22
   313.6  895.74   333.2  907.92     343  913.73   352.8  918.54   372.4  925.87
#Mann= 3 , 0 , 0
       0      .1       0   125.1    .045       0   140.1      .1       0
Bank Sta=125.1,140.1
XS Rating Curve= 0 ,0
Exp/Cntr=0.3,0.1

Type RM Length L Ch R = 1 ,6618.9  ,105.7,75.6,44.2
XS GIS Cut Line= 3
     1847211.765      475682.101     1847381.116       475847.73
     1847440.668      476003.433
#Sta/Elev= 30
       0  875.43     9.5  874.37      19  872.51    28.4  869.95    37.9  866.72
    47.4  864.11    56.8  861.99    66.3  860.78   142.1  857.55   151.6  856.92
   170.6  853.98   189.5  853.31     199  854.18   208.5  856.37   217.9  858.05
   227.4  858.44   246.7  858.44   256.5  858.86   276.1  858.41   285.9  859.07
   295.7  864.07   305.5  872.12   325.1  889.94   334.9  897.57   354.6  910.33
   364.4  916.02   374.2  920.01     384  922.51   393.8  925.64   403.6  929.93
#Mann= 3 , 0 , 0
       0      .1       0   170.6    .045       0     199      .1       0
Bank Sta=170.6,199
XS Rating Curve= 0 ,0
Exp/Cntr=0.3,0.1

Type RM Length L Ch R = 1 ,6543.3  ,69.8,67,67.3
XS GIS Cut Line= 4
     1847013.231      475773.863      1847234.69      475891.726
     1847367.441      475854.506     1847432.576      475999.044
#Sta/Elev= 30
       0  858.73    38.6  857.77   135.1  857.89   173.7  856.81   212.3  856.26
   231.6  856.41   260.1   857.4   278.4  856.44   287.6  855.24   296.8  853.44
     306  852.53   324.4  852.85   333.6  853.71     352  857.06   361.2  857.94
   370.4   858.4   379.6  858.52   407.4   858.7     426  858.43   435.4  859.04
   444.7     863     454  871.12   463.3  879.77   472.7  888.11     482  895.57
   491.3  902.22     510  914.23   519.3  918.56     538  923.81   547.3  927.26
#Mann= 3 , 0 , 0
       0     .08       0   296.8    .045       0   324.4      .1       0
Bank Sta=296.8,324.4
XS Rating Curve= 0 ,0
Exp/Cntr=0.3,0.1

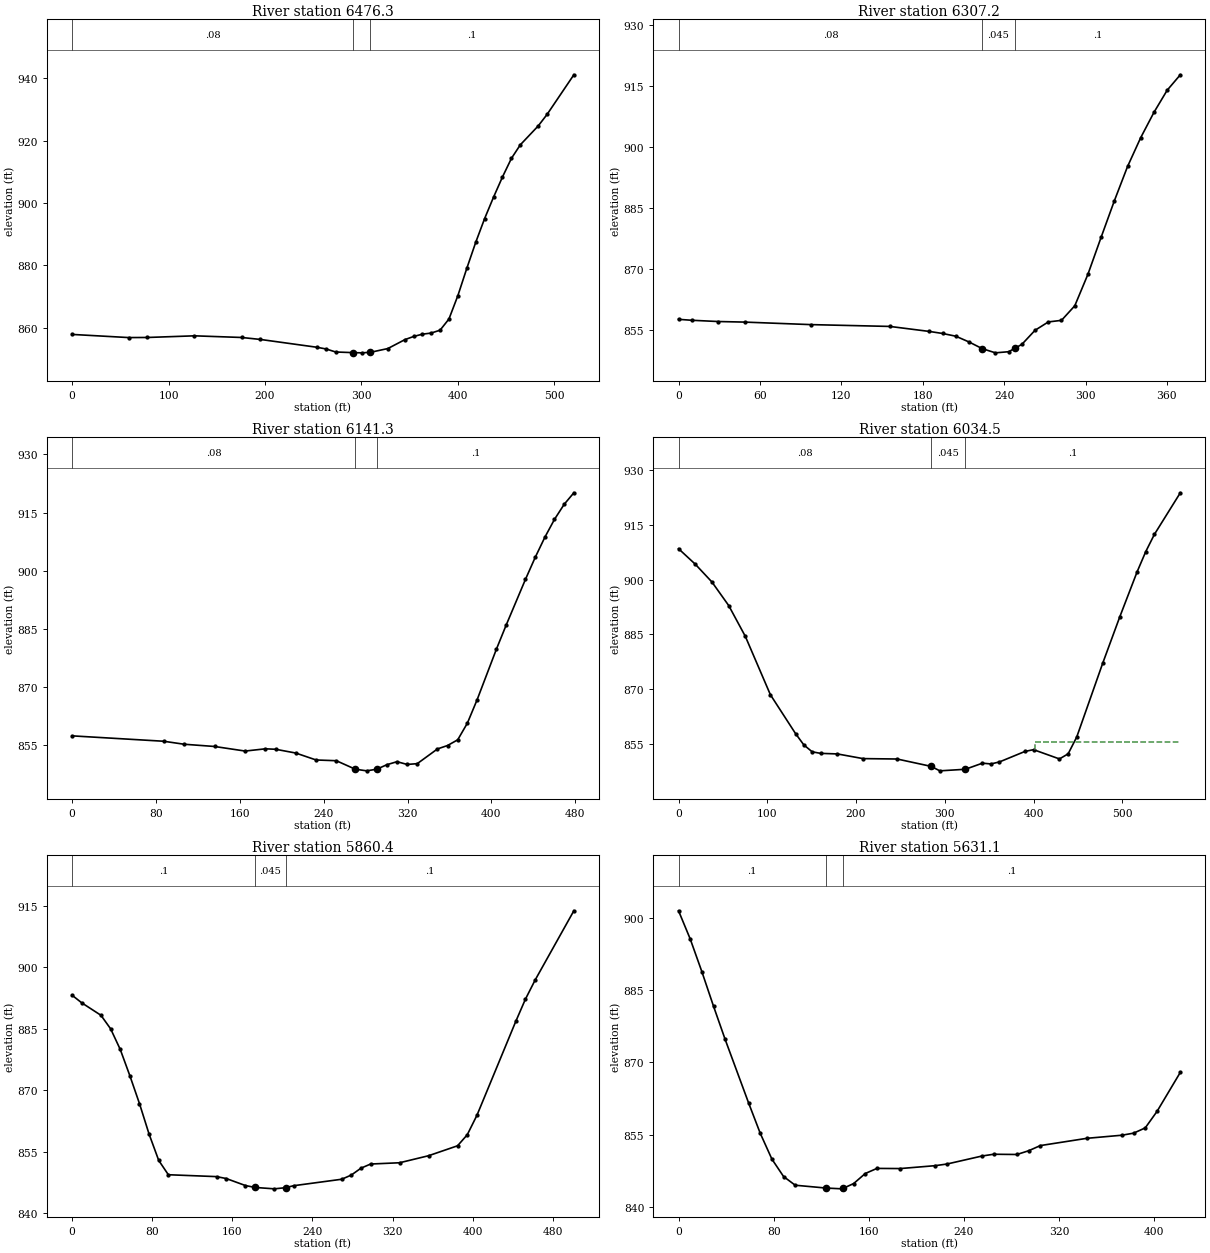
Type RM Length L Ch R = 1 ,6476.3  ,132.9,169.1,202.4
XS GIS Cut Line= 4
      1846990.43       475809.65     1847231.588      475938.251
     1847326.587      475910.649     1847407.763      476034.403
#Sta/Elev= 30
       0  857.84    58.6  856.83    78.1  856.86   126.9  857.39   175.7  856.86
   195.2  856.23   253.8  853.72   263.5  853.16   273.3   852.2   291.3     852
   300.3  851.93   309.3   852.1   327.3   853.3   345.2  856.19   354.2  857.19
   363.2  857.92   372.2  858.27   381.5   859.2   390.7  862.78     400  870.32
   409.2  879.03   418.5  887.42   427.7  895.02     437  901.93   446.2  908.36
   455.5  914.34   464.7  918.68   483.2  924.72   492.5  928.46   520.2  941.15
#Mann= 3 , 0 , 0
       0     .08       0   291.3    .045       0   309.3      .1       0
Bank Sta=291.3,309.3
XS Rating Curve= 0 ,0
Exp/Cntr=0.3,0.1

Type RM Length L Ch R = 1 ,6307.2  ,166.2,165.9,165.4
XS GIS Cut Line= 2
     1846979.055      475842.995     1847210.999       476131.19
#Sta/Elev= 27
       0  857.54     9.7  857.31    29.2     857    48.7  856.86    97.4  856.24
   155.8  855.79     185  854.55   194.7  854.05   204.4  853.38   214.2  851.95
   223.9  850.31   233.6  849.28   243.4  849.56   247.8  850.38   253.1  851.37
   262.8  854.84   272.6   856.9   282.3  857.29   292.1  860.88   301.8  868.66
   311.5  877.76   321.3  886.79     331  895.22   340.7  902.33   350.5  908.59
   360.2  914.02   369.9  917.83
#Mann= 3 , 0 , 0
       0     .08       0   223.9    .045       0   247.8      .1       0
Bank Sta=223.9,247.8
XS Rating Curve= 0 ,0
Exp/Cntr=0.3,0.1

Type RM Length L Ch R = 1 ,6141.3  ,108.9,106.8,104.7
XS GIS Cut Line= 4
     1846880.994      475880.627     1846936.203      476056.669
     1847053.911      476197.294     1847157.036      476237.919
#Sta/Elev= 30
       0  857.46    87.4  856.07   106.8   855.3   135.9  854.72   165.1  853.54
   184.5  854.12   194.2     854   213.4  853.03   232.8  851.24   252.1  851.05
   270.1  848.87     281  848.44   290.7  848.86   300.3  850.02     310   850.8
   319.6  850.09   329.3  850.29   348.6  854.09   358.2  854.97   367.9  856.44
   377.1  860.73   386.4  866.76   404.8   879.8   414.1     886   432.5  897.79
   441.8  903.46     451  908.65   460.2  913.27   469.5  917.17   478.7  920.13
#Mann= 3 , 0 , 0
       0     .08       0   270.1    .045       0   290.7      .1       0
Bank Sta=270.1,290.7
XS Rating Curve= 0 ,0
Exp/Cntr=0.3,0.1

Type RM Length L Ch R = 1 ,6034.5  ,177.1,174.1,171
XS GIS Cut Line= 4
     1846672.661      476019.169     1846819.641      476103.448
     1846983.464      476265.773     1847140.522      476317.558
#Sta/Elev= 30
       0  908.49    18.8  904.26    37.6  899.38    56.5  892.93    75.3  884.46
   103.5  868.49   131.8  857.86   141.2  854.74   150.6  852.85     160  852.43
     179  852.27   207.9  850.99   246.3  850.88   284.7  848.86   294.4  847.64
   323.2  848.07   342.4  849.74     352  849.53   361.6  850.08   390.4  852.96
     400  853.44   429.2   850.9     439   852.3   448.7  856.92   477.9  877.09
   497.3   889.9   516.8  902.21   526.5  907.72   536.2  912.42   565.4  923.81
#Mann= 3 , 0 , 0
       0     .08       0   284.7    .045       0   323.2      .1       0
#XS Ineff= 2 , 0
                           401.1          855.47
Permanent Ineff=
       F       F
Bank Sta=284.7,323.2
XS Rating Curve= 0 ,0
Exp/Cntr=0.3,0.1

Type RM Length L Ch R = 1 ,5860.4  ,223.3,229.2,234.5
XS GIS Cut Line= 3
     1846644.855      476212.042     1846921.244      476420.375
     1847056.661      476495.375
#Sta/Elev= 30
       0  893.18     9.6  891.33    28.8  888.29    38.5  884.98    48.1  879.95
    57.7  873.54    67.3  866.74    76.9  859.29    86.5  852.89    96.1   849.4
   144.2  848.94   153.8  848.48   173.1  846.76   182.7   846.3   201.9  845.96
   213.1  846.24   221.1  846.72   269.2   848.3   278.8  849.33   288.4     851
     298  852.01   326.9  852.32   355.8  854.03   384.8  856.46   394.5  859.15
   404.2  863.92   442.9  886.78   452.5  892.19   462.2  896.86   500.9  913.77
#Mann= 3 , 0 , 0
       0      .1       0   182.7    .045       0   213.1      .1       0
Bank Sta=182.7,213.1
XS Rating Curve= 0 ,0
Exp/Cntr=0.3,0.1

Type RM Length L Ch R = 1 ,5631.1  ,312,309.8,307.6
XS GIS Cut Line= 2
     1846543.644      476359.408     1846809.439      476687.042
#Sta/Elev= 30
       0  901.49     9.8  895.65    19.6  888.86    29.4  881.69    39.2  874.78
    58.9  861.61    68.7   855.3    78.5  849.94    88.3  846.33    98.1  844.52
   123.7  843.94   137.4  843.77   138.7  843.91   147.2  844.86     157  846.95
   166.8  848.01   186.4  847.98   215.8  848.58   225.7  848.92   255.1  850.58
   264.9  850.95   284.5   850.9   294.3  851.67   304.2  852.75   343.4  854.26
   372.8   854.9   382.6  855.33   392.4  856.42   402.3  859.84   421.9  867.95
#Mann= 3 , 0 , 0
       0      .1       0   123.7    .045       0   138.7      .1       0
Bank Sta=123.7,138.7
XS Rating Curve= 0 ,0
Exp/Cntr=0.3,0.1

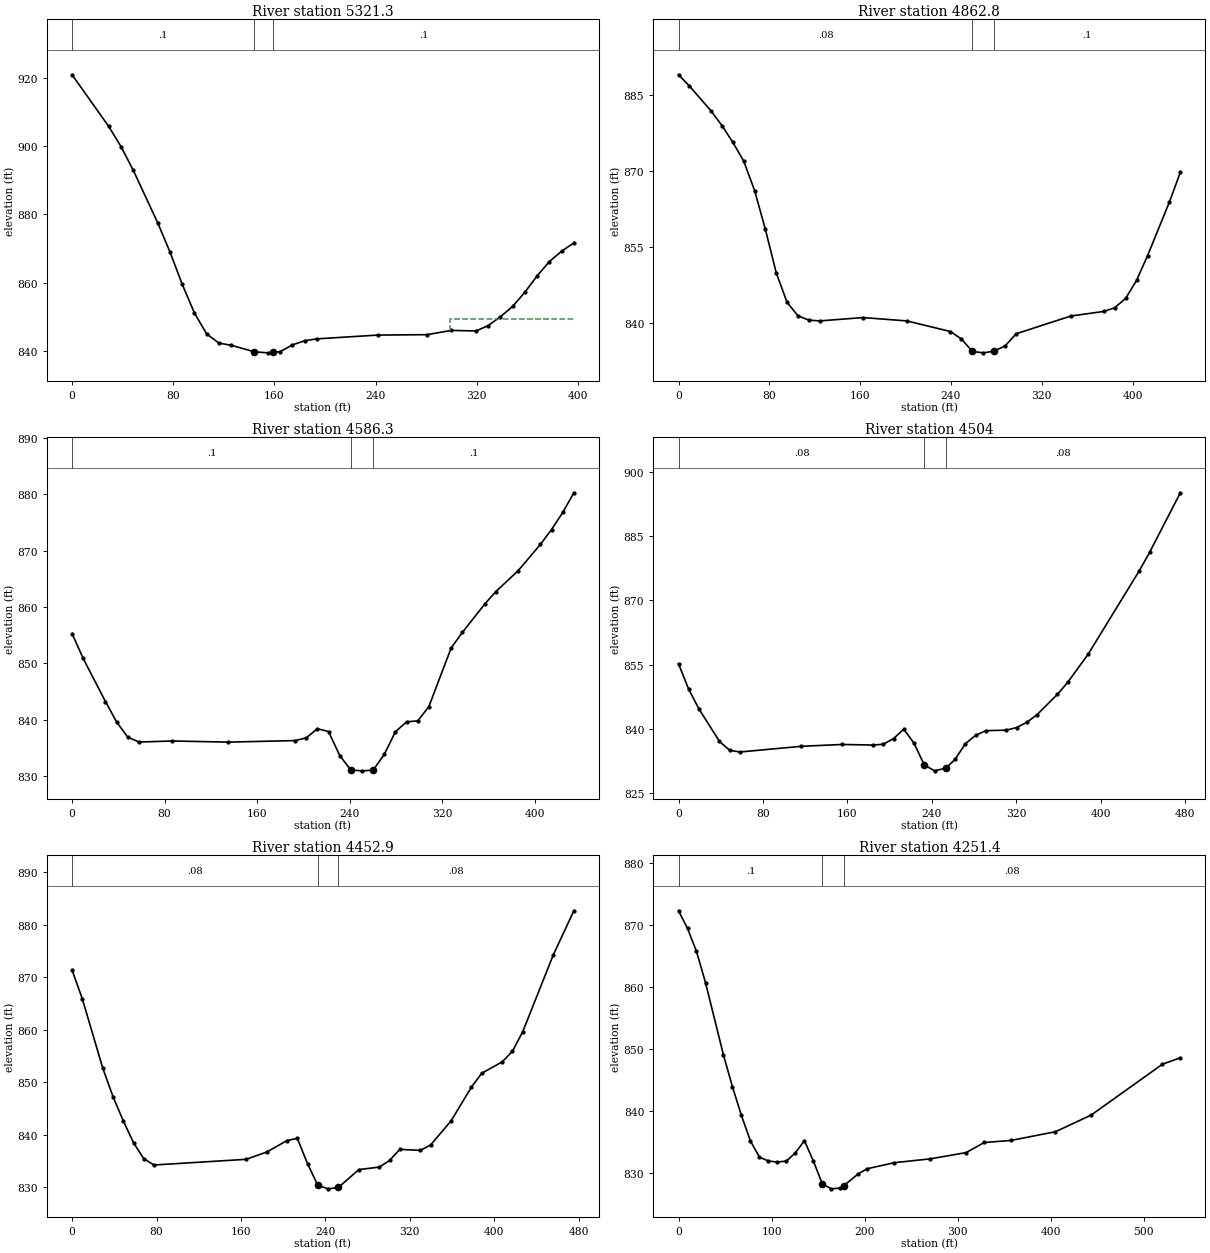
Type RM Length L Ch R = 1 ,5321.3  ,462.5,458.6,454.6
XS GIS Cut Line= 2
     1846321.244      476589.125     1846599.717      476871.764
#Sta/Elev= 30
       0  921.03      29  905.85    38.7  899.95    48.4  892.98    67.7  877.56
    77.4     869    87.1  859.47    96.8  851.01   106.4  844.92   116.1   842.2
   125.8  841.57   144.1  839.65   154.8  839.34   159.1  839.49   164.5  839.68
   174.2  841.66   183.9   842.9   193.6  843.45   241.9  844.56   280.6  844.68
     300  845.93   319.4  845.77     329  847.33   338.7  849.94   348.4  852.98
   358.1  857.17   367.7  861.92   377.4  866.15   387.1  869.19   396.8  871.64
#Mann= 3 , 0 , 0
       0      .1       0   144.1    .045       0   159.1      .1       0
#XS Ineff= 2 , 0
                          298.53          849.34
Permanent Ineff=
       F       F
Bank Sta=144.1,159.1
XS Rating Curve= 0 ,0
Exp/Cntr=0.3,0.1

Type RM Length L Ch R = 1 ,4862.8  ,274.8,276.4,278
XS GIS Cut Line= 3
     1845987.955      476921.814     1846119.152      477033.279
     1846338.881      477190.075
#Sta/Elev= 30
       0  888.98     9.6  886.76    28.7  881.83    38.3  878.92    47.8  875.65
    57.4  871.93      67  866.11    76.5  858.44    86.1  849.83    95.6  844.02
   105.2  841.36   114.8   840.5   124.3  840.34   162.6     841   201.1  840.34
   239.6  838.24   249.3  836.75   258.9   834.3   268.6  834.03   278.2  834.37
   287.8  835.42   297.5   837.8   345.7  841.31   374.6  842.21   384.2  842.93
   393.9  844.78   403.5  848.33   413.2  853.21   432.4  863.79   442.1   869.7
#Mann= 3 , 0 , 0
       0     .08       0   258.9    .045       0   278.2      .1       0
Bank Sta=258.9,278.2
XS Rating Curve= 0 ,0
Exp/Cntr=0.3,0.1

Type RM Length L Ch R = 1 ,4586.3  ,88.6,82.3,75.9
XS GIS Cut Line= 2
     1845850.399      477158.163     1846184.441      477435.265
#Sta/Elev= 30
       0  855.27     9.6  850.85    28.9   843.2    38.6  839.55    48.2  836.88
    57.9  836.01    86.8   836.2     135     836   192.9  836.27   202.5  836.75
   212.2  838.38   221.8  837.88   231.5  833.62   241.1  831.05   250.8   830.9
   260.4  831.01     270  833.82   279.7  837.84   289.3   839.6     299  839.77
   308.6  842.31   327.9  852.72   337.6  855.48   356.9   860.5   366.5  862.72
   385.8  866.42   405.1   871.1   414.7  873.74   424.4  876.77     434  880.26
#Mann= 3 , 0 , 0
       0      .1       0   241.1    .045       0   260.4      .1       0
Bank Sta=241.1,260.4
XS Rating Curve= 0 ,0
Exp/Cntr=0.3,0.1

Type RM Length L Ch R = 1 ,4504    ,51.1,51.1,51.1
XS GIS Cut Line= 2
     1845768.374      477284.076     1846203.161      477476.352
#Sta/Elev= 30
       0  855.17     9.7  849.17    19.4  844.59    38.8  837.02    48.5  834.93
    58.2  834.55   116.4  835.88   155.2  836.31   184.3  836.17     194  836.36
   203.7  837.69   213.4  839.88   223.2  836.56   232.8  831.52   242.6  830.14
   253.2  830.77     262  832.82   271.7  836.47   281.4  838.44   291.1  839.54
   310.5  839.65   320.2  840.26   329.9  841.48   339.6  843.26     359  848.04
   368.7  850.84   388.1  857.43   436.6  876.97   446.3  881.25   475.4  895.18
#Mann= 3 , 0 , 0
       0     .08       0   232.8    .045       0   253.2     .08       0
Bank Sta=232.8,253.2
XS Rating Curve= 0 ,0
Exp/Cntr=0.3,0.1

Type RM Length L Ch R = 1 ,4452.9  ,196.8,201.5,206.2
XS GIS Cut Line= 2
     1845738.861      477324.997     1846173.647      477517.273
#Sta/Elev= 30
       0  871.37     9.7   865.9    29.1  852.69    38.8  847.26    48.5  842.66
    58.2   838.5    67.9  835.45    77.6  834.25   164.9  835.33   184.3  836.71
   203.7   838.9   213.4  839.33   223.2  834.44   232.8  830.39   242.6  829.71
   252.3  829.97   271.7  833.38   291.1  833.85   300.8  835.11   310.5  837.23
   329.9  837.03   339.6  838.05     359  842.63   378.4   849.1   388.1  851.71
   407.5  853.89   417.2  855.91   426.9   859.6     456   874.3   475.4  882.66
#Mann= 3 , 0 , 0
       0     .08       0   232.8    .045       0   252.3     .08       0
Bank Sta=232.8,252.3
XS Rating Curve= 0 ,0
Exp/Cntr=0.3,0.1

Type RM Length L Ch R = 1 ,4251.4  ,176.8,166.1,155.3
XS GIS Cut Line= 3
     1845695.371      477480.308     1845962.733       477671.28
     1846104.226       477827.53
#Sta/Elev= 30
       0  872.28     9.7  869.42    19.3  865.71      29  860.68    48.3     849
      58  843.86    67.6  839.24    77.3  835.12      87  832.51    96.6  831.89
   106.3  831.72     116  831.89   125.6  833.21   135.3  835.18     145  831.87
   154.6  828.19   164.3   827.4   173.9  827.53   177.7  827.91   193.3  829.84
   202.9  830.65   231.9  831.62   270.6  832.24   309.2  833.25   328.6  834.88
   357.3  835.21   405.2  836.62   443.5   839.3   520.2  847.52   539.4  848.55
#Mann= 3 , 0 , 0
       0      .1       0   154.6    .045       0   177.7     .08       0
Bank Sta=154.6,177.7
XS Rating Curve= 0 ,0
Exp/Cntr=0.3,0.1

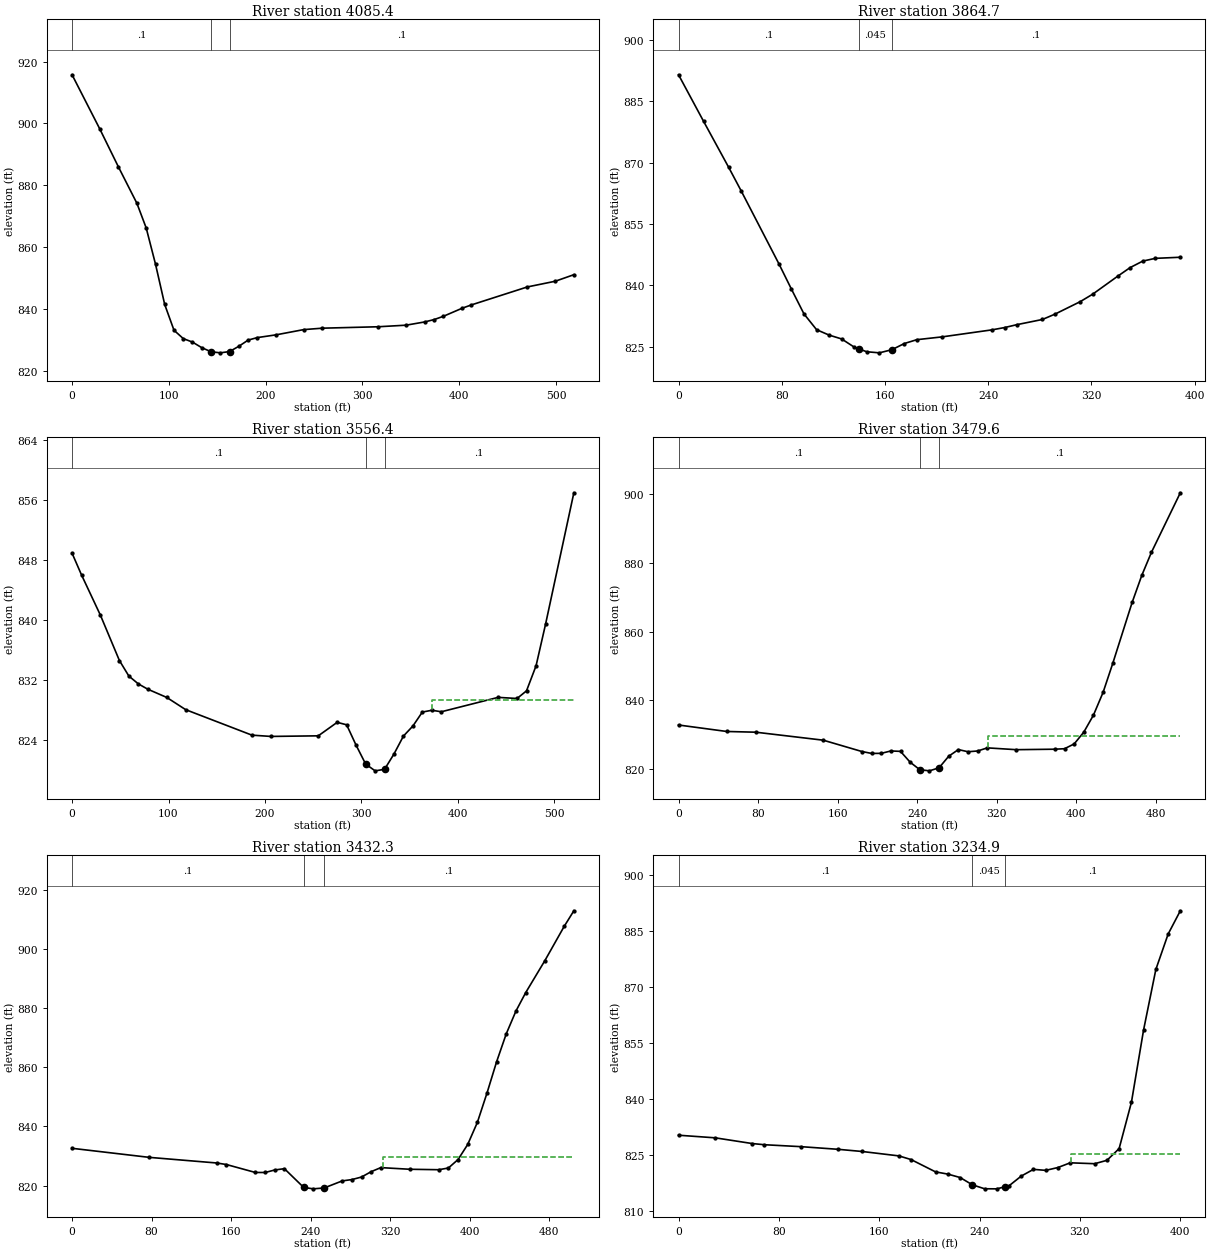
Type RM Length L Ch R = 1 ,4085.4  ,223.5,220.6,217.7
XS GIS Cut Line= 3
     1845610.689      477704.771     1845875.934        477743.3
     1846096.508      477861.821
#Sta/Elev= 30
       0  915.74    28.7  898.19    47.9  885.95      67  874.18    76.6   866.2
    86.2  854.52    95.7  841.48   105.3  833.15   114.9  830.45   124.4  829.32
     134  827.52   143.6   826.2   153.2  825.85   162.7  826.27   172.3  827.97
   181.9  829.97   191.4  830.78   210.6  831.66   239.3  833.36   258.5  833.82
   316.2  834.28   345.1  834.79   364.3  835.84     374   836.6   383.6  837.66
   402.9  840.26   412.5  841.34   470.3  847.15   499.2     849   518.4  851.11
#Mann= 3 , 0 , 0
       0      .1       0   143.6    .045       0   162.7      .1       0
Bank Sta=143.6,162.7
XS Rating Curve= 0 ,0
Exp/Cntr=0.3,0.1

Type RM Length L Ch R = 1 ,3864.7  ,306.3,308.3,310.3
XS GIS Cut Line= 2
     1845608.566      477944.717     1845997.455      477950.794
#Sta/Elev= 30
       0  891.49    19.4  880.11    38.9  868.83    48.6  863.06    77.8  845.25
    87.5  839.06    97.2  833.01     107  829.14   116.7  827.82   126.4  826.88
   136.1  824.89   139.9  824.44   145.8  823.75   155.6  823.48   165.3  824.24
     175  825.76   184.7   826.7   204.2  827.38   243.1  829.11   252.8  829.67
   262.5  830.39     282  831.64   291.7  832.94   311.2  835.98   320.9  837.81
   340.3  842.21     350  844.33   359.8  845.92   369.5  846.59   388.9  846.86
#Mann= 3 , 0 , 0
       0      .1       0   139.9    .045       0   165.3      .1       0
Bank Sta=139.9,165.3
XS Rating Curve= 0 ,0
Exp/Cntr=0.3,0.1

Type RM Length L Ch R = 1 ,3556.4  ,76.7,76.9,77
XS GIS Cut Line= 2
     1845494.851      478212.947     1846012.212      478268.502
#Sta/Elev= 30
       0  848.94     9.8  846.04    29.4  840.67    49.1  834.62    58.9  832.55
    68.7  831.51    78.5   830.8    98.2   829.7   117.8  828.07   186.5  824.67
   206.2   824.5   255.3  824.58   274.9  826.38   284.7  826.05   294.5  823.33
   304.4  820.82   314.2  819.91     324  820.11   333.8  822.16   343.6  824.55
   353.4  825.89   363.2  827.75   373.1  827.99   382.9  827.79   441.8  829.71
   461.4  829.56   471.2  830.58   481.1  833.92   490.9  839.44   520.3     857
#Mann= 3 , 0 , 0
       0      .1       0   304.4    .045       0     324      .1       0
#XS Ineff= 2 , 0
                          373.63          829.36
Permanent Ineff=
       F       F
Bank Sta=304.4,324
XS Rating Curve= 0 ,0
Exp/Cntr=0.3,0.1

Type RM Length L Ch R = 1 ,3479.6  ,47.2,47.3,47.5
XS GIS Cut Line= 2
     1845536.698      478289.972     1846037.868      478350.391
#Sta/Elev= 30
       0  832.77    48.5  830.88    77.7  830.67   145.6  828.34   184.4  825.04
   194.2  824.48   203.9   824.5   213.6   825.2   223.3  825.08     233  821.92
   242.7  819.73   252.4   819.4   262.1  820.29   271.8  823.66   281.5   825.6
   291.2  824.97   300.9  825.19   310.6   826.1   339.8  825.57   378.6  825.71
   388.3  825.85     398  827.25   407.7  830.69   417.4  835.64   427.1  842.29
   436.8  850.71   456.3   868.5     466  876.38   475.7  883.11   504.8   900.5
#Mann= 3 , 0 , 0
       0      .1       0   242.7    .045       0   262.1      .1       0
#XS Ineff= 2 , 0
                          311.54           829.5
Permanent Ineff=
       F       F
Bank Sta=242.7,262.1
XS Rating Curve= 0 ,0
Exp/Cntr=0.3,0.1

Type RM Length L Ch R = 1 ,3432.3  ,197.5,197.3,197.2
XS GIS Cut Line= 2
     1845525.747      478334.771     1846026.918       478395.19
#Sta/Elev= 30
       0  832.63    77.7  829.57   145.6  827.67   155.3  827.15   184.4  824.47
   194.2  824.46   203.9  825.31   213.6  825.75     233  819.42   242.7  818.94
   253.6  819.24   271.8  821.62   281.5  822.07   291.2  822.93   300.9  824.74
   310.6  826.11   339.8  825.55   368.9   825.4   378.6  825.98   388.3  828.84
     398  833.92   407.7  841.36   417.4  851.28   427.1  861.88   436.8  871.31
   446.6  879.04   456.3  885.19   475.7  896.06   495.1  907.61   504.8  912.86
#Mann= 3 , 0 , 0
       0      .1       0     233    .045       0   253.6      .1       0
#XS Ineff= 2 , 0
                          312.64          829.67
Permanent Ineff=
       F       F
Bank Sta=233,253.6
XS Rating Curve= 0 ,0
Exp/Cntr=0.3,0.1

Type RM Length L Ch R = 1 ,3234.9  ,342.2,341.3,340.4
XS GIS Cut Line= 2
     1845487.038      478529.787     1845884.608      478574.926
#Sta/Elev= 30
       0  830.36    29.3  829.66    58.6  828.14    68.3  827.82    97.6   827.3
   126.9   826.6   146.4  826.01   175.7  824.83   185.4  823.85   204.9  820.56
   214.7  819.96   224.5  819.05   234.2  817.11     244  816.04   253.7  816.02
   260.2  816.56   263.5  816.83   273.3  819.44     283  821.23   292.8  820.96
   302.5  821.72   312.3  822.98   331.8  822.74   341.6  823.65   351.3  826.78
   361.1  839.15   370.8  858.51   380.6  874.71   390.4  884.17   400.1  890.38
#Mann= 3 , 0 , 0
       0      .1       0   234.2    .045       0   260.2      .1       0
#XS Ineff= 2 , 0
                          313.19          825.29
Permanent Ineff=
       F       F
Bank Sta=234.2,260.2
XS Rating Curve= 0 ,0
Exp/Cntr=0.3,0.1

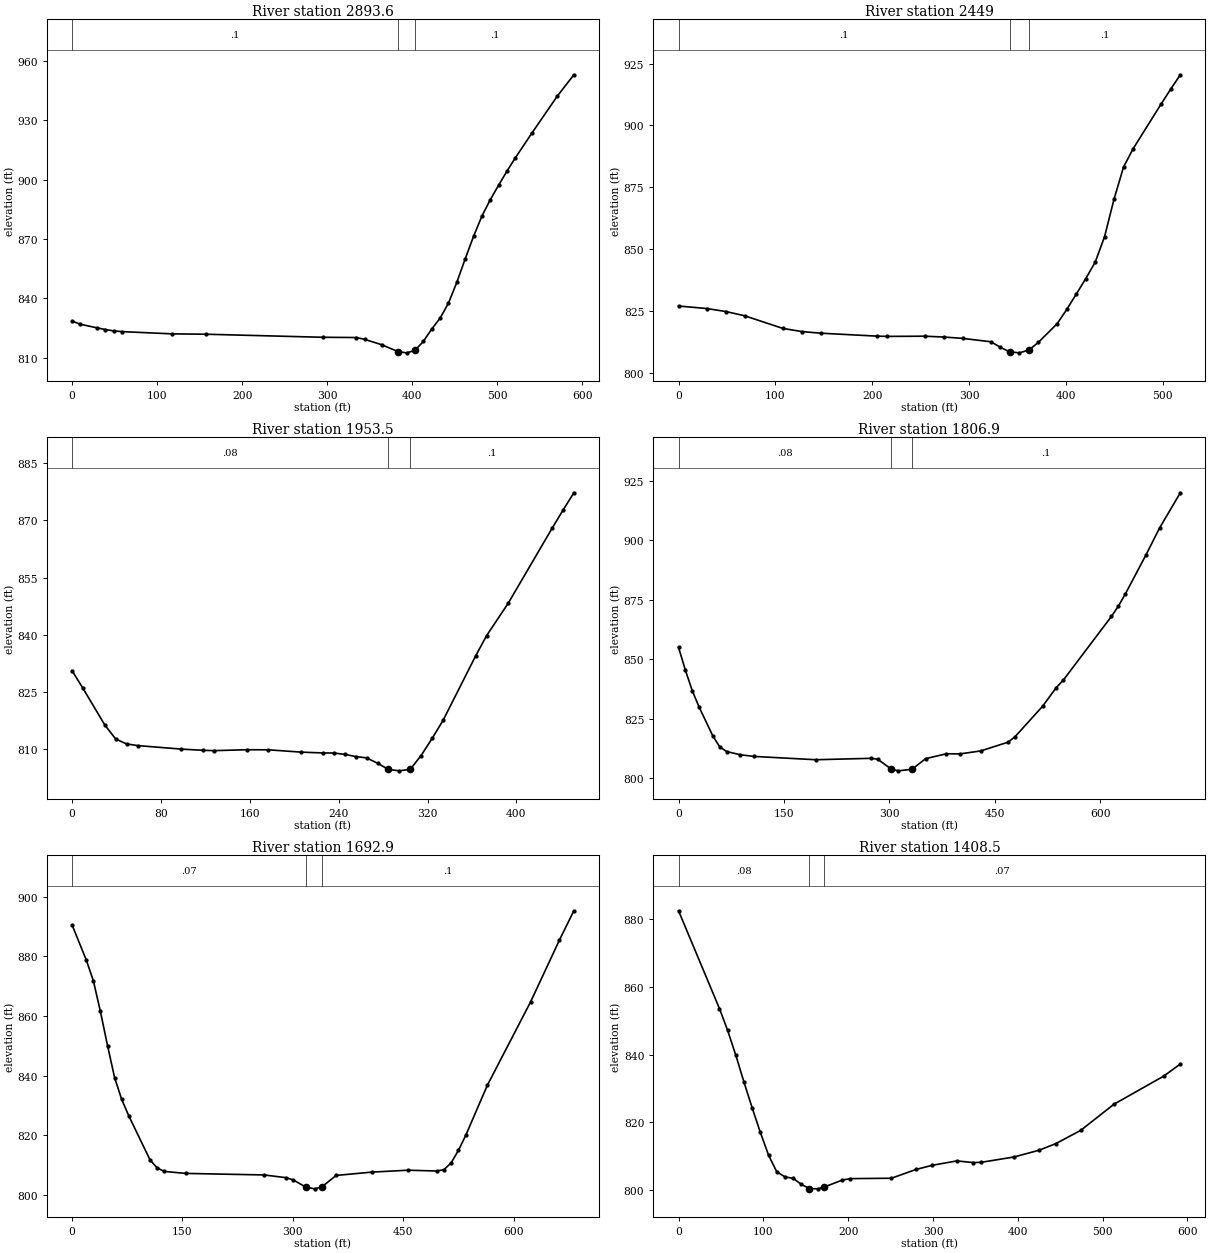
Type RM Length L Ch R = 1 ,2893.6  ,463,444.6,425.5
XS GIS Cut Line= 2
      1845329.05      478870.495     1845917.591      478913.464
#Sta/Elev= 30
       0  828.48     9.8  826.86    29.5  825.02    39.3  824.16    49.2  823.48
      59  823.12     118  821.99   157.4  821.81     295  820.26   334.4  820.14
   344.2  819.19   363.9  816.53   383.6  812.97   393.4  812.39   403.2   813.6
   413.1  818.19   422.9   824.4   432.8  829.93   442.6  837.53   452.4     848
   462.2  859.82   472.1   871.3   481.9  881.55   491.8  889.88   501.6  897.22
   511.4  904.34   521.3  911.09   540.9  923.71   570.4  942.18   590.1  953.12
#Mann= 3 , 0 , 0
       0      .1       0   383.6    .045       0   403.2      .1       0
Bank Sta=383.6,403.2
XS Rating Curve= 0 ,0
Exp/Cntr=0.3,0.1

Type RM Length L Ch R = 1 ,2449    ,495,495.6,496.1
XS GIS Cut Line= 2
     1845590.334       479552.96     1845966.202       479196.19
#Sta/Elev= 30
       0  826.95    29.3  825.92    48.9  824.72    68.4  822.99   107.6   817.9
   127.1  816.63   146.7  815.96   205.3  814.76   215.1  814.66   254.2  814.74
   273.8  814.41   293.3  813.86   322.7  812.48   332.4  810.24   341.9  808.41
     352  808.01   361.8  809.13   371.6  812.24   391.1  819.83   400.9  825.57
   410.7  831.74   420.4  837.95   430.2   844.6     440  855.03   449.8  870.28
   459.6  883.19   469.3  890.47   498.7  908.86   508.4  914.76   518.2  920.48
#Mann= 3 , 0 , 0
       0      .1       0   341.9    .045       0   361.8      .1       0
Bank Sta=341.9,361.8
XS Rating Curve= 0 ,0
Exp/Cntr=0.3,0.1

Type RM Length L Ch R = 1 ,1953.5  ,125.1,146.5,167.4
XS GIS Cut Line= 2
      1845973.82      479861.804      1846308.89      479558.853
#Sta/Elev= 30
       0  830.59     9.8  825.97    29.5  816.35    39.3  812.68    49.1   811.4
    58.9  810.97    98.2  810.05   117.8  809.73   127.7  809.64   157.1  809.88
   176.8  809.86   206.2  809.25   225.9  809.04   235.7  809.02   245.5  808.66
   255.3   808.1   265.1  807.75     275  806.34   284.8  804.71   294.6  804.35
   304.4  804.75   314.2  808.36   324.1  812.83   333.9  817.54   363.3  834.47
   373.2  839.79   392.8  848.35   432.1   867.9   441.9  872.62   451.7   877.2
#Mann= 3 , 0 , 0
       0     .08       0   284.8    .045       0   304.4      .1       0
Bank Sta=284.8,304.4
XS Rating Curve= 0 ,0
Exp/Cntr=0.3,0.1

Type RM Length L Ch R = 1 ,1806.9  ,116.3,114,112.4
XS GIS Cut Line= 4
     1846023.299      479930.381     1846212.134      479775.998
     1846514.218      479800.303     1846641.959      479693.266
#Sta/Elev= 30
       0  854.93     9.8  845.33    19.5  836.75    29.3  829.82    48.8  817.72
    58.5  813.19    68.3  811.18    87.8  809.82   107.3  809.12   195.1  807.73
   273.2  808.32     283  807.98   302.6  803.76   312.3  803.06   331.9  803.71
   351.4  808.17   380.8  810.23   400.3  810.18   429.7  811.43   468.8  815.12
   478.5   817.4   517.6  830.16   537.2  838.07     547  841.12   615.6  867.97
   625.4  872.25   635.2   877.3   664.6  893.74   684.2  905.21   713.6  919.94
#Mann= 3 , 0 , 0
       0     .08       0   302.6    .045       0   331.9      .1       0
Bank Sta=302.6,331.9
XS Rating Curve= 0 ,0
Exp/Cntr=0.3,0.1

Type RM Length L Ch R = 1 ,1692.9  ,293.2,284.4,275.4
XS GIS Cut Line= 4
     1846058.587       479998.38     1846214.837      479869.908
      1846516.92      479894.213     1846654.796      479784.474
#Sta/Elev= 30
       0  890.48    19.3  878.73    28.9   871.8    38.5   861.5    48.2  850.02
    57.8  839.33    67.4  832.05    77.1  826.52     106  811.73   115.6  809.12
   125.2  807.94   154.1  807.27   260.9  806.75   290.3  805.85     300  805.14
   317.6  802.68   329.4   802.1   339.2  802.74   358.7  806.59   407.6  807.71
   456.5  808.34   495.6  808.07   505.3  808.55   515.1  810.87   524.9  815.03
   534.7  819.98   564.1  836.79   622.8  864.69     662  885.41   681.6  895.22
#Mann= 3 , 0 , 0
       0     .07       0   317.6    .045       0   339.2      .1       0
Bank Sta=317.6,339.2
XS Rating Curve= 0 ,0
Exp/Cntr=0.3,0.1

Type RM Length L Ch R = 1 ,1408.5  ,428.3,432.6,436.9
XS GIS Cut Line= 3
     1846255.265      480197.926     1846617.244      480094.627
     1846832.522      480092.891
#Sta/Elev= 30
       0  882.34    48.3  853.51    57.9  847.11    67.6  839.74    77.2  831.85
    86.9  824.24    96.5  817.04   106.2  810.33   115.8  805.48   125.5  803.96
   135.1  803.53   144.8  801.76   154.4  800.52   164.1  800.44   171.5  800.94
     193  803.02   202.7  803.45     251  803.56   279.9  806.14   299.2  807.38
   328.2  808.67   347.5  808.17   357.1  808.26     396  809.84   425.4  811.84
   444.9  813.76   474.3  817.67   513.4  825.36   572.1  833.64   591.7  837.21
#Mann= 3 , 0 , 0
       0     .08       0   154.4    .045       0   171.5     .07       0
Bank Sta=154.4,171.5
XS Rating Curve= 0 ,0
Exp/Cntr=0.3,0.1

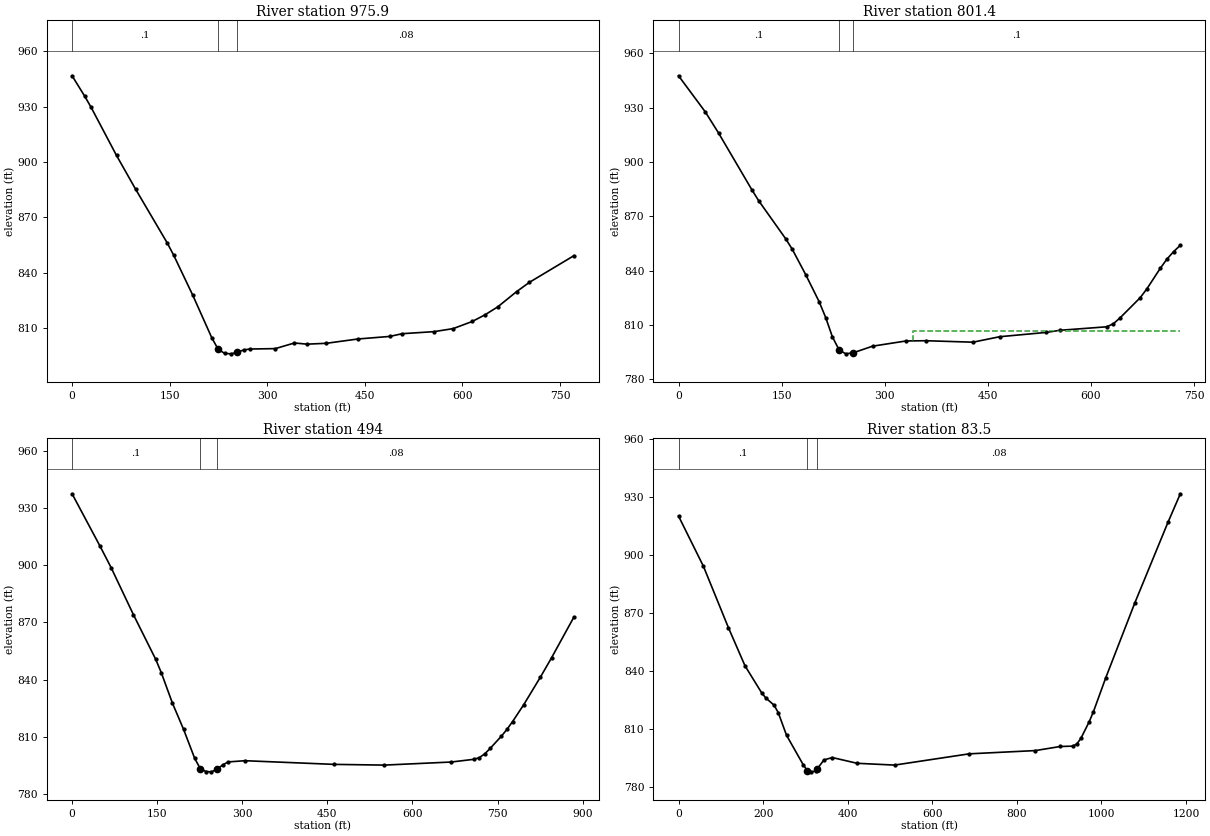
Type RM Length L Ch R = 1 ,975.9   ,163.9,174.5,184.9
XS GIS Cut Line= 2
     1846340.863      480568.225     1847109.369      480503.808
#Sta/Elev= 30
       0   946.7    19.5   935.6    29.3  929.57    68.3  903.53    97.6  885.27
   146.4  856.03   156.2  849.46   185.5  827.79   214.8  804.68   224.5  798.51
   234.3  796.32     244  796.03   253.8   796.8   263.6  798.15   273.3  798.64
   312.4  798.86   341.7  801.91   361.2  801.28   390.5  801.73   439.3  804.08
   488.1  805.46   507.6  806.95   556.4  808.06   585.7   809.7     615  813.56
   634.5  817.15   654.1  821.45   683.3  829.77   702.9  834.78   771.2   849.2
#Mann= 3 , 0 , 0
       0      .1       0   224.5    .045       0   253.8     .08       0
Bank Sta=224.5,253.8
XS Rating Curve= 0 ,0
Exp/Cntr=0.3,0.1

Type RM Length L Ch R = 1 ,801.4   ,293.9,307.4,320.9
XS GIS Cut Line= 2
     1846324.887       480628.58     1847001.971      480901.149
#Sta/Elev= 30
       0  947.67    38.9  927.71    58.4  915.91     107  884.43   116.8  878.48
   155.7  857.65   165.4  851.78   184.9  837.79   204.4  822.88   214.1  813.98
   223.8  803.33   233.6  796.11   243.3  793.95   254.4  794.57   282.2  798.18
   330.9  801.07   360.1   801.2   428.2  800.39   467.1  803.41   535.2  805.81
   554.7  806.96   622.8   808.9   632.6  810.61   642.3  813.86   671.5  824.97
   681.2  829.86   700.7   841.2   710.4  846.31   720.2  850.48   729.9  853.97
#Mann= 3 , 0 , 0
       0      .1       0   233.6    .045       0   254.4      .1       0
#XS Ineff= 2 , 0
                          340.66          806.35
Permanent Ineff=
       F       F
Bank Sta=233.6,254.4
XS Rating Curve= 0 ,0
Exp/Cntr=0.3,0.1

Type RM Length L Ch R = 1 ,494     ,411.8,410.5,409.1
XS GIS Cut Line= 2
      1846212.04      480737.955     1846705.096       481472.33
#Sta/Elev= 30
       0  937.62    49.1   910.2    68.8  898.83   108.1  874.12   147.4  850.64
   157.2  843.66   176.9   827.6   196.6  813.78   216.2  798.52     226  793.18
   235.9  791.65   245.7  791.49   255.5  792.85   265.4   795.1   275.2   796.7
   304.7  797.34   461.9  795.41   550.4  795.03   668.3  796.65   707.6  798.05
   717.5  798.89   727.3   800.9   737.1  803.84   756.8  810.25   766.6  813.82
   776.4  817.87   796.1  826.76   825.6   841.3   845.2  851.44   884.5  872.78
#Mann= 3 , 0 , 0
       0      .1       0     226    .045       0   255.5     .08       0
Bank Sta=226,255.5
XS Rating Curve= 0 ,0
Exp/Cntr=0.3,0.1

Type RM Length L Ch R = 1 ,83.5    ,88.4,83.5,78.6
XS GIS Cut Line= 3
     1845840.512      480948.024     1846166.901       481378.58
     1846793.637      481536.566
#Sta/Elev= 30
       0  920.24    58.9  894.25   117.9  862.56   157.2  842.78   196.5  828.84
   206.3  826.18   225.9  822.44   235.8  818.59   255.4  806.85   294.7  791.68
   304.5  788.61   314.4  787.95   324.2  788.39   328.1  789.52   343.8  794.09
   363.5  795.35   422.4  792.37   510.8  791.44   687.2  797.26   843.9  798.95
   902.6  801.06     932  801.24   941.8  802.36   951.6  805.33   971.2   813.9
     981     819  1010.4  836.69  1078.9  875.28  1157.2  916.93  1186.6  931.78
#Mann= 3 , 0 , 0
       0      .1       0   304.5    .045       0   328.1     .08       0
Bank Sta=304.5,328.1
XS Rating Curve= 0 ,0
Exp/Cntr=0.3,0.1